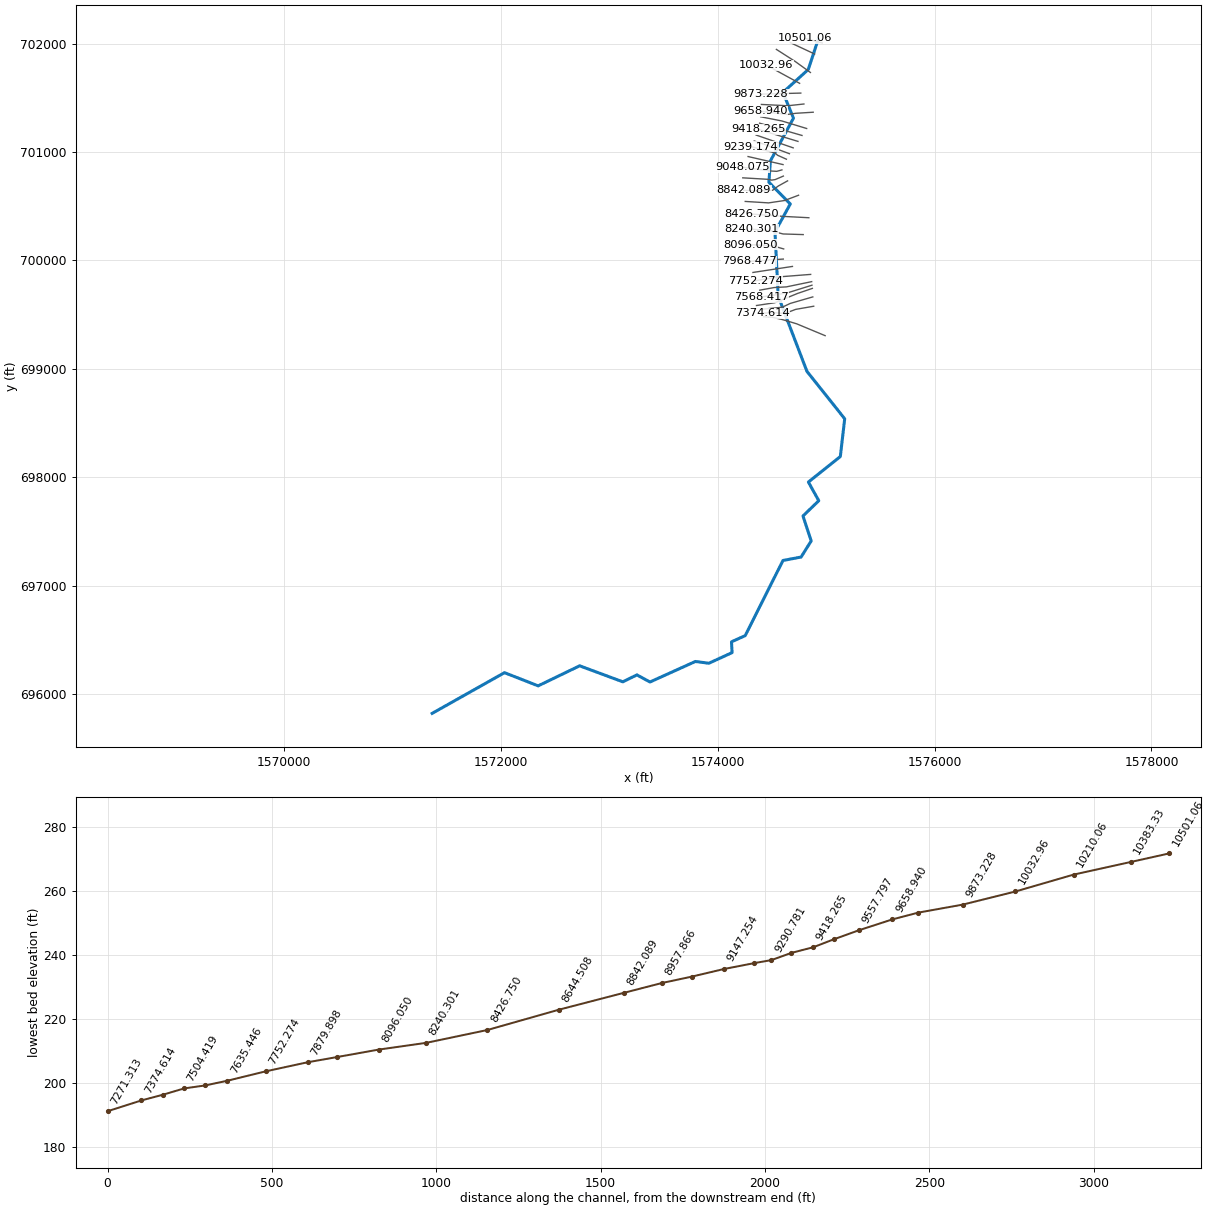
--- SusquehannaRiverTrib.prj (project) ---

Proj Title=SusquehannaRiverTrib
Current Plan=p01
Default Exp/Contr=0.3,0.1
English Units
Geom File=g01
Flow File=f01
Plan File=p01
Y Axis Title=Elevation
X Axis Title(PF)=Main Channel Distance
X Axis Title(XS)=Station
BEGIN DESCRIPTION:
Susquehanna River Trib - Georeferenced HEC-RAS model.  This was formerly an approximate method stream.  Projection:  MD Stateplane.  Horizontal datum:  NAD83.  Vertrial datum: NAVD88.  Units:Feet.  Created by: Aaron W. Buesing, USACE- St Paul District as part of FEMA Map Modernization study for Cecil County, MD.
END DESCRIPTION:
DSS Export Rating Curves= 0
DSS Export Rating Curve Sorted= 0
DSS Export Volume Flow Curves= 0
DXF OffsetX= 0
DXF OffsetY= 0
DXF ScaleX= 1
DXF ScaleY= 10

--- SusquehannaRiverTrib.p01 (plan) ---

Plan Title=SusquehannaRiverTrib_100yr
Program Version=4.00
Short Identifier=SusqueTrib100
Geom File=g01
Flow File=f01
Subcritical Flow
K Sum by GR= 0
Std Step Tol= 0.01
Critical Tol= 0.01
Num of Std Step Trials= 20
Max Error Tol= 0.3
Flow Tol Ratio= 0.001
Split Flow NTrial= 30
Split Flow Tol= 0.02
Split Flow Ratio= 0.02
Log Output Level= 0
Friction Slope Method= 1
Unsteady Friction Slope Method= 2
Unsteady Bridges Friction Slope Method= 1
Secant Critical Depth
Global Vel Dist= 0 , 0 , 0
Global Log Level= 0
CheckData=True
Encroach Param=-1 ,0,0, 0
Computation Interval=1HOUR
Output Interval=1HOUR
Run HTab= 0
Run UNet= 0
Run PostProcess= 0
Run WQNet= 0
UNET Theta= 1
UNET Theta Warmup= 1
UNET ZTol= 0.02
UNET ZSATol= 0.05
UNET MxIter= 20
UNET MaxInSteps= 0
UNET DtIC= 0
UNET DtMin= 0
UNET MaxCRTS= 20
UNET WFStab= 2
UNET SFStab= 1
UNET WFX= 1
UNET SFX= 1
UNET DSS MLevel= 4
UNET DZMax Abort= 100
UNET Convert EG Bridges= 0
UNET Use Existing IB Tables=-1
UNET Froude Reduction=False
UNET Froude Limit= 1
UNET Froude Power= 10
UNET Time Slicing=0,0, 5
Instantaneous Interval=1HOUR
Write IC File= 0
Echo Input=False
Echo Output=False
Write Detailed= 0
Detailed Automatic Start=False, 10
WQ ULTIMATE=-1
WQ Max Comp Step=1HOUR
WQ Output Interval=15MIN
WQ Output Selected Increments= 0
WQ Output face flow=0
WQ Output face velocity=0
WQ Output face area=0
WQ Output face dispersion=0
WQ Output cell volume=0
WQ Output cell surface area=0
WQ Output cell continuity=0
WQ Output face conc=0
WQ Output face dconc_dx=0
WQ Output face courant=0
WQ Output face peclet=0
WQ Output face adv mass=0
WQ Output face disp mass=0
WQ Output cell mass=0
WQ Output cell source sink temp=0
WQ Output cell source sink nsm=0
WQ Output MaxMinRange=-1
WQ Create Restart=0
WQ Fixed Restart=0
Sorting and Armoring Iterations= 10
XS Update Threshold= 0.02
Hydraulics Update Threshold= 0.02
Energy Slope Method= 1
Volume Change Method= 0
XS Weighting Method= 0
Number of US Weighted Cross Sections= 1
Number of DS Weighted Cross Sections= 1
Upstream XS Weight=0.25
Main XS Weight=0.5
Downstream XS Weight=0.25
Number of DS XS's Weighted with US Boundary= 1
Upstream Boundary Weight= 1
Weight of XSs Associated with US Boundary= 0
Number of US XS's Weighted with DS Boundary= 1
Downstream Boundary Weight= 0.5
Weight of XSs Associated with DS Boundary= 0.5
Sediment Output Level= 4
Mass or Volume Output= 0
Output Increment Type= 1
Profile and TS Output Increment= 10
XS Output Flag= 0
XS Output Increment= 10
Disregard all LS=0
Disregard all Conn=0
Disregard all Breaches=0
Disregard all Pumps=0

--- SusquehannaRiverTrib.f01 (steady flow) ---

Flow Title=SusquehannaRiverTrib_100yr
Program Version=4.00
Number of Profiles= 2
Profile Names=100CUR,100ULT
River Rch & RM=SusquehannaTrib,Reach1          ,10501.06
     660     660
River Rch & RM=SusquehannaTrib,Reach1          ,9658.940
     790     810
River Rch & RM=SusquehannaTrib,Reach1          ,8842.089
     840     850
River Rch & RM=SusquehannaTrib,Reach1          ,7076.824
     950     950
River Rch & RM=SusquehannaTrib,Reach1          ,5633.481
     970     970
River Rch & RM=SusquehannaTrib,Reach1          ,4182.476
    1080    1080
River Rch & RM=SusquehannaTrib,Reach1          ,2891.653
    1120    1120
River Rch & RM=SusquehannaTrib,Reach1          ,868.7341
    1250    1250
River Rch & RM=SusquehannaTrib,Reach1          ,272.6315
    1500    1540
Boundary for River Rch & Prof#=SusquehannaTrib,Reach1          , 1
Up Type= 0
Dn Type= 3
Dn Slope=0.0001
Boundary for River Rch & Prof#=SusquehannaTrib,Reach1          , 2
Up Type= 0
Dn Type= 3
Dn Slope=0.0001
DSS Import GetInterval= 0
DSS Import GetPeak= 0
DSS Import FillOption= 0

--- SusquehannaRiverTrib.g01 (geometry) ---

Geom Title=SusquehannaRiverTrib
Program Version=4.00

River Reach=SusquehannaTrib ,Reach1
Reach XY= 30
1574926.15464625702039.9033874421574834.43141285701761.477241114
1574600.76076461701549.7346373051574697.87444746701312.689444914
1574484.89977284700917.7558248791574471.33766654700721.042694241
1574668.44191229700520.8636662221574527.23999214700263.512009293
1574557.09074859699670.2960678641574821.82882765 698977.48950012
1575170.38810803 698539.495140121575129.95390159698190.784030944
1574835.31690526697955.9264850021574931.35648902 697783.52062434
1574785.60478595697642.8459036951574861.33644016697412.689368263
1574768.25842948697264.1876330671574600.92955124697232.244952157
  1574252.521634696539.2368545981574126.23169692696482.120802626
 1574131.3086793696382.4850230221573917.86387751696284.330029994
1573793.05472688696300.830222815  1573374.203679696111.416471124
1573253.83688793696176.9941604141573123.73921391696113.108798549
1572725.61917746696260.7643700241572342.73008807696075.877594322
1572032.18799807696197.5136309421571364.99613619695822.058694452

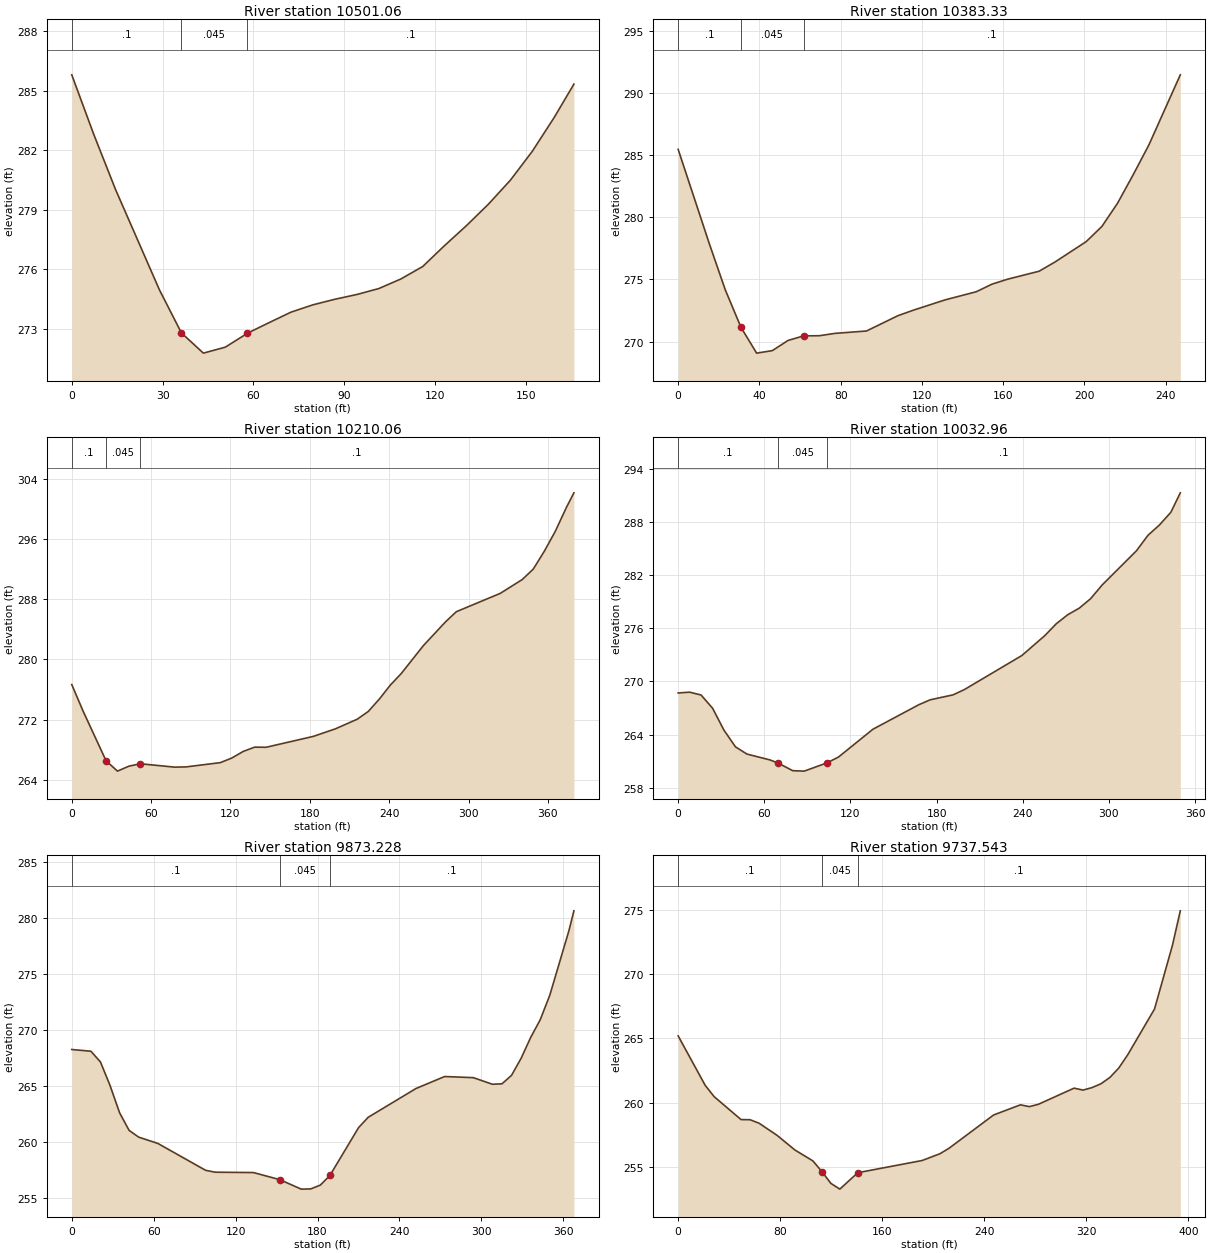
Type RM Length L Ch R = 1 ,10501.06,120.42,117.73,109.13
XS GIS Cut Line= 2
1574963.81587426702005.8319087181574803.53934693702048.696561351
#Sta/Elev= 28
       0  285.81    7.25  282.81   14.49  280.01   21.74  277.48   28.98  274.95
   31.06274.3292   31.56  274.18   36.23  272.78   43.48  271.76   50.72  272.06
   56.56  272.62   57.06272.6696   57.97  272.76   65.21   273.3   72.46  273.83
   79.71   274.2   86.95  274.48    94.2  274.72  101.44  275.02  108.69   275.5
  115.94  276.13  123.18  277.19  130.43   278.2  137.67  279.28  144.92  280.49
  152.17  281.95  159.41  283.66  165.91  285.34
#Mann= 3 , 0 , 0
       0      .1       0   36.23    .045       0   57.97      .1       0
Bank Sta=36.23,57.97
XS Rating Curve= 0 ,0
Exp/Cntr=0.3,0.1

Type RM Length L Ch R = 1 ,10383.33,174.6,173.27,158.35
XS GIS Cut Line= 2
1574893.25048095701904.0225719811574669.25668558702008.715324163
#Sta/Elev= 25
       0  285.46   15.45  277.82   23.18  274.17   30.91  271.15   38.63  269.07
   46.36  269.27   54.09  270.09   61.81  270.46   69.54  270.47   77.27  270.66
   92.72  270.85  108.18  272.08   115.9  272.53  131.36  273.35  146.81  274.01
  154.54  274.62  162.26  275.02  177.72  275.66  185.44  276.39   200.9  278.04
  208.63  279.26  216.35  281.13  224.08  283.43  231.81  285.83  247.25  291.46
#Mann= 3 , 0 , 0
       0      .1       0   30.91    .045       0   61.81      .1       0
Bank Sta=30.91,61.81
XS Rating Curve= 0 ,0
Exp/Cntr=0.3,0.1

Type RM Length L Ch R = 1 ,10210.06,159.83,177.1,163.17
XS GIS Cut Line= 3
1574854.29503825701733.5925102681574713.08155857701835.850547284
1574540.21678168701946.630087405
#Sta/Elev= 30
       0  276.65    8.64  273.09   25.93  266.52   34.57  265.14   43.21   265.8
   51.86  266.12   77.78  265.67   86.43   265.7  112.35  266.27     121  266.88
  129.64  267.76  138.28  268.33  146.92  268.31  182.66  269.76  199.29  270.76
  215.92  272.05  224.23  273.08  232.55  274.72  240.86  276.58  249.18  278.13
   265.8  281.82  282.43  284.96  290.75  286.34     324  288.78  340.63  290.62
  348.95  292.01  357.26  294.37  365.57  297.02  373.89  300.17  379.67  302.15
#Mann= 3 , 0 , 0
       0      .1       0   25.93    .045       0   51.86      .1       0
Bank Sta=25.93,51.86
XS Rating Curve= 0 ,0
Exp/Cntr=0.3,0.1

Type RM Length L Ch R = 1 ,10032.96,137.17,159.73,175.98
XS GIS Cut Line= 2
1574754.47171643701633.7691884191574447.69760531701801.764534935
#Sta/Elev= 30
       0   268.7    7.98  268.79   15.96  268.47   23.94  266.98   31.92  264.49
    39.9  262.61   47.89  261.79   63.85  261.13   69.36260.7919   79.81  259.91
   87.79  259.86  103.75   260.8  111.73  261.46  135.67   264.6   167.6  267.37
  175.58  267.93  191.54  268.49  199.52   269.1  239.43  272.94  255.39  275.19
  263.37  276.53  271.35  277.55  279.33  278.29  287.31  279.37  295.29  280.91
  319.24  284.79  327.22  286.53   335.2   287.7  343.18  289.14  349.76  291.34
#Mann= 3 , 0 , 0
       0      .1       0   69.36    .045       0  103.75      .1       0
Bank Sta=69.36,103.75
XS Rating Curve= 0 ,0
Exp/Cntr=0.3,0.1

Type RM Length L Ch R = 1 ,9873.228,119.61,135.68,121.79
XS GIS Cut Line= 2
1574765.42793466701543.6847272221574397.78594443701533.945866555
#Sta/Elev= 30
       0  268.23      14  268.08   21.01  267.12   28.01  265.03   35.01  262.59
   42.01  261.01   49.02  260.41   63.02  259.85   98.03  257.45  105.04  257.28
  133.05  257.25   152.4256.6148  168.06  255.77  175.06  255.79  182.06  256.13
  189.07  256.99  210.07  261.26  217.08  262.18  252.09  264.75   273.1  265.82
   294.1  265.72  308.11  265.13  315.11  265.17  322.11  265.93  329.12  267.45
  336.12  269.31  343.12  270.89  350.12  273.08  364.13  278.84  367.77  280.61
#Mann= 3 , 0 , 0
       0      .1       0   152.4    .045       0  189.07      .1       0
Bank Sta=152.4,189.07
XS Rating Curve= 0 ,0
Exp/Cntr=0.3,0.1

Type RM Length L Ch R = 1 ,9737.543,79.95,78.6,81.82
XS GIS Cut Line= 3
1574794.28650077701443.0142482071574645.96608819701426.870529816
1574401.79234782701438.978318587
#Sta/Elev= 30
       0   265.2   21.12  261.36   28.17  260.47   49.29  258.68   56.33  258.67
   63.37   258.4   77.45  257.46   91.54  256.31  105.62  255.46  112.66  254.63
   119.7  253.71  126.74  253.26  140.83  254.54  191.25  255.49  205.27  256.02
  212.27  256.44  247.32  259.04  268.34  259.83  275.35  259.69  282.36  259.87
  310.39  261.13   317.4  260.98  324.41  261.17  331.42  261.47  338.43  261.96
  345.44   262.7  352.45  263.73  373.47   267.3  387.49  272.26  393.67  274.95
#Mann= 3 , 0 , 0
       0      .1       0  112.66    .045       0  140.83      .1       0
Bank Sta=112.66,140.83
XS Rating Curve= 0 ,0
Exp/Cntr=0.3,0.1

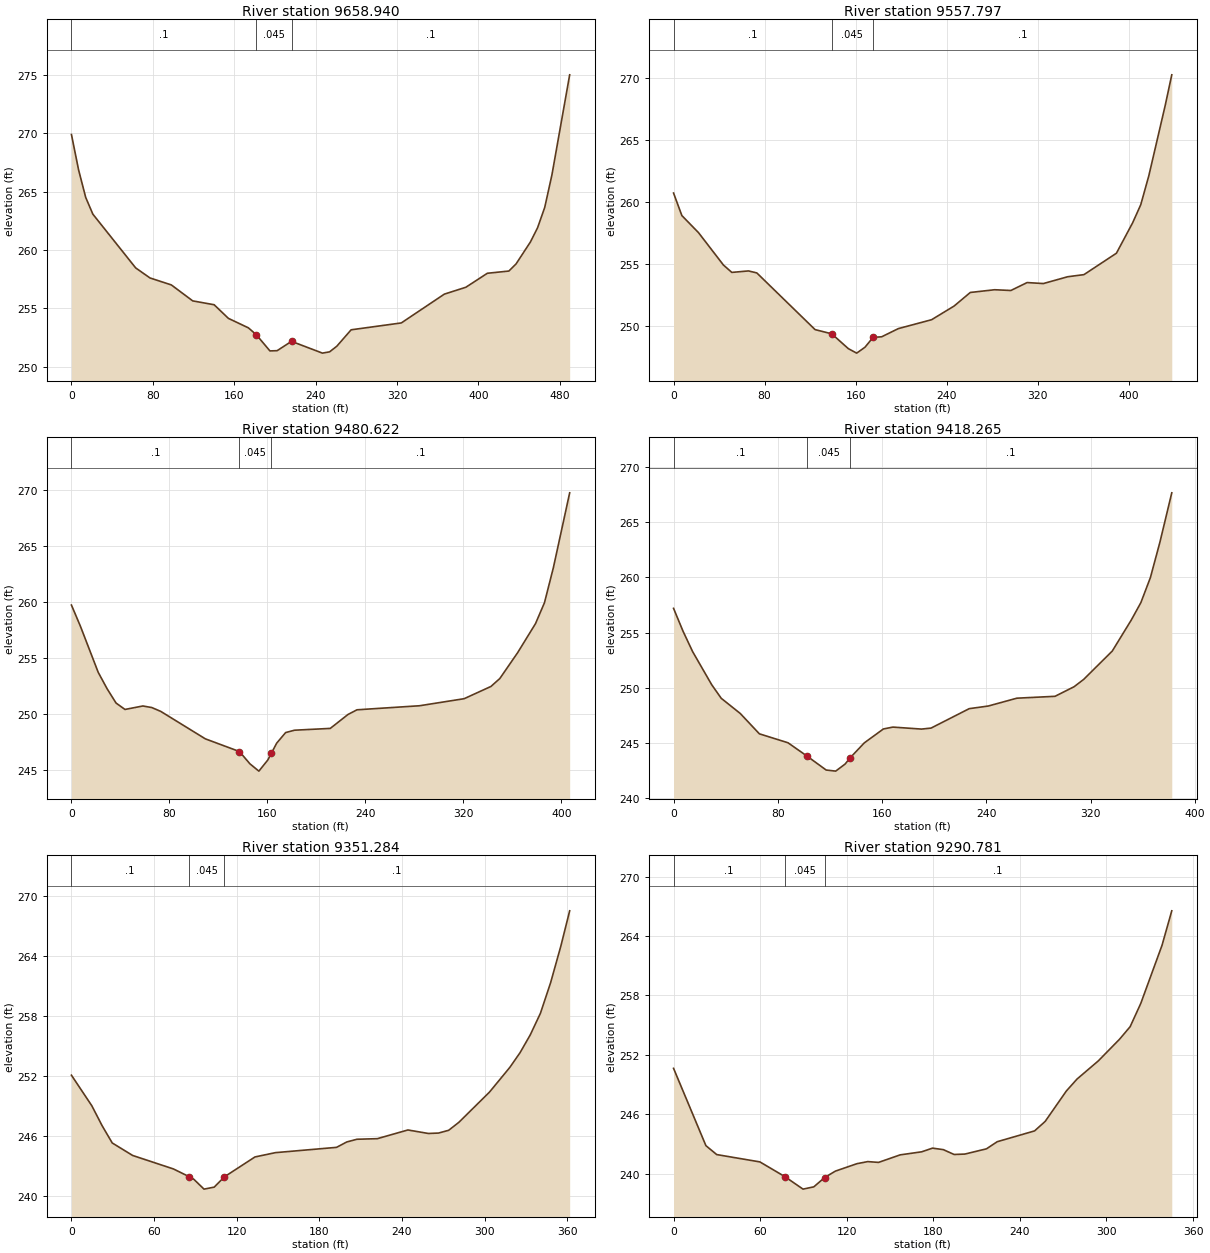
Type RM Length L Ch R = 1 ,9658.940,106.29,101.14,72.6
XS GIS Cut Line= 4
 1574879.8595475701367.1678775851574720.38570407701357.429016918
1574641.25746116701346.472798675 1574392.9165141701375.689380676
#Sta/Elev= 30
       0   269.9    7.01  266.87   14.03   264.5   21.04  263.07   63.12  258.46
   77.14   257.6   98.18     257  119.22  255.63  140.26   255.3  154.29  254.13
   173.9  253.32  181.68  252.73   195.1  251.34  202.17  251.36  216.31  252.16
   246.7  251.15  253.75  251.26   260.8  251.74   274.9  253.15  324.23  253.74
  366.52  256.21  387.67   256.8  408.81     258  429.96  258.19  437.01   258.8
   451.1  260.68  458.15   261.9   465.2  263.65  472.25  266.43  489.71  275.02
#Mann= 3 , 0 , 0
       0      .1       0  181.68    .045       0  216.31      .1       0
Bank Sta=181.68,216.31
XS Rating Curve= 0 ,0
Exp/Cntr=0.3,0.1

Type RM Length L Ch R = 1 ,9557.797,77.36,77.18,76.23
XS GIS Cut Line= 3
1574819.51106073701217.0021909621574590.47205628701286.621976465
1574395.73845342701324.963307574
#Sta/Elev= 30
       0  260.71    7.32  258.89   21.95  257.51    43.9  254.89   51.21   254.3
   65.85  254.42   73.16  254.26  124.38  249.68  139.01  249.34  153.64  248.14
  160.96  247.78  168.27  248.26  175.32  249.05  182.91   249.1  197.54  249.76
   226.8  250.48  246.52  251.58  260.79  252.68  282.19   252.9  296.46  252.84
  310.73  253.48     325   253.4   346.4  253.95  360.67  254.12  389.21  255.85
  403.48  258.31  410.61  259.77  417.75  262.13  432.02  267.76  437.86  270.26
#Mann= 3 , 0 , 0
       0      .1       0  139.01    .045       0  175.32      .1       0
Bank Sta=139.01,175.32
XS Rating Curve= 0 ,0
Exp/Cntr=0.3,0.1

Type RM Length L Ch R = 1 ,9480.622,61.92,62.36,61.2
XS GIS Cut Line= 2
 1574776.3841529701152.9129428861574385.61236858 701266.12719816
#Sta/Elev= 30
       0  259.74    7.29  257.86   21.86  253.74   29.15  252.27   36.44     251
   43.73  250.43    58.3  250.74   65.59   250.6   72.88  250.26  109.32  247.81
  137.19246.6767  145.76  245.58  153.05  244.93  160.33  245.92  163.27246.5312
  167.62  247.43  174.91  248.37   182.2  248.58  211.35  248.74  225.92  249.99
  233.21   250.4  284.23  250.76  320.67  251.39  342.53  252.48  349.82  253.19
  364.39   255.5  378.97  258.09  386.26  259.95  393.54  263.08  406.84  269.75
#Mann= 3 , 0 , 0
       0      .1       0  137.19    .045       0  163.27      .1       0
Bank Sta=137.19,163.27
XS Rating Curve= 0 ,0
Exp/Cntr=0.3,0.1

Type RM Length L Ch R = 1 ,9418.265,67.59,66.98,65.43
XS GIS Cut Line= 2
1574739.33404258701098.1637757721574373.65558305701208.996822402
#Sta/Elev= 30
       0   257.2    7.31  255.12   14.63  253.28   29.26  250.28   36.57  249.05
    51.2  247.67   65.83  245.83   87.77  245.02   102.4  243.81  117.03  242.55
  124.35  242.45  131.66   243.1   135.3  243.64  146.29  245.01  160.92  246.27
  168.23  246.44  190.18  246.26  197.49  246.35  226.75  248.11  241.38  248.35
  263.32  249.06  292.58  249.23  307.21   250.1  314.52  250.76  336.46  253.33
  351.09  256.15  358.41  257.72  365.72  259.99  373.04  263.21  382.11  267.67
#Mann= 3 , 0 , 0
       0      .1       0   102.4    .045       0   135.3      .1       0
Bank Sta=102.4,135.3
XS Rating Curve= 0 ,0
Exp/Cntr=0.3,0.1

Type RM Length L Ch R = 1 ,9351.284,61.37,60.5,62.83
XS GIS Cut Line= 2
1574695.40622576701038.4123064581574353.36119267701156.463247061
#Sta/Elev= 30
       0  252.07   14.81  249.01   22.22  247.03   29.62  245.29   44.43  244.04
   74.05  242.69   85.29  241.93   88.86  241.66   96.27  240.67  103.67  240.87
  111.08   241.9  133.29  243.89   148.1  244.32  192.53  244.85  199.94  245.39
  207.35  245.66  222.16  245.72  244.37  246.59  259.18  246.24  266.59  246.28
  273.99  246.56   281.4  247.36  303.61  250.38  318.42  252.86  325.83  254.33
  333.23  256.11  340.64  258.28  348.04  261.35  355.45     265  361.84  268.52
#Mann= 3 , 0 , 0
       0      .1       0   85.29    .045       0  111.08      .1       0
Bank Sta=85.29,111.08
XS Rating Curve= 0 ,0
Exp/Cntr=0.3,0.1

Type RM Length L Ch R = 1 ,9290.781,55.02,51.61,44.53
XS GIS Cut Line= 3
1574660.26842973700984.5069572631574432.95479269701069.926056907
1574335.53466256701101.693490639
#Sta/Elev= 30
       0  250.63   22.43  242.82   29.91  241.92   59.82  241.18   77.07   239.7
   89.73  238.43   97.21  238.66  104.69   239.6  112.17  240.25  127.12     241
   134.6  241.21  142.08  241.13  157.04  241.89  171.99   242.2  179.47  242.57
  186.95  242.42  194.43  241.93   201.9  241.97  216.86   242.5  224.34  243.22
   250.2  244.31  257.56  245.27  272.28  248.35  279.65  249.55  294.37  251.38
   309.1  253.57  316.46  254.84  323.82  257.19  338.55  263.06   345.3  266.54
#Mann= 3 , 0 , 0
       0      .1       0   77.07    .045       0  104.69      .1       0
Bank Sta=77.07,104.69
XS Rating Curve= 0 ,0
Exp/Cntr=0.3,0.1

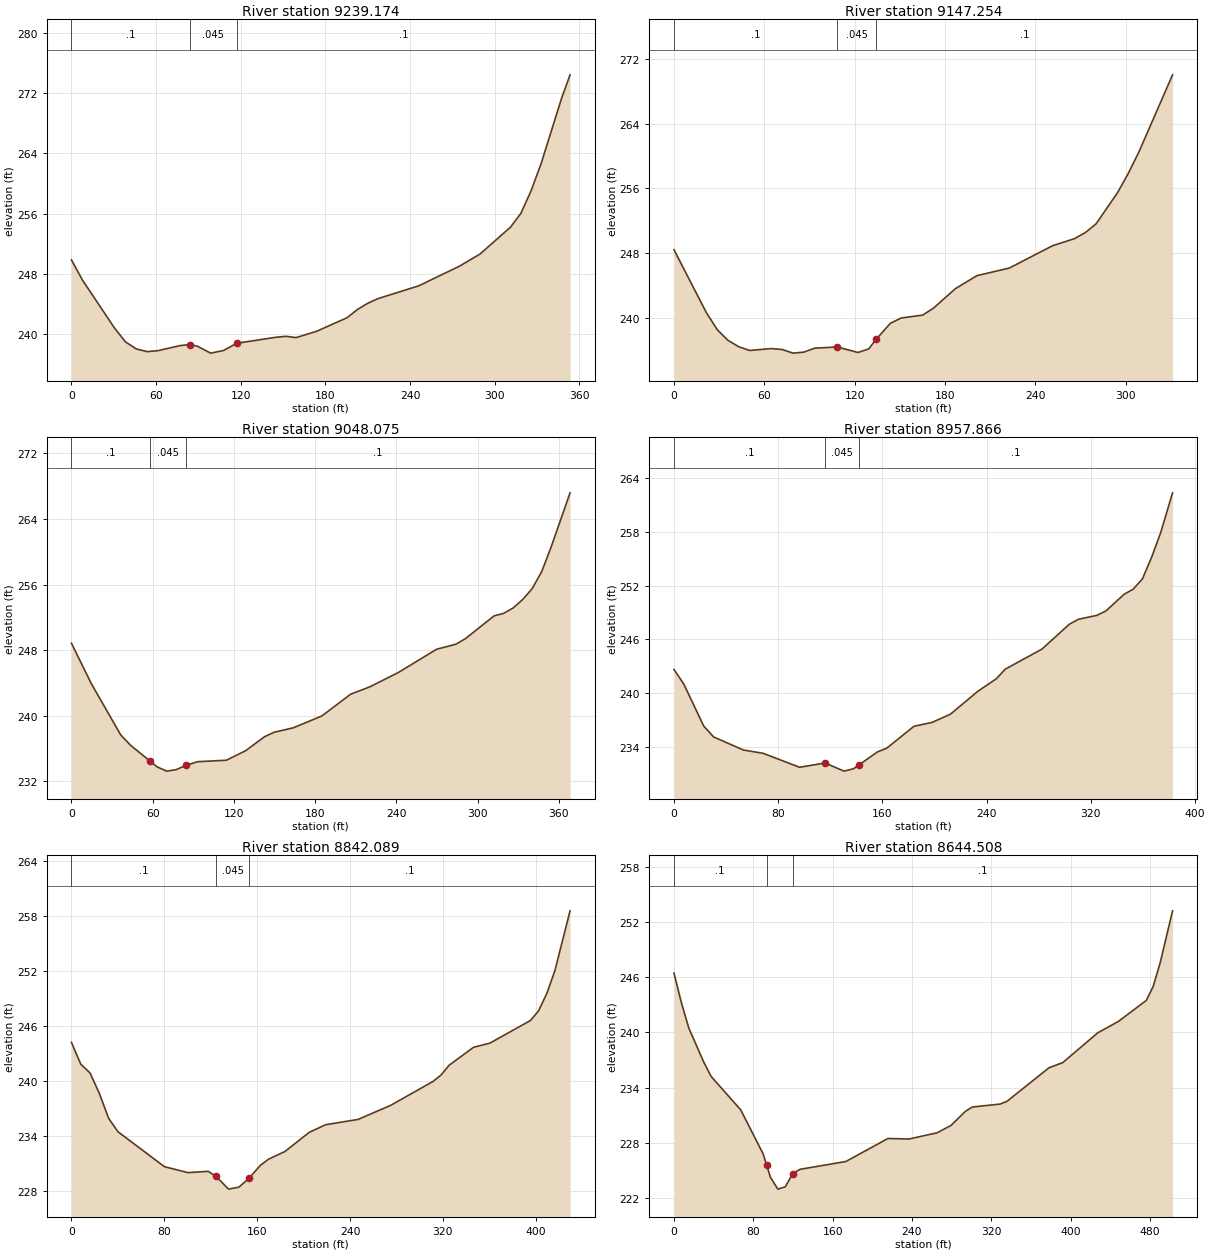
Type RM Length L Ch R = 1 ,9239.174,69.93,91.92,93.71
XS GIS Cut Line= 4
1574632.73595804700933.7885778251574551.17299996700970.309305325
1574525.60849066700992.221741855 1574302.8320529701050.654905856
#Sta/Elev= 30
       0  249.85    7.67  247.21   30.68  240.77   38.35  238.97   46.02  238.04
   53.69  237.69   61.36  237.82    76.7  238.48   83.78238.6283   89.37   238.4
   98.59  237.49  107.81  237.84  117.02  238.79  144.75  239.59  151.98  239.72
  159.22  239.55  173.69  240.38   195.4  242.19  202.64  243.27  209.88  244.09
  217.11  244.71  246.06  246.41  275.01  249.02  289.48  250.62  311.19   254.2
  318.43     256  325.67  258.98   332.9  262.65  347.38   271.3  353.35  274.39
#Mann= 3 , 0 , 0
       0      .1       0   83.78    .045       0  117.02      .1       0
Bank Sta=83.78,117.02
XS Rating Curve= 0 ,0
Exp/Cntr=0.3,0.1

Type RM Length L Ch R = 1 ,9147.254,75.68,99.18,91.89
XS GIS Cut Line= 2
1574601.67516303700884.2630552351574279.05922478700958.387067303
#Sta/Elev= 30
       0  248.43   21.55  240.65   28.73  238.56   35.91  237.23   43.09  236.44
   50.28  235.99   64.64  236.22   71.82  236.11   79.01  235.66   86.19  235.78
   93.37  236.27  108.44  236.42   122.1  235.74  129.28  236.18  134.43  237.41
  143.65  239.34  150.83     240  165.19  240.36  172.38  241.23  186.74  243.61
  201.11  245.23  222.65  246.17  251.38  248.93  265.75  249.79  272.93  250.53
  280.11   251.6  294.48  255.48  301.66  257.87  308.84  260.58  331.02  270.04
#Mann= 3 , 0 , 0
       0      .1       0  108.44    .045       0  134.43      .1       0
Bank Sta=108.44,134.43
XS Rating Curve= 0 ,0
Exp/Cntr=0.3,0.1

Type RM Length L Ch R = 1 ,9048.075,74.85,90.21,80.82
XS GIS Cut Line= 4
1574591.34580022700835.1826135671574543.86885446700821.791680142
1574500.04398142700824.2263953091574227.35588272700859.529765233
#Sta/Elev= 30
       0  248.84   14.55  243.95   36.37  237.67   43.64   236.4    58.1234.4643
   63.35  233.76   70.36  233.25   77.37  233.43   84.38  233.95   93.22   234.4
   114.4  234.58  128.51  235.73  142.63  237.45  149.69  237.99  163.81  238.53
  184.98  239.98  206.16  242.63  220.27  243.52  241.45  245.28  269.68  248.11
   283.8  248.72  290.86  249.39  312.03  252.17  319.09  252.48  326.15  253.14
  333.21  254.17  340.27  255.51  347.32   257.6  354.38  260.65  368.19  267.18
#Mann= 3 , 0 , 0
       0      .1       0    58.1    .045       0   84.38      .1       0
Bank Sta=58.1,84.38
XS Rating Curve= 0 ,0
Exp/Cntr=0.3,0.1

Type RM Length L Ch R = 1 ,8957.866,67.25,115.78,120.85
XS GIS Cut Line= 5
1574604.59780985700778.0948476791574528.92412996700745.807410926
1574495.62771085700740.7624989451574470.40315089700747.825375721
1574230.26534005700761.951129317
#Sta/Elev= 30
       0  242.63    7.61  240.98   22.83  236.31   30.44  235.09   53.27  233.63
   68.49  233.26   96.43   231.7  115.95  232.18  130.49  231.27  137.76  231.53
  142.14  231.98  156.17  233.42  163.18  233.82  184.22  236.28  198.24  236.72
  212.27  237.64   233.3   240.2  247.33  241.58  254.34  242.67  282.39   244.9
  303.42  247.68  310.44  248.24  324.46  248.67  331.47  249.16   345.5  251.03
  352.51  251.61  359.52  252.74  366.53  255.13  373.54   257.9   382.7  262.37
#Mann= 3 , 0 , 0
       0      .1       0  115.95    .045       0  142.14      .1       0
Bank Sta=115.95,142.14
XS Rating Curve= 0 ,0
Exp/Cntr=0.3,0.1

Type RM Length L Ch R = 1 ,8842.089,173.59,197.58,135.68
XS GIS Cut Line= 5
1574643.69217633700734.1419341121574556.04243031700685.447630763
1574506.13076937700647.7095456721574385.61236858700642.840115353
1574239.52945857700646.492188111
#Sta/Elev= 30
       0   244.2    8.01  241.83   16.02  240.87   24.02  238.64   32.03  235.92
   40.04  234.46   80.08  230.65  100.27     230  117.82  230.14  124.54229.5916
  135.37   228.2  144.15  228.41  152.92  229.37  162.84   230.8  169.85  231.47
  183.86   232.3  204.87  234.39  218.89  235.22  246.91   235.8  274.93  237.33
  311.47  239.94  318.47  240.65  325.47  241.72  346.48  243.67  360.48  244.12
  395.49  246.59  402.49  247.65   409.5  249.52   416.5  252.01  429.59  258.55
#Mann= 3 , 0 , 0
       0      .1       0  124.54    .045       0  152.92      .1       0
Bank Sta=124.54,152.92
XS Rating Curve= 0 ,0
Exp/Cntr=0.3,0.1

Type RM Length L Ch R = 1 ,8644.508,200.62,217.76,154.91
XS GIS Cut Line= 4
1574744.73285575 700601.449957521574615.69295186700552.755654156
1574468.39268428700530.8432176411574252.92039196700544.234151065
#Sta/Elev= 30
       0  246.47    7.48  243.25   14.96  240.48   29.93   236.8   37.41  235.22
   67.34  231.56   89.78   226.8   93.31  225.59   97.26  224.22  104.75  222.93
  112.23  223.18  119.71  224.63  127.19  225.09  173.31  225.94  215.77  228.45
     237  228.39  265.31  229.07  279.46  229.88  293.86  231.41  300.87  231.88
  328.92   232.2  335.94  232.51  378.02  236.15  392.05  236.72  427.11  239.95
  448.15  241.21  476.21  243.49  483.22  245.02  490.24   247.6  502.73  253.26
#Mann= 3 , 0 , 0
       0      .1       0   93.31    .045       0  119.71      .1       0
Bank Sta=93.31,119.71
XS Rating Curve= 0 ,0
Exp/Cntr=0.3,0.1

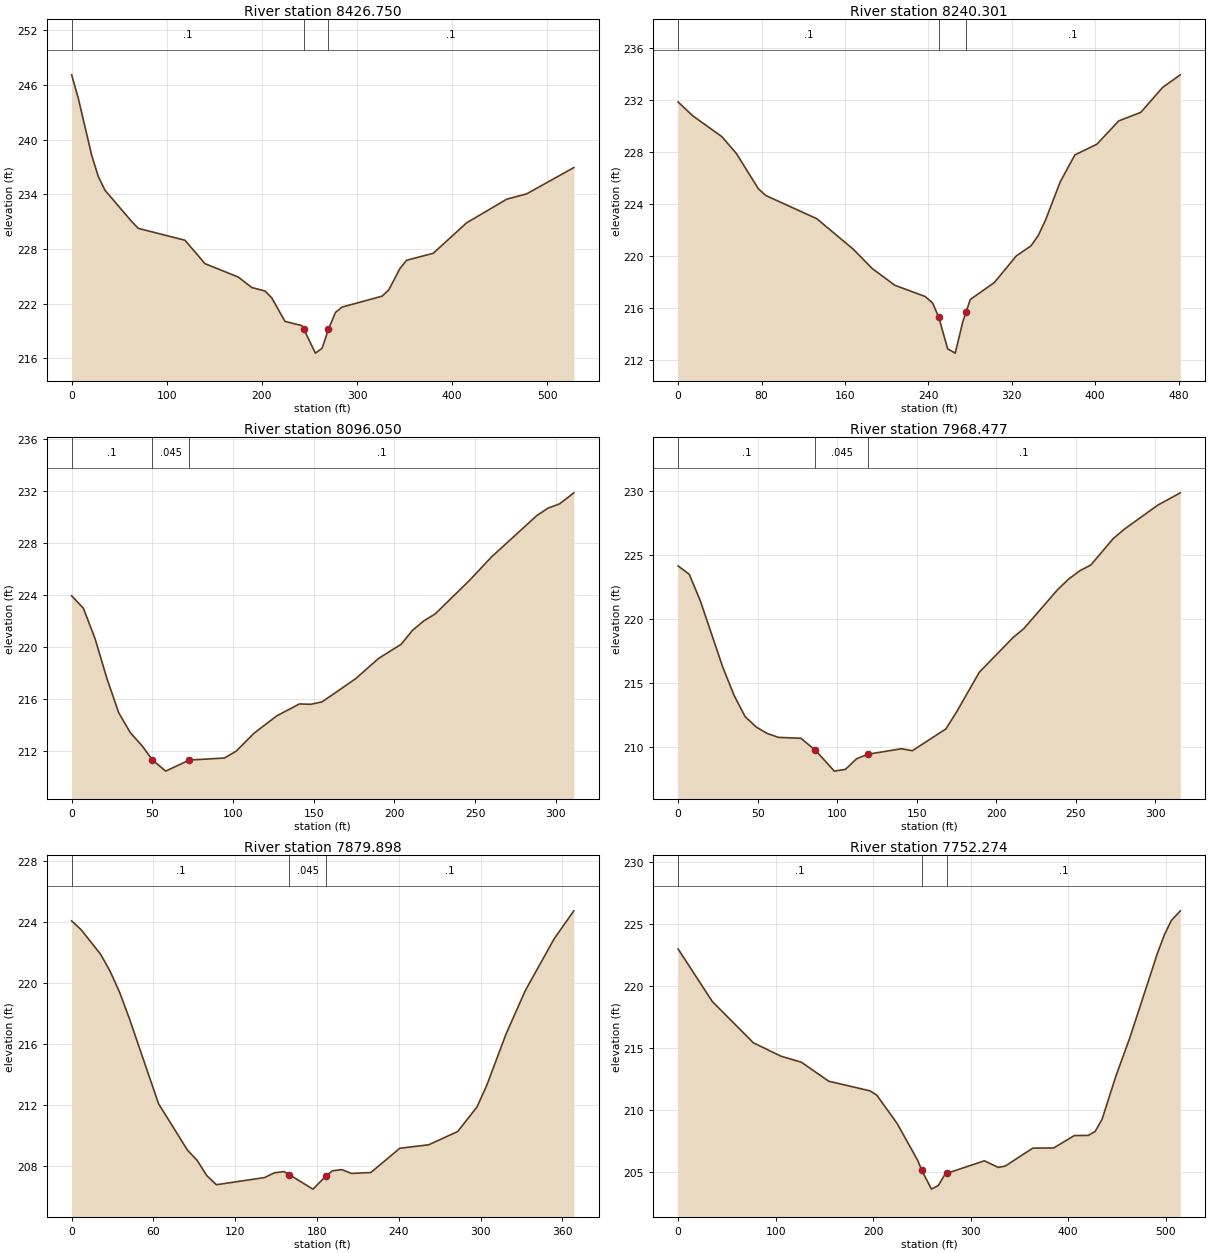
Type RM Length L Ch R = 1 ,8426.750,182.69,186.45,163.52
XS GIS Cut Line= 4
1574839.88692941700393.8806662261574605.01823972700406.285702646
1574502.46993862700413.7287245241574313.08638257700427.787765801
#Sta/Elev= 30
       0   247.1    7.01  244.52   21.03  238.29   28.04  235.94   35.05  234.44
   63.09  231.02    70.1  230.26  119.17  228.96   140.2  226.39  175.24  224.92
  189.26  223.78  203.28  223.39  210.29  222.65  224.31  220.06  242.21  219.59
  243.85 219.248  256.25  216.58  263.27  217.11  269.98219.2058  277.31  221.04
  284.32  221.63  326.44  222.83  333.45  223.53  345.03  225.84  352.05  226.76
  380.13  227.53  415.23  230.87  457.34  233.46   478.4  234.05  527.92  236.93
#Mann= 3 , 0 , 0
       0      .1       0  243.85    .045       0  269.98      .1       0
Bank Sta=243.85,269.98
XS Rating Curve= 0 ,0
Exp/Cntr=0.3,0.1

Type RM Length L Ch R = 1 ,8240.301,141.33,144.25,133.68
XS GIS Cut Line= 4
1574787.78577642700238.4042097181574601.71023004700244.193226695
1574488.41089737700273.9653141351574310.60537525700288.024355397
#Sta/Elev= 30
       0  231.88   14.01  230.82   42.02  229.21   56.03   227.9   77.04   225.2
   84.04  224.69  133.06   222.9  168.08  220.55  186.17  219.07  207.88  217.78
  236.83  216.92  244.07  216.42  249.99215.3186  258.54  212.89  265.78  212.56
  273.02  214.96  276.14215.7068  280.25  216.69  303.31  217.99  324.38  220.04
  338.42  220.81  345.44  221.61  352.46  222.81  366.51  225.74  380.55  227.81
  401.62  228.63  422.68  230.43  443.75  231.08  464.81  233.01  481.67  233.97
#Mann= 3 , 0 , 0
       0      .1       0  249.99    .045       0  276.14      .1       0
Bank Sta=249.99,276.14
XS Rating Curve= 0 ,0
Exp/Cntr=0.3,0.1

Type RM Length L Ch R = 1 ,8096.050,115.47,127.57,137.19
XS GIS Cut Line= 3
1574607.62475707 700106.112570391574505.71753483700135.373059928
1574300.89410798700145.462883919
#Sta/Elev= 30
       0  223.95    7.28  222.99   14.57  220.63   21.85  217.59   29.13  214.96
   36.41  213.41    43.7   212.4   49.95  211.33   58.26  210.46   72.83  211.31
   94.68  211.47  101.96     212  113.03  213.38  127.05  214.71  141.07  215.63
  148.08   215.6  155.08  215.79  162.09  216.38  176.11  217.59  190.13  219.13
  204.14  220.22  211.15  221.29  218.16  222.02  225.17  222.55  246.19   225.1
  260.21  226.95  288.25  230.13  295.25   230.7  302.26  231.02   311.1  231.87
#Mann= 3 , 0 , 0
       0      .1       0   49.95    .045       0   72.83      .1       0
Bank Sta=49.95,72.83
XS Rating Curve= 0 ,0
Exp/Cntr=0.3,0.1

Type RM Length L Ch R = 1 ,7968.477,95.22,88.58,90.93
XS GIS Cut Line= 2
1574604.19123732700012.6325467681574289.10331212699991.130483642
#Sta/Elev= 30
       0  224.16    7.02  223.51   14.03  221.41   28.07  216.25   35.08  214.07
    42.1  212.38   49.11  211.56   56.13  211.05   63.15  210.75   77.18  210.68
   86.38  209.74   98.23  208.11  105.24  208.25  112.26  209.08  119.28  209.43
  140.33  209.86  147.34  209.71  168.39  211.41  175.41   212.8  189.44  215.85
  210.49  218.54   217.5  219.27  238.55  222.29  245.57  223.13  252.59  223.78
   259.6  224.24  273.63   226.3  280.65  227.04   301.7  228.92  315.82  229.88
#Mann= 3 , 0 , 0
       0      .1       0   86.38    .045       0  119.28      .1       0
Bank Sta=86.38,119.28
XS Rating Curve= 0 ,0
Exp/Cntr=0.3,0.1

Type RM Length L Ch R = 1 ,7879.898,84.95,127.62,80.55
XS GIS Cut Line= 2
1574688.34334894699944.6753866521574324.10070312699889.181354746
#Sta/Elev= 30
       0   224.1    7.08  223.51   21.24  221.91   28.32  220.78    35.4  219.37
   42.48  217.66   63.73  212.11   84.97  209.06   92.05  208.39   99.13  207.39
  106.21  206.79  141.62  207.26   148.7  207.57  155.78  207.65  159.83207.4412
  177.02   206.5  186.32  207.33  191.18   207.7  198.26  207.78  205.34  207.53
   219.5  207.59  240.75  209.18  261.99  209.41  283.23  210.28  297.39  211.89
  304.47  213.29  318.63  216.66   332.8  219.52  354.04  222.93  368.45  224.76
#Mann= 3 , 0 , 0
       0      .1       0  159.83    .045       0  186.32      .1       0
Bank Sta=159.83,186.32
XS Rating Curve= 0 ,0
Exp/Cntr=0.3,0.1

Type RM Length L Ch R = 1 ,7752.274,101.3,116.83,93.9
XS GIS Cut Line= 3
1574856.42697798699871.2151315211574550.43607946699847.232061103
1574345.33947726699812.497959122
#Sta/Elev= 30
       0  222.98   35.11  218.75   77.24  215.43  105.32  214.36  126.39  213.87
  154.47  212.34   196.6  211.57  203.62  211.23  224.69  208.93  245.75  205.96
   249.8205.1801  259.79  203.66  266.82  203.95  273.84  204.88  275.81204.9368
  314.03  205.94  328.23  205.41  335.33  205.51  363.73  206.96  385.03  206.97
  406.32  207.97  420.52  207.98  427.62   208.3  434.72  209.28  448.92  212.76
  463.12  215.82  491.52  222.64  498.62  224.12  505.72  225.27  514.95  226.05
#Mann= 3 , 0 , 0
       0      .1       0   249.8    .045       0  275.81      .1       0
Bank Sta=249.8,275.81
XS Rating Curve= 0 ,0
Exp/Cntr=0.3,0.1

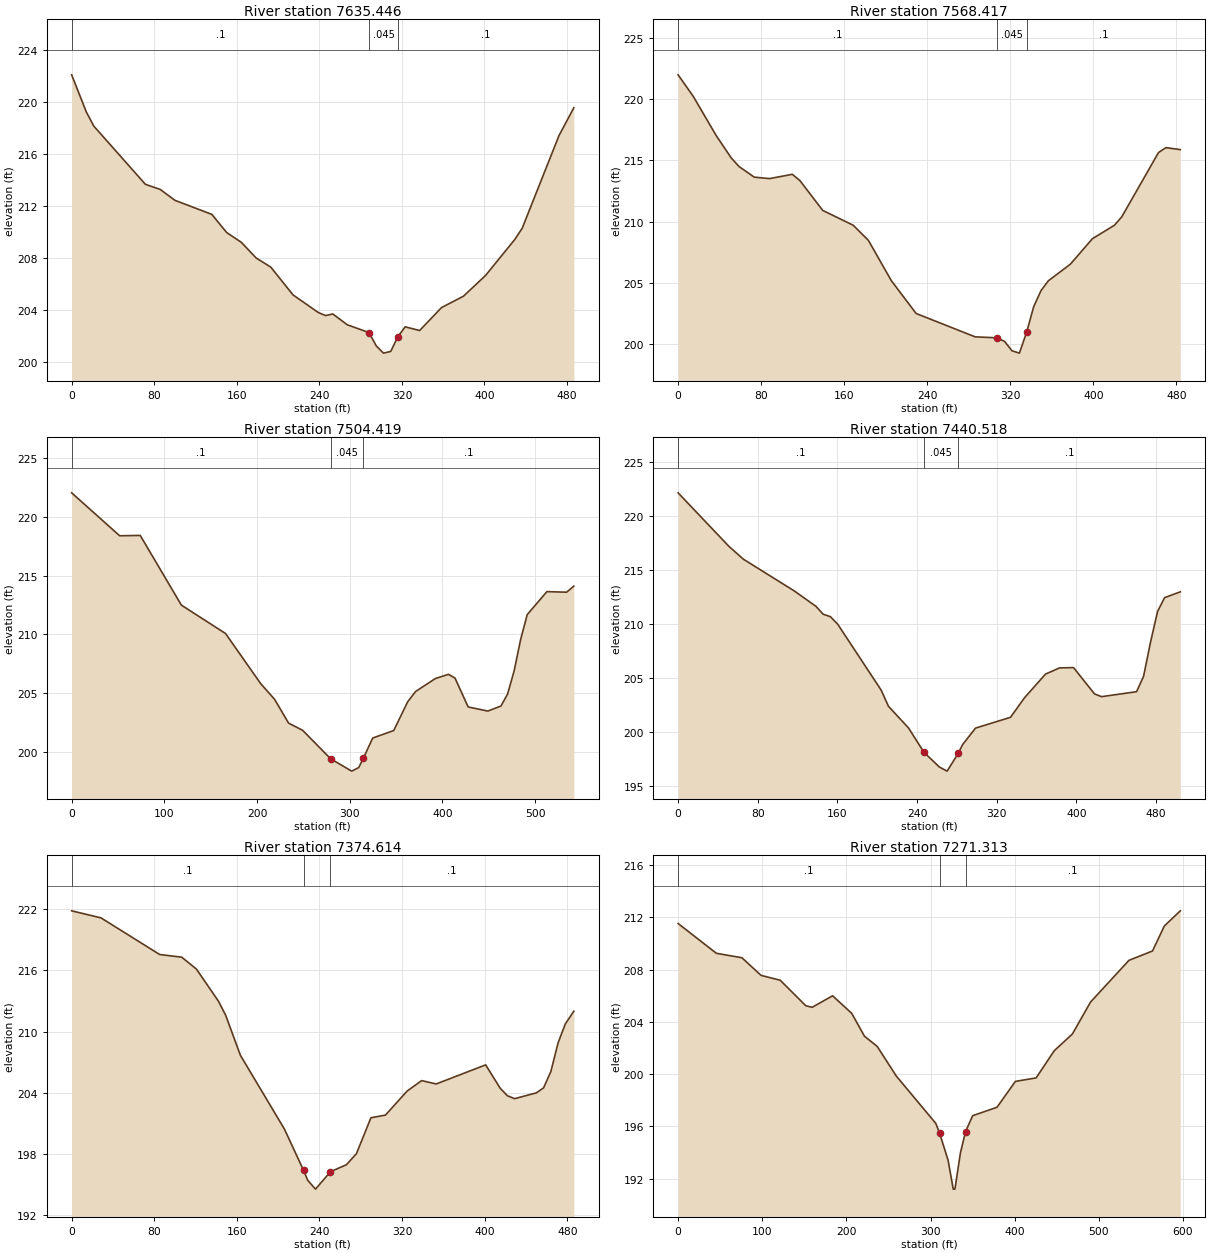
Type RM Length L Ch R = 1 ,7635.446,59.83,67.03,67.8
XS GIS Cut Line= 4
1574865.92425101699804.4268332721574631.84033462699755.995678142
1574519.84328839699749.9417837711574386.65761185699725.726206213
#Sta/Elev= 30
       0  222.12    14.3  219.25   21.44  218.18   71.48   213.7   85.78  213.31
  100.08  212.47  135.82  211.39  150.11     210  164.41  209.24  178.71  208.04
     193  207.33  214.45   205.2  239.04  203.84  246.05  203.61  253.06  203.73
  267.08   202.9  288.11   202.3  295.12  201.28  302.13  200.72  309.14  200.85
  316.15  201.99  323.16  202.74  337.18  202.46  358.32  204.22  379.66   205.1
  401.01  206.69  429.46  209.47  436.58  210.33  472.15  217.44  486.57  219.59
#Mann= 3 , 0 , 0
       0      .1       0  288.11    .045       0  316.15      .1       0
Bank Sta=288.11,316.15
XS Rating Curve= 0 ,0
Exp/Cntr=0.3,0.1

Type RM Length L Ch R = 1 ,7568.417,49.98,64,62.85
XS GIS Cut Line= 4
1574868.52160646699771.6969312731574649.67928512699703.220462978
1574538.14029552 699683.454059751574398.36358708699662.981713578
#Sta/Elev= 30
       0     222   14.67  220.23   36.67  217.04   51.34  215.19   58.68  214.51
   73.35  213.64   88.02  213.52  110.02  213.87  117.35  213.36  139.36  210.92
   168.7  209.71  183.37  208.47  205.37  205.19  229.31   202.5  286.18  200.59
  307.51  200.51  314.61  200.21  321.72  199.45  328.83  199.26  335.94  201.01
  342.58  203.05  349.66  204.37  356.73  205.17  377.96  206.53  399.18  208.61
   420.4  209.71  427.48   210.4  462.85  215.65  469.93  216.05  483.85  215.89
#Mann= 3 , 0 , 0
       0      .1       0  307.51    .045       0  335.94      .1       0
Bank Sta=307.51,335.94
XS Rating Curve= 0 ,0
Exp/Cntr=0.3,0.1

Type RM Length L Ch R = 1 ,7504.419,61.55,63.9,64.81
XS GIS Cut Line= 4
1574872.14002408699742.2027526941574736.51162583699695.890616715
 1574525.6260066699609.8823641841574356.91751127699584.245288894
#Sta/Elev= 30
       0  222.05   51.78  218.39   73.97  218.42  118.35  212.48     166  210.06
   203.8   205.8  218.92  204.45  234.04  202.42  249.15  201.81  279.39  199.38
  302.07  198.33  309.63  198.63  314.56  199.41  324.75  201.15  347.43  201.79
  362.55  204.25  371.07  205.12  392.31  206.22  406.47  206.58  413.55  206.26
  427.71   203.8  448.95  203.45  463.11  203.88  470.19  204.89  477.27  206.86
  484.35  209.56  491.43  211.67  512.67  213.63  533.92  213.58  541.71   214.1
#Mann= 3 , 0 , 0
       0      .1       0  279.39    .045       0  314.56      .1       0
Bank Sta=279.39,314.56
XS Rating Curve= 0 ,0
Exp/Cntr=0.3,0.1

Type RM Length L Ch R = 1 ,7440.518,67.52,65.9,63.51
XS GIS Cut Line= 4
1574876.28697915699663.6876565521574668.73974536699603.682503909
1574593.90979035699568.3853553091574389.18632843699547.913009122
#Sta/Elev= 30
       0  222.13   51.01  217.18   65.58  215.99  116.59  213.06  138.45  211.63
  145.73   210.9  153.02  210.67  160.31  209.98  204.03  203.87  211.31  202.38
  231.53  200.37  247.01  198.12  262.49  196.76  270.23  196.38  281.68  198.06
   285.7  198.82  298.78  200.36  333.96  201.36  348.03  203.17  369.13  205.36
   383.2  205.93  397.27  205.96  418.38  203.52  425.41  203.27  460.59  203.73
  467.62  205.15  474.66  208.33  481.69  211.15  488.73  212.43  504.53  212.97
#Mann= 3 , 0 , 0
       0      .1       0  247.01    .045       0  281.68      .1       0
Bank Sta=247.01,281.68
XS Rating Curve= 0 ,0
Exp/Cntr=0.3,0.1

Type RM Length L Ch R = 1 ,7374.614,122.1,103.3,79.49
XS GIS Cut Line= 5
1574884.54506052699577.6292694961574718.31757244699548.684184477
1574618.25027862699510.6420727821574507.43195322699518.912097067
1574408.19166179 699513.12308006
#Sta/Elev= 30
       0  221.84   28.42  221.15   85.26  217.56  106.58   217.3  120.79  216.14
  142.11     213  149.21   211.6  163.42  207.69  206.17  200.44  224.58196.4192
  228.64  195.44  236.13  194.58  250.65196.2819  266.08  196.97  275.78  198.05
  289.82  201.57  303.86  201.83  324.92  204.19  338.96  205.21     353  204.88
  400.93  206.75  414.96  204.47  421.97  203.73  428.98  203.44  450.02  204.01
  457.03   204.5  464.04  206.09  471.05   208.9  478.06  210.76  486.32  212.01
#Mann= 3 , 0 , 0
       0      .1       0  224.58    .045       0  250.65      .1       0
Bank Sta=224.58,250.65
XS Rating Curve= 0 ,0
Exp/Cntr=0.5,0.3

Type RM Length L Ch R = 1 ,7271.313,71.97,72.95,74.73
BEGIN DESCRIPTION:
Channel bottom lowered to meet culvert invert based on study assumption that any deposition in culvert will be removed by flow prior to peak of a 100-yr flood event.  The bridge/culvert survey photos show channel invert above culvert invert at upstream end of culvert.
END DESCRIPTION:
XS GIS Cut Line= 6
1574990.18529671699306.0496599821574727.68382356699415.307622552
1574651.00617369699438.3787738381574592.25698766699455.260723844
1574505.30960031699475.2724240871574423.33764906 699480.07011354
#Sta/Elev= 30
       0  211.52   45.52  209.24   75.87   208.9   98.63  207.55  121.39  207.18
  151.74  205.23  159.32  205.11  183.59  205.99  206.31  204.65  221.45   202.9
   236.6  202.12  259.32  199.85  306.26  196.23  310.85195.4679  320.88  193.41
     327   191.2     329   191.2   335.5  193.96  341.59195.6015  350.12  196.82
  378.97  197.46  400.82  199.44  425.53  199.71  447.08  201.79  468.63  203.07
  490.18  205.51  535.79   208.7  563.84  209.42  577.86  211.33  596.86  212.49
#Mann= 3 , 0 , 0
       0      .1       0  310.85    .045       0  341.59      .1       0
Bank Sta=310.85,341.59
XS Rating Curve= 0 ,0
Exp/Cntr=0.5,0.3