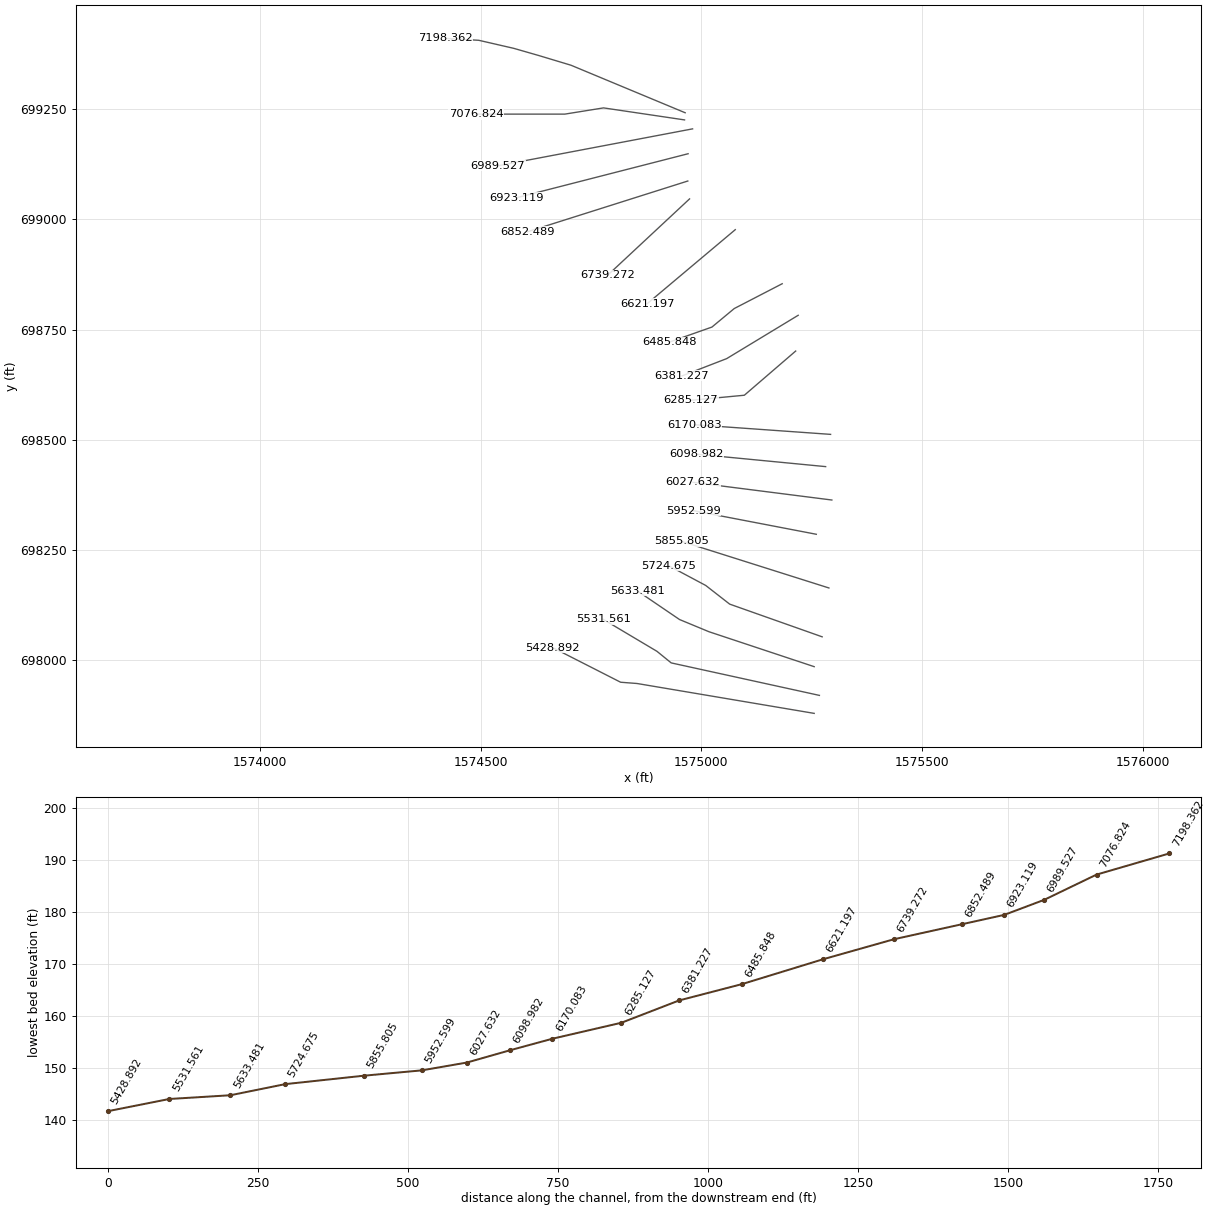
HEC-RAS study SusquehannaRiverTrib.prj: SusquehannaRiverTrib

--- SusquehannaRiverTrib.g01 (geometry) --- (continued)

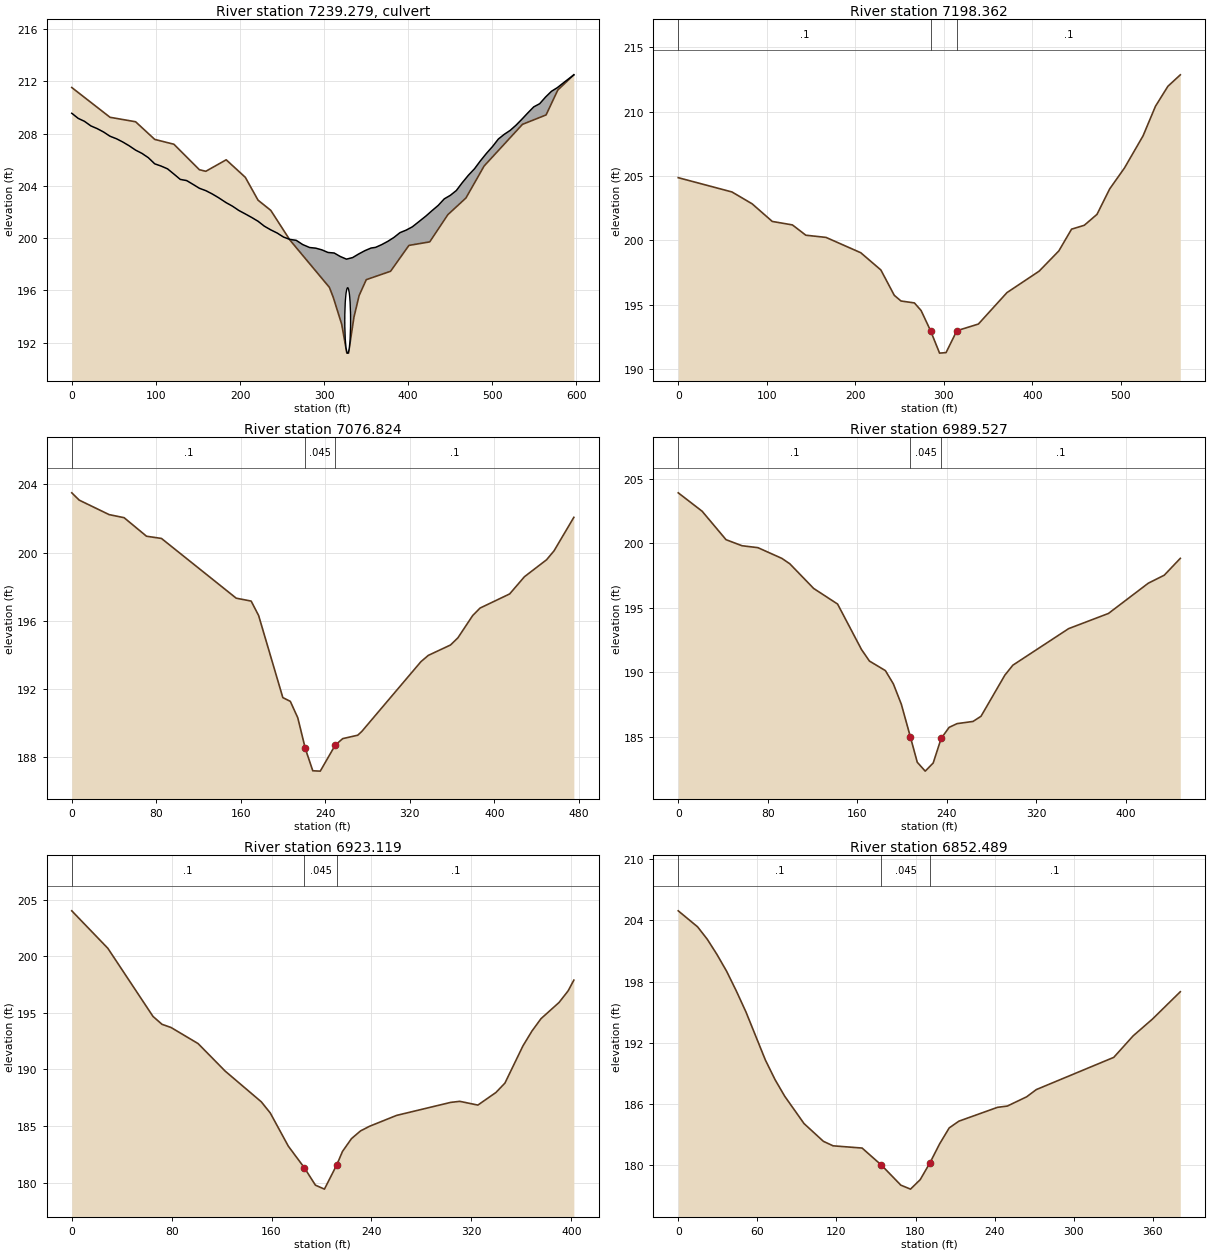
Type RM Length L Ch R = 2 ,7239.279,,,
BEGIN DESCRIPTION:
St. Mark's Church Road
MDE Bridge #: CE033108FS-1
Top of road obtained from DEM.
Opening estimated from MDE2 bridge/culvert surveys photos and limited structure data (culvert size and invert were not provided).
END DESCRIPTION:
Bridge Culvert--1,0,-1,-1, 0
Deck Dist Width WeirC Skew NumUp NumDn MinLoCord MaxHiCord MaxSubmerge Is_Ogee
22.5,28,2.6,0, 81, 78, , , 0.95, 0, 2,2,,
       0    7.59   15.17   22.76   30.35   37.93   45.52   53.11   60.69   68.28
   75.87   83.46   91.04   98.63  106.22   113.8  121.39  128.98  136.56  144.15
  151.74  159.32  166.91   174.5  183.52   191.1  198.67  206.24  213.82  221.39
  228.96  236.54  244.11  251.69  259.26  266.83  274.41  282.71  290.02  297.33
  304.64  311.95  319.26  326.57  333.88  341.19   348.5  355.81  361.11  368.39
  375.67  382.96  390.24  397.52  404.81  412.09  421.24  428.43  435.61  442.79
  449.97  457.16  464.34  471.52  478.71  485.89  493.07  500.26  507.14  514.15
  521.16  528.17  535.18   542.2  549.21  556.22  563.23  570.24  577.26  586.73
  596.86
  209.55  209.16  208.93  208.58  208.37  208.11  207.79   207.6  207.35  207.06
  206.73  206.48  206.15  205.68  205.51   205.3   204.9  204.49   204.4  204.11
  203.81  203.63  203.38  203.09  202.71  202.44  202.11  201.85  201.58  201.29
  200.91  200.63  200.39  200.08   199.9  199.83  199.51  199.28  199.23   199.1
   198.9  198.86  198.59  198.39  198.51  198.79  199.04  199.24  199.29   199.5
  199.75  200.05  200.42  200.61  200.86  201.23   201.7  202.11   202.5     203
  203.27  203.64  204.25  204.81   205.3  205.92  206.49  207.01  207.58  207.94
  208.24  208.64   209.1  209.58  210.04  210.28  210.79  211.23  211.51  211.99
  212.49
                                                                                
                                                                                
                                                                                
                                                                                
                                                                                
                                                                                
                                                                                
                                                                                
        
       0    7.59   15.17   22.76   30.35   37.93   45.52   53.11   60.69   68.28
   75.87   83.46   91.04   98.63  106.22   113.8  121.39  128.98  136.56  144.15
  151.74  159.32  166.91   174.5  183.52   191.1  198.67  206.24  213.82  221.39
  228.96  236.54  244.11  251.69  259.26  266.83  274.41  282.71  290.02  297.33
  304.64  311.95  319.26  326.57  333.88  341.19   348.5  355.81  361.11  368.39
  375.67  382.96  390.24  397.52  404.81  412.09  421.24  428.43  435.61  442.79
  449.97  457.16  464.34  471.52  478.71  485.89  493.07  500.26  507.14  514.15
  521.16  528.17  535.18   542.2  549.21  556.22  563.23   567.1
  209.55  209.16  208.93  208.58  208.37  208.11  207.79   207.6  207.35  207.06
  206.73  206.48  206.15  205.68  205.51   205.3   204.9  204.49   204.4  204.11
  203.81  203.63  203.38  203.09  202.71  202.44  202.11  201.85  201.58  201.29
  200.91  200.63  200.39  200.08   199.9  199.83  199.51  199.28  199.23   199.1
   198.9  198.86  198.59  198.39  198.51  198.79  199.04  199.24  199.29   199.5
  199.75  200.05  200.42  200.61  200.86  201.23   201.7  202.11   202.5     203
  203.27  203.64  204.25  204.81   205.3  205.92  206.49  207.01  207.58  207.94
  208.24  208.64   209.1  209.58  210.04  210.28  210.79  211.23
                                                                                
                                                                                
                                                                                
                                                                                
                                                                                
                                                                                
                                                                                
                                                                
BR Coef=-1 , 0 , 0 ,, 0 ,,,0.8,0,,0,
WSPro=,,,, 1 ,,,, 0 ,,,, 0 ,,,,-1 ,-1 ,-1 , 0 , 0 , 0 , 0 , 0
Culvert=3,5,6.88,34,0.024,0.5,1,34,1,191.2,328,191.2,300,Culvert #1  , 0 ,19.5
Culvert Bottom n=0.024
BC Design=,, 0 ,, 0 ,,,,,,
BC Use User HTab Curves=0
BC User HTab FreeFlow(D)= 0

Type RM Length L Ch R = 1 ,7198.362,109.37,121.54,131.73
BEGIN DESCRIPTION:
Channel bottom center lowered 0.5 ft based on bridge survey info
END DESCRIPTION:
XS GIS Cut Line= 6
1574963.19085057699241.4640588161574704.17978854699349.279663131
1574631.25472885699371.2217165081574574.72779469699387.465088367
1574495.34434618699405.7358820591574419.24765839699410.189701572
#Sta/Elev= 30
       0  204.86   60.69  203.75   83.46  202.83  106.22  201.46  128.98  201.19
  144.15  200.39  166.91  200.22  206.16  199.03  228.88  197.69  244.03  195.72
   251.6  195.28  266.75  195.13  274.32  194.54  284.95  192.98  295.18  191.23
  302.49  191.27  314.69192.9691  339.04  193.49  371.28  195.93  407.69   197.6
  429.89  199.17  444.26  200.86  458.62  201.16  472.99  202.01  487.35  203.99
     504  205.61  525.03  208.11  539.05  210.41  553.08  211.96   567.1  212.85
#Mann= 3 , 0 , 0
       0      .1       0  284.95    .045       0  314.69      .1       0
Bank Sta=284.95,314.69
XS Rating Curve= 0 ,0
Exp/Cntr=0.5,0.3

Type RM Length L Ch R = 1 ,7076.824,87.48,87.3,89.28
XS GIS Cut Line= 4
1574961.77757891699225.2709366231574778.14278239699252.513461366
 1574690.3613137699238.3877077851574489.57381645699238.387707785
#Sta/Elev= 30
       0  203.51    7.08  203.08   35.38  202.23   49.54  202.05   70.77  200.96
   84.92  200.83  155.69  197.32  169.84  197.15  176.92   196.3  199.82  191.48
  206.91  191.26     214  190.29  221.09  188.49  228.18  187.18  235.27  187.16
  249.46  188.69  256.55  189.07  270.73  189.27  274.56  189.49  330.56  193.59
  337.56  193.96  358.56  194.57  365.56  194.99  379.56   196.3  386.56  196.74
  414.56  197.57  428.56  198.58  449.56  199.58  456.56   200.1  475.34  202.07
#Mann= 3 , 0 , 0
       0      .1       0  221.09    .045       0  249.46      .1       0
Bank Sta=221.09,249.46
XS Rating Curve= 0 ,0
Exp/Cntr=0.3,0.1

Type RM Length L Ch R = 1 ,6989.527,65.74,66.41,68.85
XS GIS Cut Line= 2
1574980.02138954699204.9832462821574538.90564103699121.277547002
#Sta/Elev= 30
       0  203.93   21.37   202.5   42.75  200.29      57  199.82   71.25  199.67
   92.62  198.84   99.75  198.42  121.12   196.5   142.5  195.29  163.87  191.76
     171  190.86  185.25  190.12  192.37  189.09   199.5  187.51  207.57  184.98
  213.75     183  220.87  182.31     228  182.94  235.12  184.85  242.25  185.71
  249.37     186  263.62  186.17  270.75  186.57  292.12  189.77  299.25  190.54
  349.12  193.38  384.75  194.56  420.37  196.91  434.62  197.53  448.99  198.84
#Mann= 3 , 0 , 0
       0      .1       0  207.57    .045       0  235.12      .1       0
Bank Sta=207.57,235.12
XS Rating Curve= 0 ,0
Exp/Cntr=0.3,0.1

Type RM Length L Ch R = 1 ,6923.119,68.35,70.63,71.09
XS GIS Cut Line= 2
1574969.84943807 699148.588274361574580.38223229699048.699016914
#Sta/Elev= 30
       0     204   28.91  200.69   65.04  194.68   72.27  193.98   79.49   193.7
  101.17  192.28  122.85  189.85  151.76  187.14  158.98  186.15  173.44  183.22
  186.32  181.31  195.12  179.78  202.34  179.43  212.33   181.6   216.8  182.76
  224.02  183.89  231.25  184.57  238.48  184.98  260.16  185.94  303.52  187.09
  310.74  187.18   325.2  186.85  339.65  187.96  346.88  188.79  361.33  192.08
  368.55  193.39  375.78  194.48  390.23  195.91  397.46  196.93  402.07  197.88
#Mann= 3 , 0 , 0
       0      .1       0  186.32    .045       0  212.33      .1       0
Bank Sta=186.32,212.33
XS Rating Curve= 0 ,0
Exp/Cntr=0.3,0.1

Type RM Length L Ch R = 1 ,6852.489,98.97,113.22,119.92
XS GIS Cut Line= 2
1574969.12636204699086.7323378031574606.00306664698971.803084031
#Sta/Elev= 30
       0  204.94   14.68  203.37   22.03  202.15   29.37  200.66   36.71  199.01
   44.05  197.08    51.4  195.01   66.08  190.31   73.42  188.38   80.76  186.75
   95.45  184.06  110.13  182.32  117.48  181.88   139.5  181.66  154.19  179.98
  168.87  178.02  176.21  177.63  183.56  178.56   190.9   180.2  198.24  182.06
  205.58  183.64  212.92   184.3  242.29  185.66  249.64  185.78  264.32  186.69
  271.66   187.4   330.4  190.56  345.09  192.67  359.77  194.32  380.88     197
#Mann= 3 , 0 , 0
       0      .1       0  154.19    .045       0   190.9      .1       0
Bank Sta=154.19,190.9
XS Rating Curve= 0 ,0
Exp/Cntr=0.3,0.1

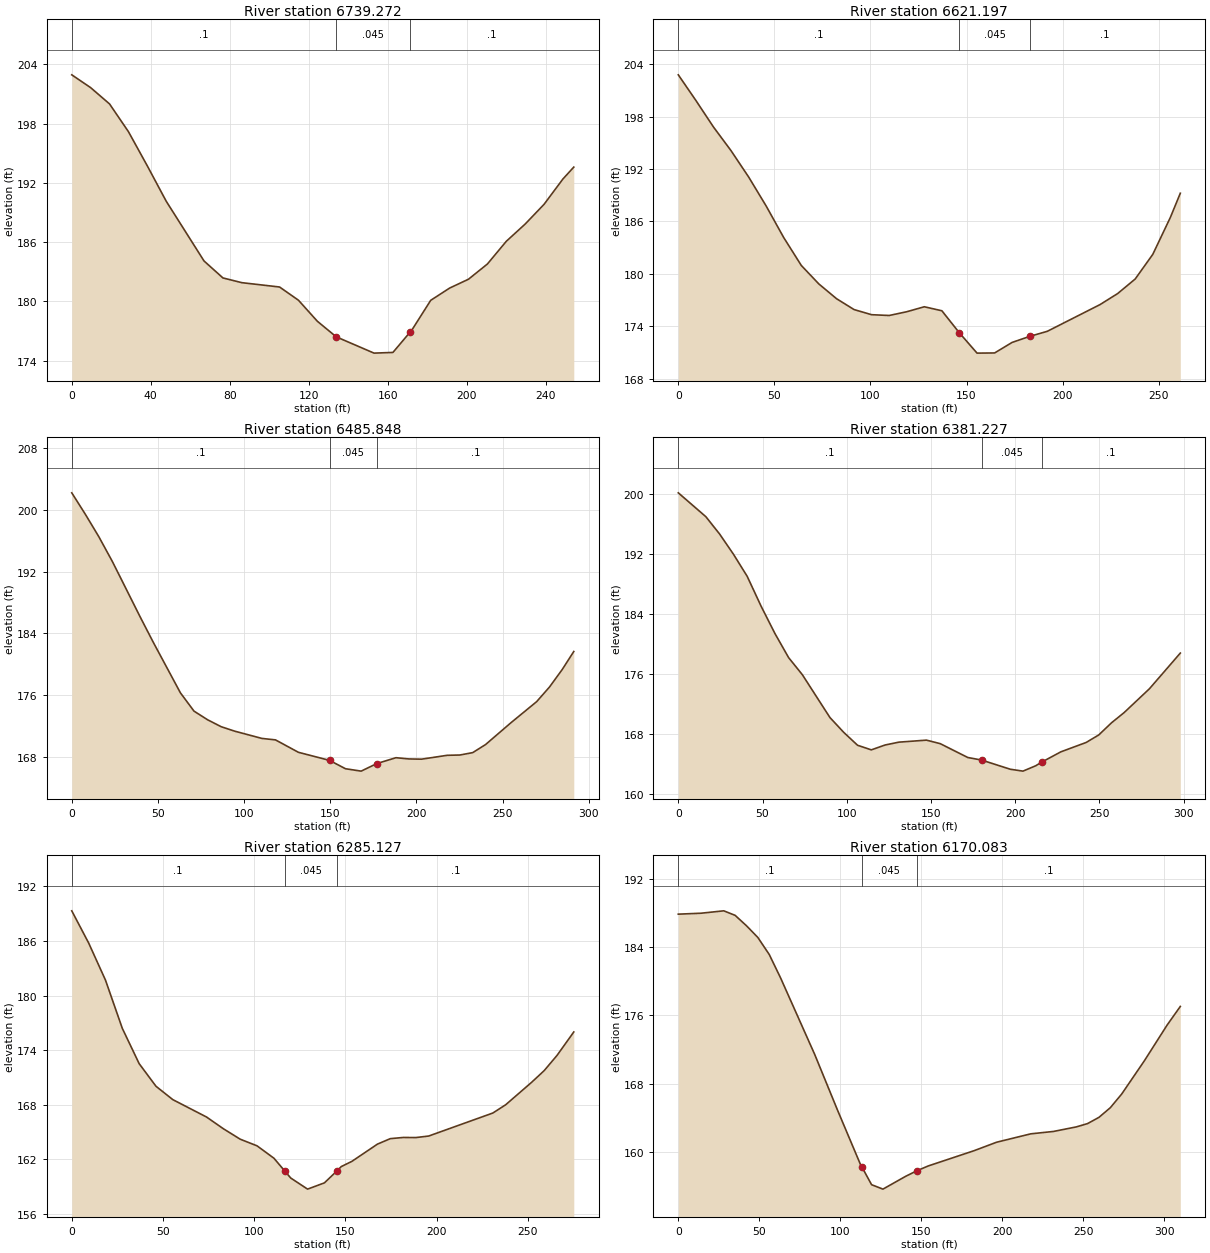
Type RM Length L Ch R = 1 ,6739.272,116.51,118.07,113.8
XS GIS Cut Line= 2
1574973.11234769699046.2081500591574787.09968269698872.817772985
#Sta/Elev= 26
       0  202.95    9.57  201.65   19.14     200   28.71  197.19   38.28  193.72
   47.85  190.14   66.99  184.09   76.56  182.37   86.13  181.89  105.26  181.45
  114.83  180.11   124.4  177.98  133.97   176.4  153.11  174.75  162.68  174.82
  171.55  176.92  172.25  177.08  181.82   180.1  191.39  181.34  200.96  182.24
  210.53  183.78   220.1  186.08  229.67  187.83  239.24  189.83  248.81   192.4
  254.29   193.6
#Mann= 3 , 0 , 0
       0      .1       0  133.97    .045       0  171.55      .1       0
Bank Sta=133.97,171.55
XS Rating Curve= 0 ,0
Exp/Cntr=0.3,0.1

Type RM Length L Ch R = 1 ,6621.197,136.61,135.35,127.72
XS GIS Cut Line= 2
1575076.74797536698976.4534006571574876.78436045698808.377671182
#Sta/Elev= 28
       0  202.78    9.14  199.85   18.29  196.81   27.43   194.1   36.58  191.09
   45.72  187.76   54.87  184.14   64.01  180.95   73.15  178.83    82.3  177.15
   91.44   175.9  100.59  175.31  109.73  175.22  118.88  175.65  128.02  176.22
  137.16  175.76  146.31  173.22  155.45  170.91   164.6  170.93  173.74  172.14
  182.89  172.83  192.03  173.41  219.46  176.47  228.61  177.73  237.75   179.4
   246.9  182.22  256.04  186.45  261.22  189.22
#Mann= 3 , 0 , 0
       0      .1       0  146.31    .045       0  182.89      .1       0
Bank Sta=146.31,182.89
XS Rating Curve= 0 ,0
Exp/Cntr=0.3,0.1

Type RM Length L Ch R = 1 ,6485.848,99.39,104.62,79.93
XS GIS Cut Line= 4
 1575183.1576774 698853.900782631575074.40379696698797.615879595
1575023.84278233698755.6406976731574926.53667879698721.297367021
#Sta/Elev= 30
       0  202.21    7.88  199.43   15.76   196.5   23.65  193.27   39.41  186.25
   47.29  182.84   63.06  176.28   70.94  173.91   78.82  172.79    86.7  171.89
   94.58  171.31  110.35  170.37  118.23  170.18  131.55  168.57  149.67  167.52
  158.85  166.44  167.95  166.13  177.04  167.11  188.17  167.87  195.59  167.71
  203.02  167.68  217.86  168.18  225.29  168.22  232.71  168.53  240.13  169.57
  254.98  172.42  269.82  175.14  277.25  177.03  284.67  179.31  291.36  181.64
#Mann= 3 , 0 , 0
       0      .1       0  149.67    .045       0  177.04      .1       0
Bank Sta=149.67,177.04
XS Rating Curve= 0 ,0
Exp/Cntr=0.3,0.1

Type RM Length L Ch R = 1 ,6381.227,85.91,96.1,102.32
XS GIS Cut Line= 3
1575219.40897085698782.3521770831575057.23213163698684.092092142
1574956.11010244698644.978854433
#Sta/Elev= 30
       0  200.18   16.37  196.99   24.55  194.67   32.74  191.98   40.92  189.02
   49.11  185.06   57.29  181.42   65.48  178.17   73.66  175.88   90.03  170.16
   98.22  168.18   106.4  166.46  114.58  165.84  122.77  166.49  130.95  166.87
  147.32  167.14  155.51  166.67  171.88  164.82  180.06  164.48  197.13  163.25
  204.63     163  212.14  163.71  215.93164.2241  227.15  165.58  242.16  166.83
  249.66  167.84  257.17  169.45  264.68  170.82  279.69     174  298.04  178.77
#Mann= 3 , 0 , 0
       0      .1       0  180.06    .045       0  215.93      .1       0
#XS Ineff= 2 , 0
          147.33  167.12
Permanent Ineff=
       F       F
Bank Sta=180.06,215.93
XS Rating Curve= 0 ,0
Exp/Cntr=0.3,0.1

Type RM Length L Ch R = 1 ,6285.127,124.73,115.04,85.87
XS GIS Cut Line= 3
1575213.68508242698701.2637574521575097.29935071698601.095709696
1574976.14371198698589.647932813
#Sta/Elev= 30
       0  189.32    9.24  185.79   18.47  181.71   27.71   176.4   36.94  172.52
   46.18  170.03   55.41  168.56   73.88  166.65   83.12  165.36   92.36  164.21
  101.59  163.48  110.83  162.12  116.71  160.73  120.06  159.94   129.3  158.72
  138.53  159.41   145.5  160.74  147.77   161.2  153.56  161.77  167.62  163.67
  174.65  164.27  181.68   164.4  188.71  164.39  195.74  164.56   230.9  167.09
  237.93     168  251.99  170.44  259.02  171.75  266.05  173.42  275.25     176
#Mann= 3 , 0 , 0
       0      .1       0  116.71    .045       0   145.5      .1       0
Bank Sta=116.71,145.5
XS Rating Curve= 0 ,0
Exp/Cntr=0.3,0.1

Type RM Length L Ch R = 1 ,6170.083,71.07,71.1,69.92
XS GIS Cut Line= 2
1575292.86553921698512.3754388091574983.77556326698534.317011192
#Sta/Elev= 29
       0  187.83   14.04  187.94   28.07  188.22   35.09  187.69   42.11  186.47
   49.12   185.1   56.14  183.11   63.16  180.36   84.21  171.41   98.25  164.91
  112.28  158.61  113.23  158.28   119.3  156.17  126.32  155.65  140.35  157.15
  147.37  157.81  154.39  158.37  182.46  160.14  196.49  161.14  217.55  162.12
  231.58   162.4  245.62  162.93  252.63  163.32  259.65  164.05  266.67  165.18
  273.69  166.78  287.72  170.68  301.76  174.86  309.87  177.03
#Mann= 3 , 0 , 0
       0      .1       0  113.23    .045       0  147.37      .1       0
Bank Sta=113.23,147.37
XS Rating Curve= 0 ,0
Exp/Cntr=0.3,0.1

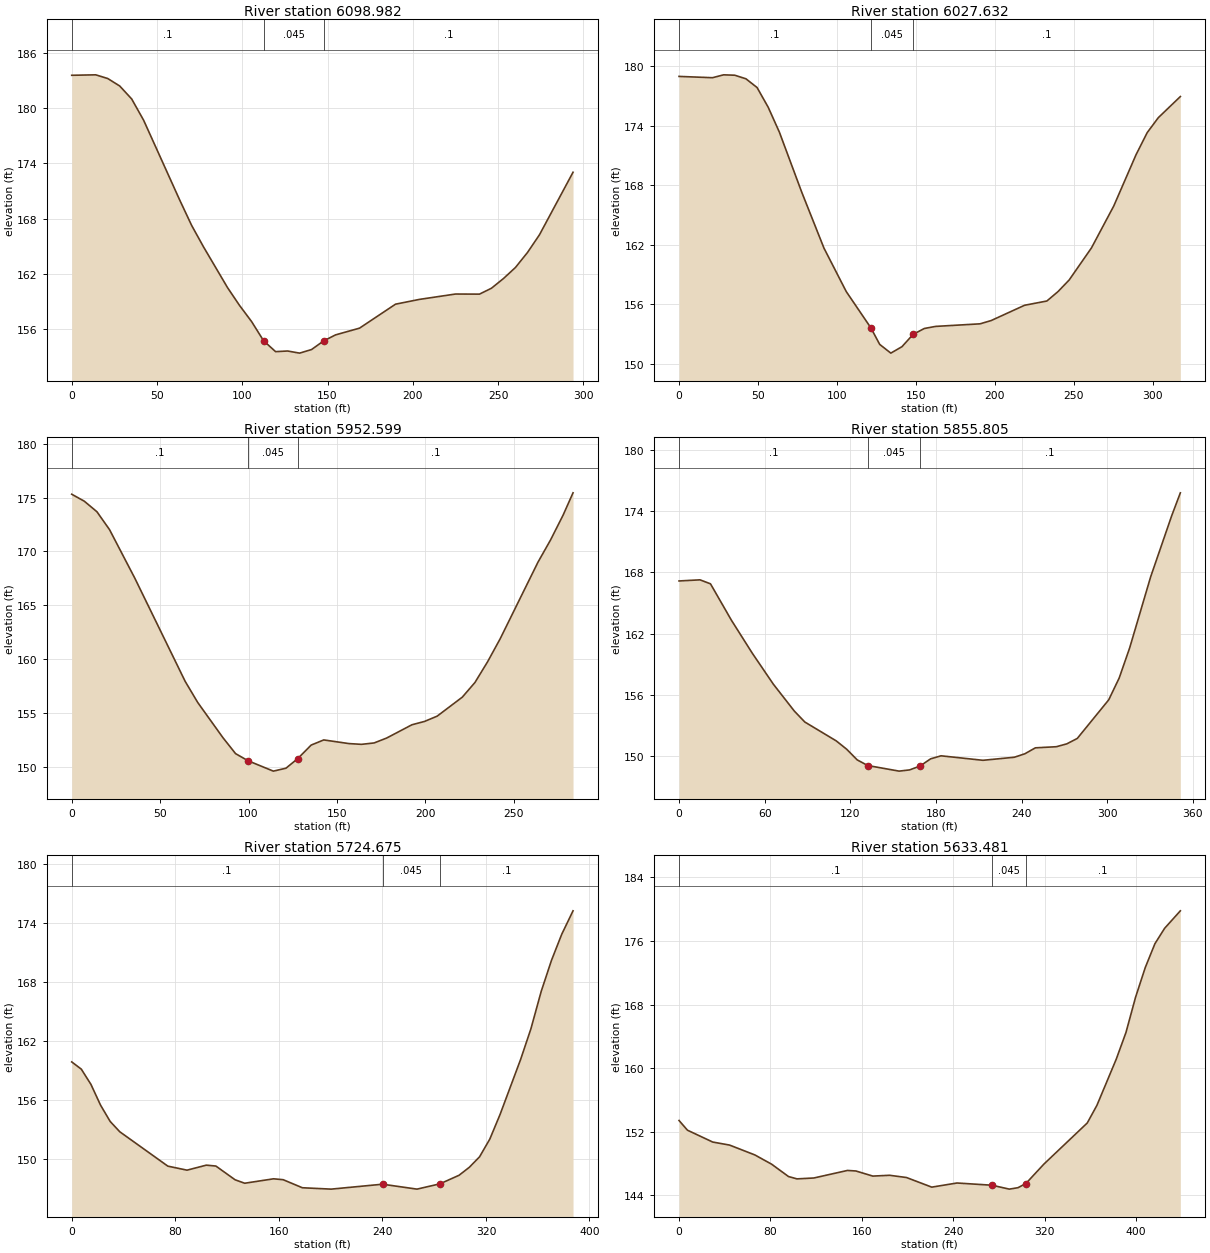
Type RM Length L Ch R = 1 ,6098.982,70.92,71.35,68.82
XS GIS Cut Line= 2
1575281.62499915698439.2736482921574989.02010363698467.525155455
#Sta/Elev= 30
       0  183.56   14.07  183.61    21.1  183.21   28.13   182.4   35.16  180.99
    42.2  178.67   63.29  170.04   70.33  167.27   77.36  164.92   91.42  160.51
   98.46  158.58  105.49  156.84  112.52  154.76  119.55  153.58  126.59  153.65
  133.62  153.42  140.65  153.81  147.68  154.74  154.72   155.4  168.78  156.13
  189.88  158.73  203.94  159.25  225.04  159.83  239.11  159.82  246.14  160.46
  253.17  161.51   260.2  162.71  267.24  164.33  274.27  166.25  293.97  173.04
#Mann= 3 , 0 , 0
       0      .1       0  112.52    .045       0  147.68      .1       0
Bank Sta=112.52,147.68
XS Rating Curve= 0 ,0
Exp/Cntr=0.3,0.1

Type RM Length L Ch R = 1 ,6027.632,76.07,75.03,71.99
XS GIS Cut Line= 2
1575295.72748342 698363.554339261574980.91361898698403.621558368
#Sta/Elev= 30
       0  178.95   21.17  178.82   28.23  179.11   35.28  179.07   42.34  178.71
    49.4  177.83   56.45  175.84   63.51  173.34   77.62  167.31   91.73  161.66
  105.85  157.28  121.42  153.63  127.02  151.96  134.07  151.08  141.13  151.73
  148.19  152.97  155.24  153.56   162.3  153.77  190.52  154.03  197.58  154.36
  218.75   155.9  232.86  156.33  239.92  157.28  246.98  158.45  261.09  161.68
   275.2   165.9  289.32  171.07  296.37  173.29  303.43   174.8  317.35  176.92
#Mann= 3 , 0 , 0
       0      .1       0  121.42    .045       0  148.19      .1       0
Bank Sta=121.42,148.19
XS Rating Curve= 0 ,0
Exp/Cntr=0.3,0.1

Type RM Length L Ch R = 1 ,5952.599,99.65,96.79,90.7
XS GIS Cut Line= 2
1575260.43636878 698285.908323751574981.95722687698339.384390861
#Sta/Elev= 30
       0  175.32    7.13  174.67   14.26  173.69   21.38  172.03   35.64  167.53
   64.15  157.93   71.28  155.96   85.53  152.69   92.66  151.21   99.79  150.54
  114.05  149.58  121.17  149.85  127.89  150.75  135.43     152  142.56  152.48
  156.81  152.14  163.94  152.07  171.07   152.2   178.2  152.66  192.45  153.89
  199.58   154.2  206.71  154.69  220.96  156.46  228.09  157.82  235.22  159.74
  242.35  161.88  263.73     169  270.86  171.07  277.99  173.39  283.57  175.45
#Mann= 3 , 0 , 0
       0      .1       0   99.79    .045       0  127.89      .1       0
Bank Sta=99.79,127.89
XS Rating Curve= 0 ,0
Exp/Cntr=0.3,0.1

Type RM Length L Ch R = 1 ,5855.805,109.35,131.13,97.6
XS GIS Cut Line= 2
1575289.04961358698164.172225118 1574954.2021396698270.064161316
#Sta/Elev= 30
       0  167.17   14.68  167.28   22.03  166.89   36.71  163.32   51.39  160.08
   66.08  157.06   80.76  154.43    88.1  153.36  110.13  151.51  117.47  150.69
  124.81  149.65  132.15   149.1  154.18  148.55  161.52  148.67  168.86  149.05
   176.2  149.75  183.54  150.05  212.91  149.61  234.93  149.91  242.28  150.25
  249.62  150.83   264.3  150.94  271.64  151.22  278.98  151.75  301.01  155.53
  308.35  157.67  315.69  160.62  330.38  167.57  345.06  173.53  351.19   175.8
#Mann= 3 , 0 , 0
       0      .1       0  132.15    .045       0  168.86      .1       0
Bank Sta=132.15,168.86
XS Rating Curve= 0 ,0
Exp/Cntr=0.3,0.1

Type RM Length L Ch R = 1 ,5724.675,80.16,91.19,95.99
XS GIS Cut Line= 4
1575273.73287243698053.4317372591575064.06780975698127.555749327
1575009.71020086698169.9123276621574924.99704425698215.092677861
#Sta/Elev= 30
       0  159.88    7.42  159.14   14.85  157.59   22.27  155.48    29.7  153.82
   37.12  152.77   74.25  149.27   89.09  148.86  103.94  149.37  111.37  149.28
  126.22  147.88  133.64  147.53  155.92  147.98  163.34  147.89  178.19  147.07
  200.46  146.93  240.13  147.43  266.75  146.93   284.5  147.47  299.23  148.34
  307.16  149.15  315.09  150.22  323.03  152.03  330.96  154.54  346.83  160.14
  354.76  163.25  362.69  167.05  370.63  170.21  378.56  172.87   387.3  175.26
#Mann= 3 , 0 , 0
       0      .1       0  240.13    .045       0   284.5      .1       0
Bank Sta=240.13,284.5
XS Rating Curve= 0 ,0
Exp/Cntr=0.3,0.1

Type RM Length L Ch R = 1 ,5633.481,94.94,101.92,97.72
XS GIS Cut Line= 4
1575255.66026434697985.7777019291575017.16491249698064.958158731
1574950.38621397698092.6236195561574854.98807327698157.494355246
#Sta/Elev= 30
       0  153.43    7.38  152.21    29.5  150.72   44.25  150.34   66.38   149.1
   81.13  147.93   95.88  146.38  103.26  146.09  118.01   146.2  147.51  147.15
  154.89  147.08  169.64  146.44  184.39  146.54  199.14  146.26  221.27  145.05
   243.4  145.57  274.03  145.29  289.18   144.8  296.76  144.98  303.66145.4998
  319.49  147.95  357.44  153.12   365.9  155.34  382.83  161.15   391.3  164.49
  399.76  168.95  408.23  172.67  416.69  175.67  425.16   177.6  438.94   179.8
#Mann= 3 , 0 , 0
       0      .1       0  274.03    .045       0  303.66      .1       0
Bank Sta=274.03,303.66
XS Rating Curve= 0 ,0
Exp/Cntr=0.3,0.1

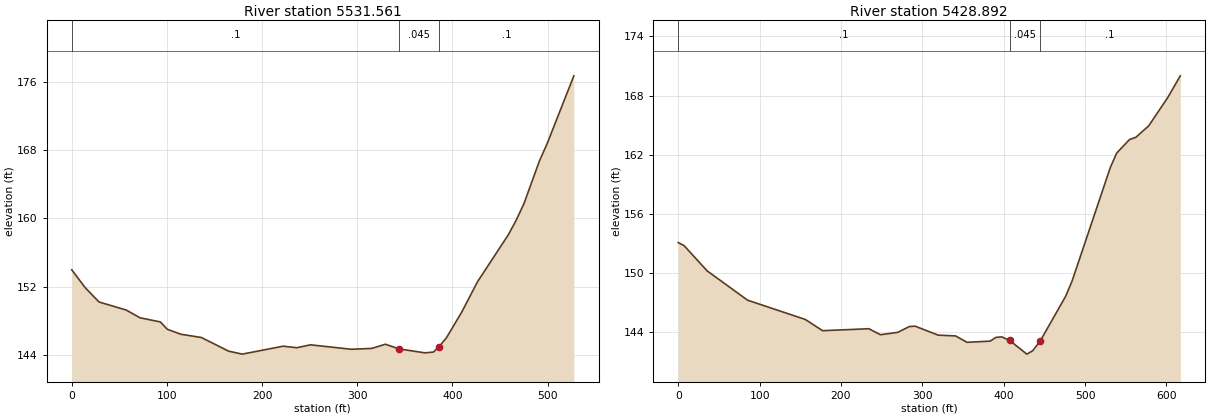
Type RM Length L Ch R = 1 ,5531.561,83.58,102.67,114.53
XS GIS Cut Line= 4
1575267.49924558697920.6566955451574931.50810695697994.312410638
1574899.22067018698020.5459529761574777.13379997698093.192685679
#Sta/Elev= 30
       0  153.96   14.33  151.84   28.66  150.19   57.33  149.24   71.66  148.34
   93.16  147.85  100.33     147  114.66  146.41  136.16  146.03  164.82  144.43
  179.16  144.08  222.15  145.01  236.49  144.83  250.82  145.17  293.82  144.65
  315.31  144.75  329.65  145.24  343.97  144.69  371.03  144.23  380.05  144.32
  385.57  144.91  393.72  145.99  410.01  149.04   426.3  152.54  458.88  158.08
  467.03  159.77  475.17   161.7  491.46  166.71  499.61  168.75  527.64  176.69
#Mann= 3 , 0 , 0
       0      .1       0  343.97    .045       0  385.57      .1       0
Bank Sta=343.97,385.57
XS Rating Curve= 0 ,0
Exp/Cntr=0.3,0.1

Type RM Length L Ch R = 1 ,5428.892,65.72,50.19,48.29
XS GIS Cut Line= 4
1575255.66026434697879.8857657021574854.03409185 697947.61844565
1574816.82881692697950.4803898781574663.23781034698028.706865251
#Sta/Elev= 30
       0  153.06     7.1  152.76   35.49  150.19   85.19  147.21  156.17  145.25
  177.47  144.11  234.26  144.31  248.46   143.7  269.76  143.94  283.95  144.53
  291.05  144.57  319.45  143.66  340.74  143.58  354.94  142.93  383.34  143.05
  390.44  143.43  397.54  143.48   407.3  143.12  428.36  141.73  435.38  142.06
  444.61  143.03  476.04   147.6  483.89  149.13  531.02   160.7  538.88  162.16
  554.59  163.53  562.45  163.76  578.16  164.92  601.72  167.82  616.98     170
#Mann= 3 , 0 , 0
       0      .1       0   407.3    .045       0  444.61      .1       0
Bank Sta=407.3,444.61
XS Rating Curve= 0 ,0
Exp/Cntr=0.3,0.1