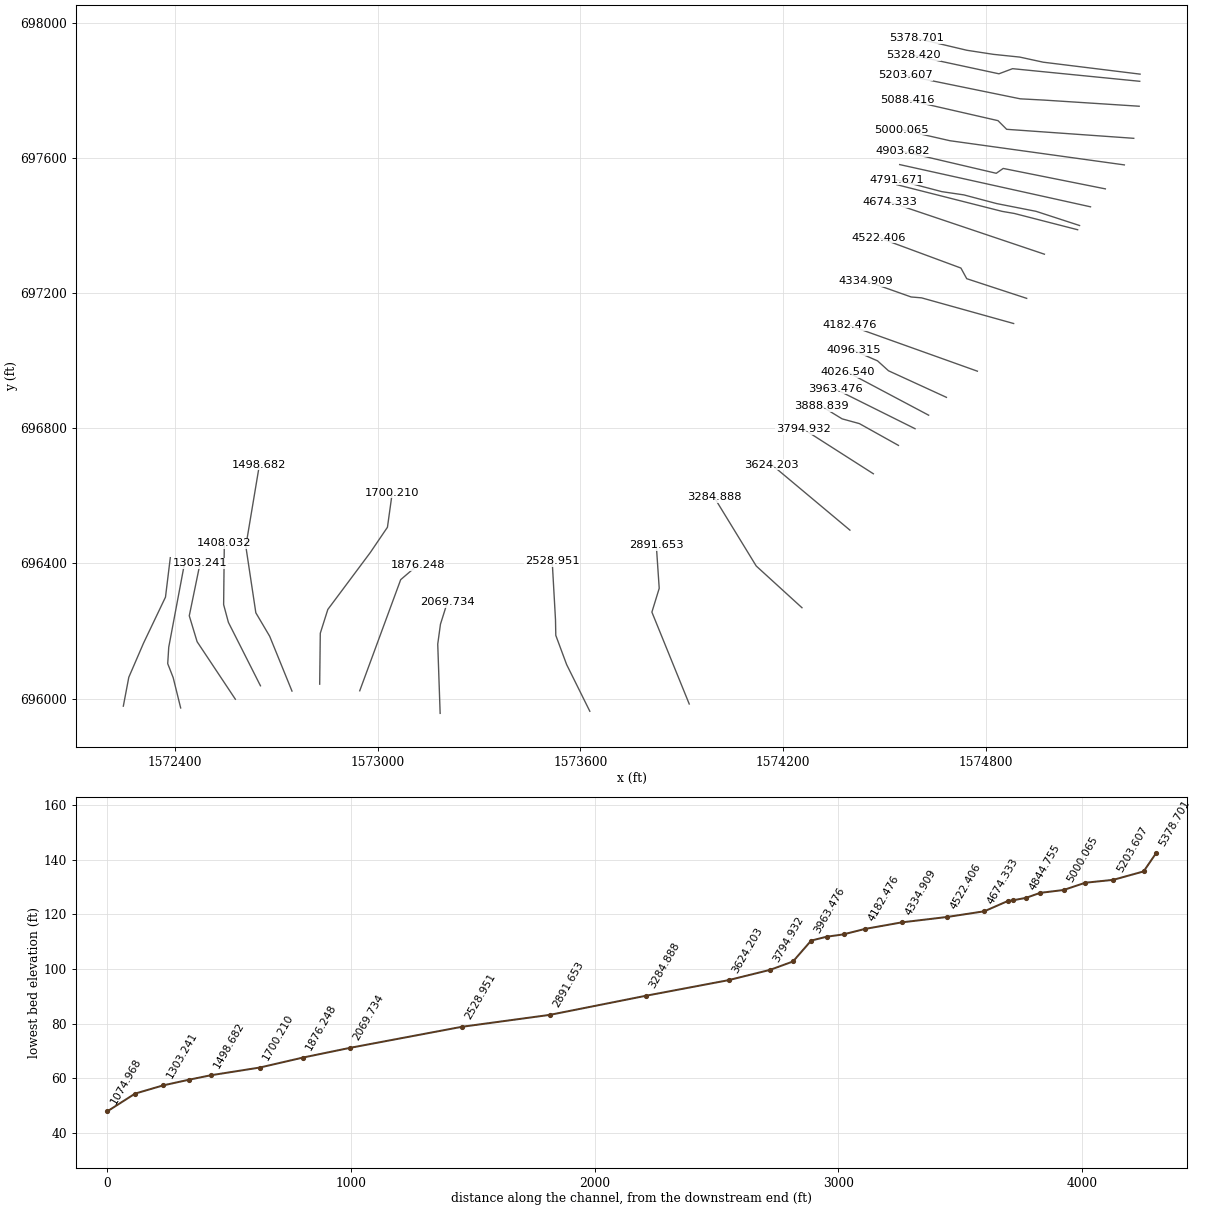
HEC-RAS study SusquehannaRiverTrib.prj: SusquehannaRiverTrib

--- SusquehannaRiverTrib.g01 (geometry) --- (continued)

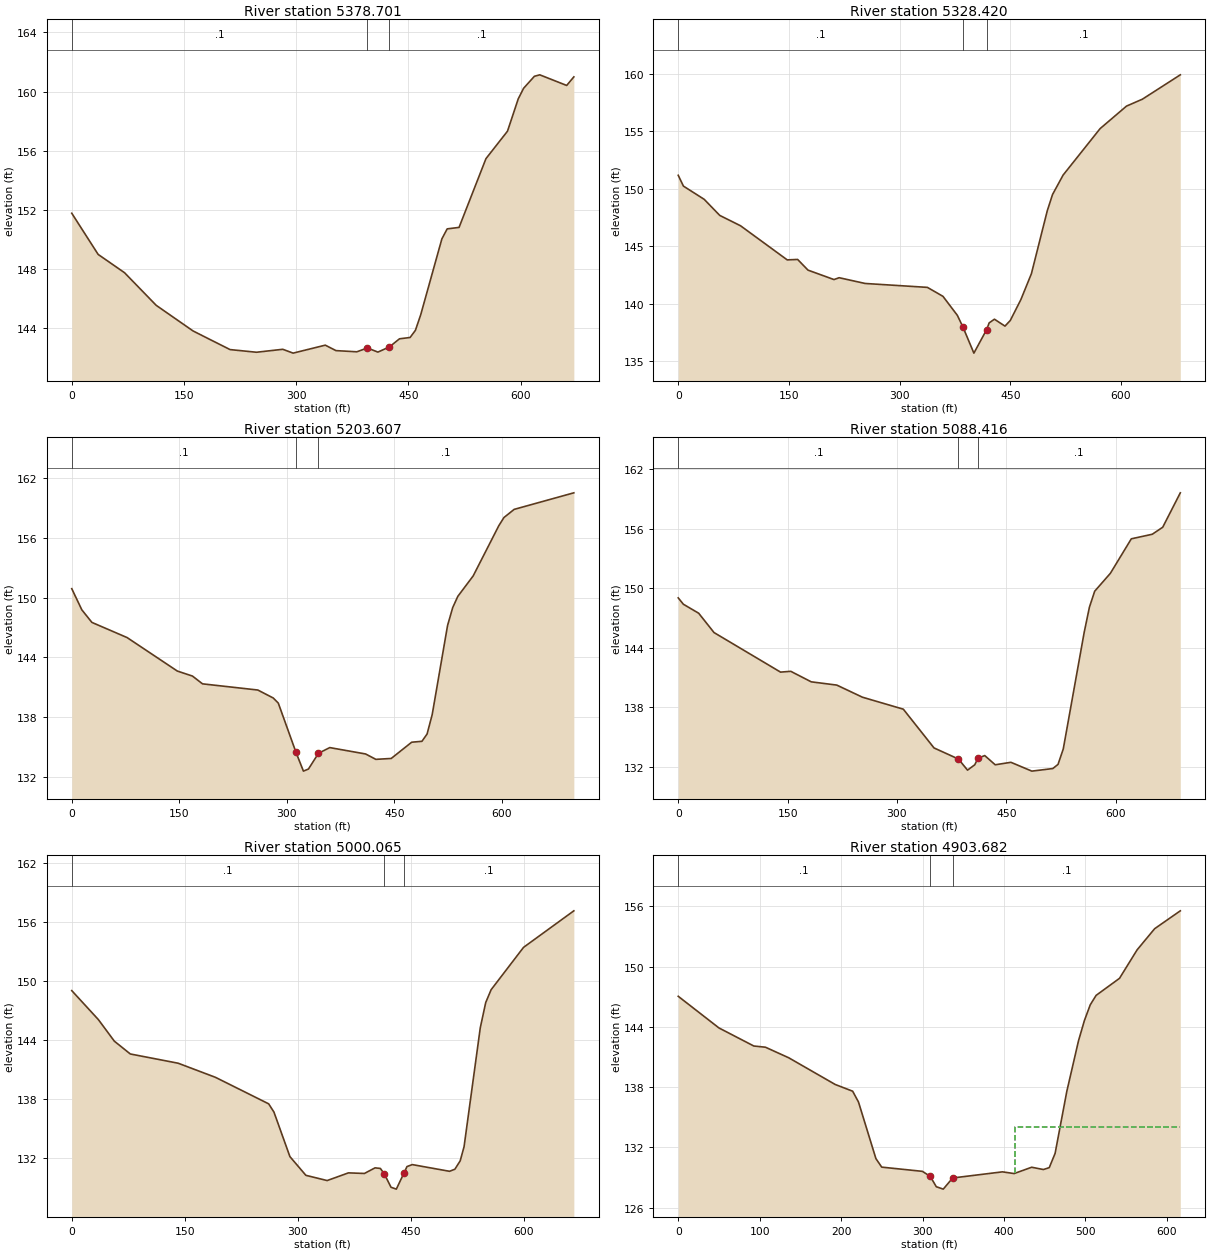
Type RM Length L Ch R = 1 ,5378.701,45.38,50.28,56.17
XS GIS Cut Line= 6
1575256.40043919697848.0099628721574969.84943807697883.324346796
 1574900.2296526697898.459082797 1574822.5380079697906.530941963
1574743.83738086697918.6387307641574594.50798586697953.953114703
#Sta/Elev= 30
       0  151.75   35.26  148.96   70.53  147.72  112.85  145.51  162.22  143.77
  211.59  142.51  246.85  142.33  282.12  142.53  295.88  142.27  338.86  142.81
  353.19  142.44  381.08  142.36  395.15  142.62  409.23  142.34  424.57  142.69
  438.07  143.24  452.24  143.33  459.32  143.81   466.4  144.86  494.73  150.01
  501.82  150.69   517.7  150.79  553.67  155.45  582.44  157.31  596.82   159.5
  604.02  160.22   618.4  161.03   625.6  161.13  661.56  160.41  671.15  160.99
#Mann= 3 , 0 , 0
       0      .1       0  395.15    .045       0  424.57      .1       0
Bank Sta=395.15,424.57
XS Rating Curve= 0 ,0
Exp/Cntr=0.3,0.1

Type RM Length L Ch R = 1 ,5328.420,127.24,124.81,62.63
XS GIS Cut Line= 4
1575255.39145684697826.8213324991574879.04102221697864.153681234
1574838.68172629697849.0189452621574585.42714429697903.503994763
#Sta/Elev= 30
       0  151.16    7.03  150.22   35.17  149.07   56.27  147.67   84.41  146.77
  147.72   143.8  161.79  143.84  175.86  142.91  211.03  142.09  218.06  142.25
  253.24  141.75  337.65  141.41  358.75  140.63   378.2  138.98  385.67  137.98
  400.63  135.69  417.94  137.74   421.3  138.32  428.46  138.64  442.78  138.04
  449.94  138.53  464.26  140.34  478.58   142.6  500.06  148.07  507.22  149.49
  521.54  151.18  571.66  155.22  607.47  157.18  628.95  157.78  680.35   159.9
#Mann= 3 , 0 , 0
       0      .1       0  385.67    .045       0  417.94      .1       0
Bank Sta=385.67,417.94
XS Rating Curve= 0 ,0
Exp/Cntr=0.3,0.1

Type RM Length L Ch R = 1 ,5203.607,128.33,115.19,88.59
XS GIS Cut Line= 4
1575253.75230156697753.0062385351574973.28176777697771.131885275
1574901.73316219697774.9478108881574561.16179979 697844.58845365
#Sta/Elev= 30
       0  150.89   14.03  148.77   28.06  147.51   77.16  145.99  147.31  142.63
  168.35  142.13  182.38  141.35  259.54  140.73  281.06  139.93  288.07  139.42
  312.62134.5116  323.12   132.6  330.13  132.81  344.15  134.39  359.85  134.96
  409.86  134.32  424.15  133.78  445.59  133.87  474.17   135.5  488.46  135.59
   495.6  136.32  502.75  138.27  524.18   147.2  531.33  148.99  538.47  150.12
  559.91  152.17  595.63   157.2  602.78  158.02  617.06  158.84  700.32   160.5
#Mann= 3 , 0 , 0
       0      .1       0  312.62    .045       0  344.15      .1       0
Bank Sta=312.62,344.15
XS Rating Curve= 0 ,0
Exp/Cntr=0.3,0.1

Type RM Length L Ch R = 1 ,5088.416,63.56,88.35,86.25
XS GIS Cut Line= 4
1575237.66160564 697658.08077997 1574861.5501447697684.726278558
  1574835.929473697710.3469502931574567.42483328 697771.83656244
#Sta/Elev= 30
       0  149.02    7.02  148.38   28.07  147.47   49.12  145.52  140.35  141.53
  154.39  141.61  182.46  140.55  217.54  140.22  252.63     139  308.77  137.79
  350.88  133.88  384.39  132.76  396.85  131.64  406.75  132.18  411.18  132.84
  420.47  133.11  434.83  132.18  456.37  132.43   485.1  131.54  513.82   131.8
  521.01  132.22  528.19  133.78  556.91  145.55  564.09  148.09  571.27  149.69
  592.82   151.5  621.54  154.98  650.27  155.44  664.63  156.15  688.74  159.62
#Mann= 3 , 0 , 0
       0      .1       0  384.39    .045       0  411.18      .1       0
Bank Sta=384.39,411.18
XS Rating Curve= 0 ,0
Exp/Cntr=0.3,0.1

Type RM Length L Ch R = 1 ,5000.065,74.56,96.38,79.51
XS GIS Cut Line= 3
1575209.86915678697579.3816224041574693.76521541697650.930227935
1574551.62198567697683.365595818
#Sta/Elev= 30
       0  149.04   35.33   146.1   56.54  143.91   77.74  142.61  141.34  141.67
  190.81  140.24  261.48  137.55  268.54  136.71  289.74  132.19  310.95  130.29
  339.21  129.76  367.48  130.54  388.68  130.48  402.82  131.05  409.88  130.99
  415.11130.4361  424.02  129.08  431.08  128.89  441.45 130.559  445.22  131.18
  452.28  131.38  501.75   130.7  508.82  130.91  515.89  131.76  521.04   133.2
  542.58  145.27  549.76  147.82  556.94  149.13  600.02  153.43  666.84  157.14
#Mann= 3 , 0 , 0
       0      .1       0  415.11    .045       0  441.45      .1       0
Bank Sta=415.11,441.45
XS Rating Curve= 0 ,0
Exp/Cntr=0.3,0.1

Type RM Length L Ch R = 1 ,4903.682,60.53,58.93,51.49
XS GIS Cut Line= 4
1575153.62580243697508.4560570871574851.30187602 697568.92084235
1574830.80533861697554.5732661781574555.12691085697619.137358949
#Sta/Elev= 30
       0  147.04   49.97  143.89    92.8  142.09  107.08  141.97  135.63  140.92
  192.74  138.26  214.16  137.59   221.3  136.52  242.71  130.88  249.85  130.03
  299.82  129.61  309.41  129.11  316.86  128.08   325.4  127.84  336.96  128.95
  398.04  129.56  412.41  129.39  433.98  130.02  448.36  129.79  455.55  129.98
  462.74   131.4  477.12  137.58   491.5  142.62  498.69  144.62  505.88  146.19
  513.07  147.13  541.82  148.83  563.39  151.66  584.96  153.77  616.47  155.55
#Mann= 3 , 0 , 0
       0      .1       0  309.41    .045       0  336.96      .1       0
#XS Ineff= 2 , 0
       0                  413.24       0     134
Permanent Ineff=
       F       F
Bank Sta=309.41,336.96
XS Rating Curve= 0 ,0
Exp/Cntr=0.3,0.1

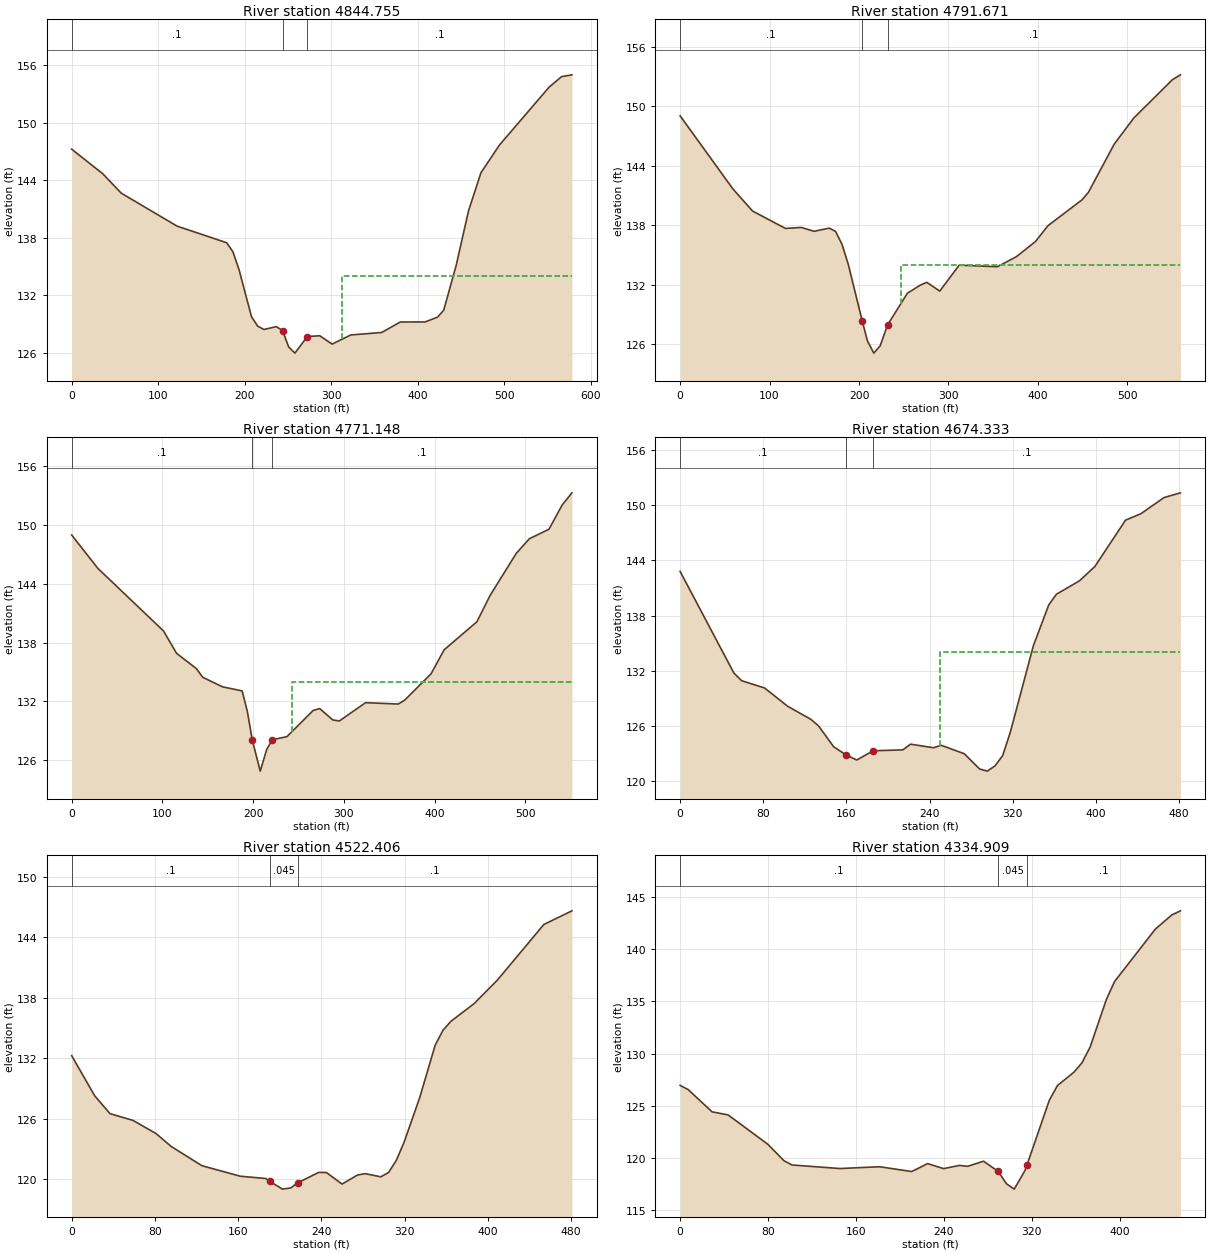
Type RM Length L Ch R = 1 ,4844.755,49.7,53.08,71.85
XS GIS Cut Line= 2
1575109.70110904697455.3640394211574544.94411583697580.335603803
#Sta/Elev= 30
       0  147.23   35.85  144.68   57.35  142.65  121.88  139.22  179.23  137.49
   186.4  136.56  193.57  134.67  207.91  129.79  215.08  128.81  222.25  128.46
  236.59  128.76  243.76  128.35  250.93  126.64   258.1     126  272.43  127.72
  286.77  127.81  301.11  126.94  322.62  127.89  358.47  128.15  379.97  129.24
  408.65  129.25  422.99  129.74  430.16  130.47   444.5  135.11  458.84  140.81
  473.18  144.77  494.68  147.67  552.04  153.69  566.38  154.78  578.42  154.97
#Mann= 3 , 0 , 0
       0      .1       0  243.76    .045       0  272.43      .1       0
#XS Ineff= 2 , 0
       0                  312.96       0     134
Permanent Ineff=
       F       F
Bank Sta=243.76,272.43
XS Rating Curve= 0 ,0
Exp/Cntr=0.3,0.1

Type RM Length L Ch R = 1 ,4791.671,19.19,20.52,19.59
XS GIS Cut Line= 6
1575077.26574117697400.0331178011574948.47825117697442.008299723
1574832.09251946697464.9038535061574734.78641592697490.661351502
1574669.91568024697500.2011655871574535.40430178697535.498477638
#Sta/Elev= 30
       0  149.02    58.9  141.67   80.99  139.43   117.8  137.68  135.46  137.78
  149.79  137.39   166.7  137.71  173.83  137.38  180.95  136.09  188.08  134.04
  203.56  128.38  209.45  126.35  216.57  125.12  223.69  125.86  232.03127.9718
  254.08  131.15  268.56  131.97   275.8  132.25  290.29  131.37  312.01  133.98
  354.74  133.82  375.96  134.83  397.19  136.35  411.34  137.96  449.25  140.55
  456.49  141.31  485.44  146.18  507.15  148.79  550.57  152.67  559.37  153.15
#Mann= 3 , 0 , 0
       0      .1       0  203.56    .045       0  232.03      .1       0
#XS Ineff= 2 , 0
       0                  246.49       0     134
Permanent Ineff=
       F       F
Bank Sta=203.56,232.03
XS Rating Curve= 0 ,0
Exp/Cntr=0.3,0.1

Type RM Length L Ch R = 1 ,4771.148,93.15,96.82,102.31
XS GIS Cut Line= 4
1575071.63965286697387.5264865161574884.09633583697435.693349376
1574848.22739539697441.8423105931574536.68002723697520.753979504
#Sta/Elev= 30
       0  148.99   28.91  145.58  101.18   139.2  115.63  136.91  137.32  135.36
  144.54  134.46  166.23  133.49  187.91  133.07  193.63  130.98  199.03  128.08
  207.83  124.88  214.94  127.09  221.23  128.09  237.24   128.4  266.13  131.07
  273.35  131.27  287.79  130.11  295.01     130   323.9  131.87     360  131.73
  367.22  132.14  396.11  134.82  410.55  137.27  446.65  140.13   461.1  142.81
  489.98  147.11  504.42  148.61  526.09  149.58  540.53  152.04  551.41   153.3
#Mann= 3 , 0 , 0
       0      .1       0  199.03    .045       0  221.23      .1       0
#XS Ineff= 2 , 0
       0                  242.92       0     134
Permanent Ineff=
       F       F
Bank Sta=199.03,221.23
XS Rating Curve= 0 ,0
Exp/Cntr=0.3,0.1

Type RM Length L Ch R = 1 ,4674.333,150.07,151.93,132.43
XS GIS Cut Line= 2
1574973.28176777697315.1287725571574517.27865502697468.719779164
#Sta/Elev= 30
       0   142.8    51.7  131.76   59.09  130.93   81.25  130.13  103.41  128.15
  125.57  126.74  132.96  126.04  147.73  123.74  159.51122.8736  169.89  122.31
  185.69123.3122  214.21  123.41  221.59  124.03  243.75  123.64  251.14  123.91
   273.3  122.99  288.07  121.33  295.46   121.1  302.84  121.67  310.23  122.79
  317.62  125.34  339.77  134.73  354.55  139.16  361.93  140.32  384.09  141.78
  398.87  143.33  428.41  148.37  443.18  149.07  465.34  150.82  481.17  151.34
#Mann= 3 , 0 , 0
       0      .1       0  159.51    .045       0  185.69      .1       0
#XS Ineff= 2 , 0
       0                  249.68       0     134
Permanent Ineff=
       F       F
Bank Sta=159.51,185.69
XS Rating Curve= 0 ,0
Exp/Cntr=0.3,0.1

Type RM Length L Ch R = 1 ,4522.406,112.49,187.5,148.43
XS GIS Cut Line= 4
1574920.81279036697184.4333197331574743.37224856697242.626185581
1574726.20058322697274.1075720341574483.88930579697363.781824335
#Sta/Elev= 30
       0  132.25    22.1  128.28   36.83  126.51   58.93  125.84   81.04  124.54
   95.77  123.25  125.24  121.35  162.07  120.31  186.74  120.08  190.27119.8105
  202.69  119.03  210.66  119.15  217.35119.6569  237.53  120.69  244.99  120.67
  259.92  119.53  274.85  120.43  282.31  120.56  297.24  120.25   304.7  120.68
  312.17  121.89  319.63  123.69  334.56  128.08  349.49  133.29  356.95  134.76
  364.42  135.64  386.81   137.4   409.2  139.73  453.98  145.25  480.97   146.6
#Mann= 3 , 0 , 0
       0      .1       0  190.27    .045       0  217.35      .1       0
Bank Sta=190.27,217.35
XS Rating Curve= 0 ,0
Exp/Cntr=0.3,0.1

Type RM Length L Ch R = 1 ,4334.909,156.76,152.43,142.63
XS GIS Cut Line= 4
1574882.18396264697110.001006126 1574609.5846823697185.971297354
1574578.94120343697188.5249206271574445.51438944697235.766950458
#Sta/Elev= 30
       0  126.96    7.27  126.56   29.07  124.43    43.6  124.14   79.93  121.32
   94.47  119.76  101.73  119.35  145.34  119.01  181.67  119.18  210.74  118.72
  225.27  119.48   239.8     119  254.34  119.31   261.6  119.22  276.14  119.71
  289.51118.7277  297.04  117.55  304.06  117.04  313.74   118.8  315.65 119.347
  336.01  125.54  343.44  126.95  358.29  128.21  365.72  129.12  373.14  130.63
     388   135.2  395.42   136.9  432.55  141.91   447.4  143.25  455.28  143.65
#Mann= 3 , 0 , 0
       0      .1       0  289.51    .045       0  315.65      .1       0
Bank Sta=289.51,315.65
XS Rating Curve= 0 ,0
Exp/Cntr=0.3,0.1

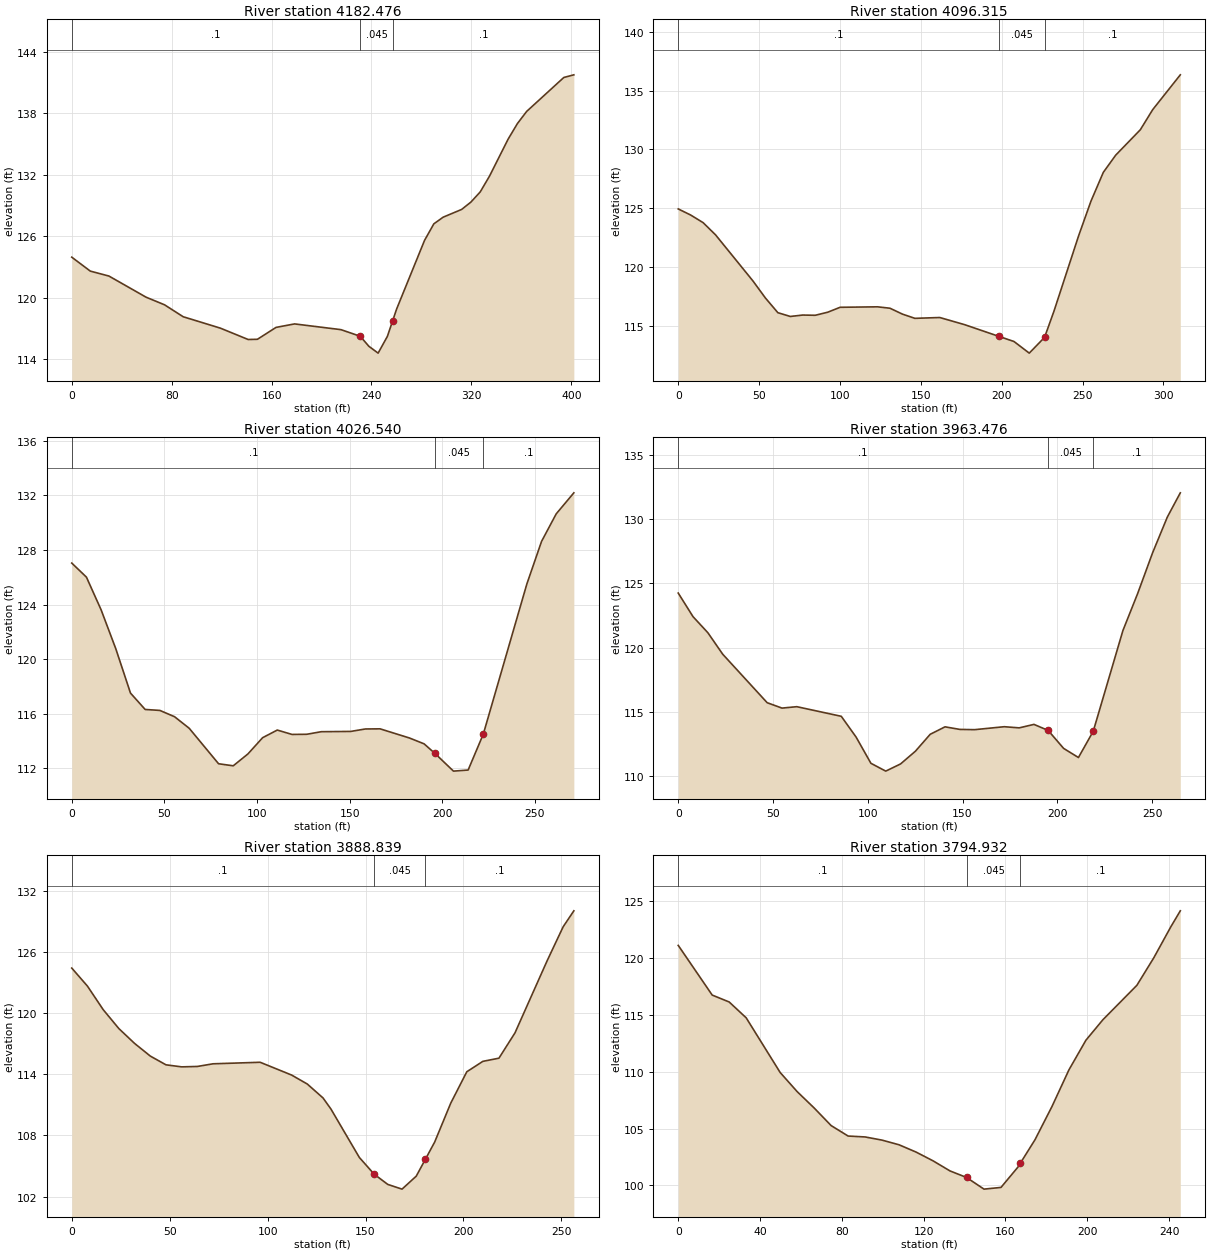
Type RM Length L Ch R = 1 ,4182.476,98.98,86.16,77.73
XS GIS Cut Line= 2
1574774.93178675696968.9133224041574396.35714217697104.255353853
#Sta/Elev= 30
       0  123.97   14.87  122.61   29.74  122.13   59.47  120.07   74.34  119.32
   89.21  118.16  118.94  117.05  141.24  115.94  148.68  115.96  163.55  117.12
  178.41  117.46  215.58   116.9  231.01116.2529  237.88  115.28  245.32  114.61
  252.75  116.25  257.02117.7923  260.19  118.93  282.49  125.61  289.92  127.22
  297.36  127.87  312.22  128.63  319.66  129.35  327.09  130.34  334.52  131.88
  349.39  135.48  356.83     137  364.26  138.19     394   141.5  402.04  141.76
#Mann= 3 , 0 , 0
       0      .1       0  231.01    .045       0  257.02      .1       0
Bank Sta=231.01,257.02
XS Rating Curve= 0 ,0
Exp/Cntr=0.3,0.1

Type RM Length L Ch R = 1 ,4096.315,76.64,69.78,72.34
XS GIS Cut Line= 4
1574683.29843695696891.4946492311574511.77142923696970.195276305
1574479.48399246696999.4557658731574407.84624216697030.734220207
#Sta/Elev= 30
       0  124.93     7.7  124.41    15.4  123.76    23.1  122.72   46.21   118.8
   53.91  117.35   61.61   116.1   69.31  115.78   77.02   115.9   84.72  115.88
   92.42  116.14  100.12  116.56  123.23   116.6  130.93  116.48  138.63  115.98
  146.33  115.62  161.73  115.69  177.14  115.08  198.17  114.09  207.61  113.65
  217.06  112.66  226.51     114  232.29  116.21  247.57  122.64  255.21  125.59
  262.85  128.04  270.48   129.5  285.76  131.67   293.4  133.38  310.46  136.34
#Mann= 3 , 0 , 0
       0      .1       0  198.17    .045       0  226.51      .1       0
Bank Sta=198.17,226.51
XS Rating Curve= 0 ,0
Exp/Cntr=0.3,0.1

Type RM Length L Ch R = 1 ,4026.540,73.22,63.06,61.91
XS GIS Cut Line= 2
1574630.65207396696838.6785374281574391.24989566 696965.72129336
#Sta/Elev= 30
       0  127.04    7.92  126.01   15.85  123.61   23.77  120.76    31.7  117.51
   39.62  116.31   47.55  116.24   55.47  115.78    63.4  114.93   79.25  112.33
   87.17  112.18   95.09  113.05  103.02  114.24  110.94   114.8  118.87  114.48
  126.79  114.49  134.72  114.68  150.57   114.7  158.49  114.88  166.42  114.89
  182.26  114.22  190.19  113.79  196.03113.0888  206.04  111.79  213.96  111.87
  222.16114.5075  245.66  125.51  253.59  128.63  261.51  130.65  271.02  132.19
#Mann= 3 , 0 , 0
       0      .1       0  196.03    .045       0  222.16      .1       0
Bank Sta=196.03,222.16
XS Rating Curve= 0 ,0
Exp/Cntr=0.3,0.1

Type RM Length L Ch R = 1 ,3963.476,90.08,74.64,71.85
XS GIS Cut Line= 2
1574590.47205628696798.6682685911574353.36119267696916.719209194
#Sta/Elev= 29
       0  124.24    7.82   122.4   15.64  121.15   23.46  119.48   46.92   115.7
   54.74  115.28   62.56  115.39   86.02  114.64   93.84  113.02  101.65  110.98
  109.47  110.37  117.29  110.93  125.11  111.92  132.93  113.24  140.75  113.82
  148.57  113.62  156.39   113.6  172.03  113.83  179.85  113.74  187.67  114.01
  195.16  113.54  203.31  112.14  211.13  111.43  218.95  113.48  234.59  121.32
  242.41  124.22  250.23  127.37  258.05  130.17  264.87  132.05
#Mann= 3 , 0 , 0
       0      .1       0  195.16    .045       0  218.95      .1       0
Bank Sta=195.16,218.95
XS Rating Curve= 0 ,0
Exp/Cntr=0.3,0.1

Type RM Length L Ch R = 1 ,3888.839,99.59,93.91,87.93
XS GIS Cut Line= 4
1574541.27526075696749.3017241811574425.72380936696813.780710861
1574374.65134464696827.8256386671574314.00279284696864.853175566
#Sta/Elev= 30
       0   124.4    8.02  122.63   16.03  120.33   24.05  118.47   32.06  117.02
   40.08  115.78    48.1  114.92   56.11  114.72   64.13  114.76   72.14  115.02
   96.19  115.17  112.23  113.92  120.24  113.04  128.26  111.68  132.32  110.59
  146.84  105.84   154.4104.2044  161.36   103.2  168.62  102.74  175.88  104.01
   180.6105.6814  185.29  107.35  193.49  111.16   201.7  114.24   209.9  115.26
   218.1  115.57   226.3  118.05   242.7  125.11   250.9  128.45  256.35  130.01
#Mann= 3 , 0 , 0
       0      .1       0   154.4    .045       0   180.6      .1       0
Bank Sta=154.4,180.6
XS Rating Curve= 0 ,0
Exp/Cntr=0.3,0.1

Type RM Length L Ch R = 1 ,3794.932,171.76,170.73,153.98
XS GIS Cut Line= 2
1574467.01424961696665.3657759431574260.11722383696797.519897103
#Sta/Elev= 29
       0  121.12   16.61  116.75   24.92  116.14   33.22  114.75   49.84  109.94
   58.14  108.26   66.45  106.82   74.76  105.27   83.06  104.35   91.37  104.27
   99.67  103.99  107.98  103.58  116.29  102.94  124.59  102.17   132.9  101.28
  140.97100.7064  149.51   99.68  157.82   99.83  166.12  101.62  167.31101.9697
  174.43  104.02  182.73  106.94  191.04  110.17  199.35  112.78  207.65  114.58
  224.27  117.61  232.57  120.04  240.88  122.76   245.5  124.16
#Mann= 3 , 0 , 0
       0      .1       0  140.97    .045       0  167.31      .1       0
Bank Sta=140.97,167.31
XS Rating Curve= 0 ,0
Exp/Cntr=0.3,0.1

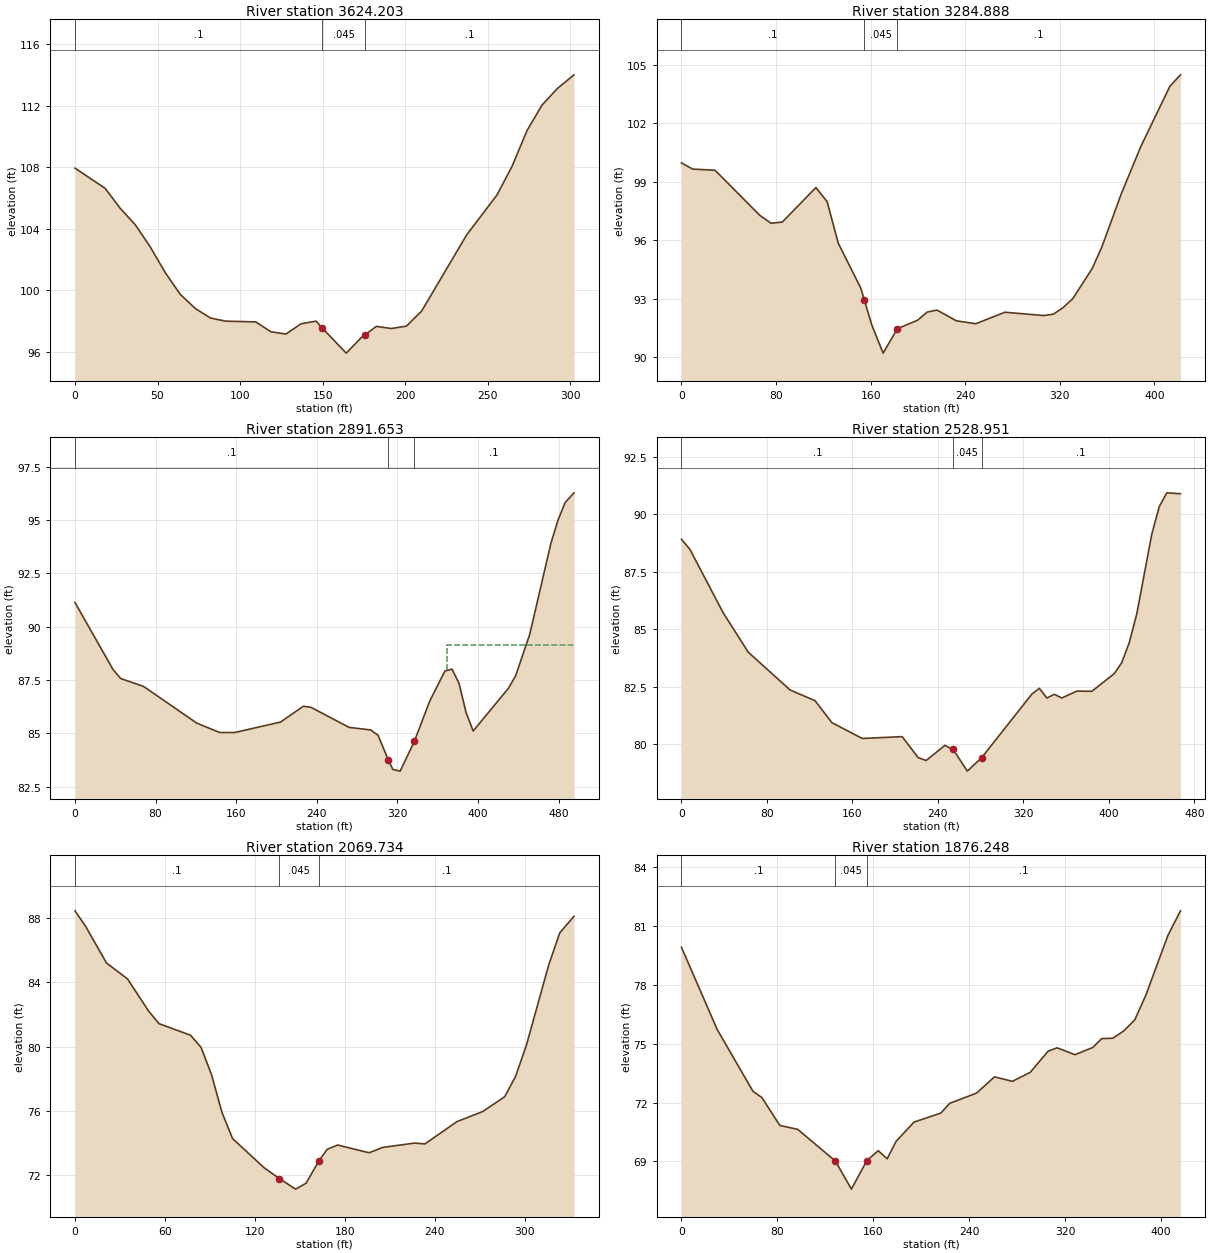
Type RM Length L Ch R = 1 ,3624.203,265.66,339.32,242.12
XS GIS Cut Line= 2
 1574397.6874975696498.548278749 1574165.8761702696692.446538508
#Sta/Elev= 30
       0  107.94   18.25  106.63   27.38  105.33    36.5  104.26   45.63  102.81
   54.76  101.13   63.88   99.72   73.01    98.8   82.13   98.19   91.26   97.99
  109.51   97.94  118.64    97.3  127.76   97.15  136.89   97.82  146.01   97.99
  149.8797.52751  164.27   95.91  173.39   96.92  175.8997.12145  182.52   97.65
  191.64   97.51  200.77   97.67   209.9   98.64  237.27  103.61  255.53  106.19
  264.65  108.05  273.78  110.39   282.9  112.05  292.03  113.11  302.21  114.01
#Mann= 3 , 0 , 0
       0      .1       0  149.87    .045       0  175.89      .1       0
Bank Sta=149.87,175.89
XS Rating Curve= 0 ,0
Exp/Cntr=0.3,0.1

Type RM Length L Ch R = 1 ,3284.888,360.83,393.23,293.45
XS GIS Cut Line= 3
 1574255.7843018696268.9034124911574120.38048916696392.391689643
1573995.80898149696596.039023876
#Sta/Elev= 30
       0   99.97    9.47   99.65   28.42   99.59   66.32   97.27   75.79   96.87
   85.27   96.93  113.69    98.7  123.16   97.98  132.64   95.84  151.58   93.55
  154.78 92.9031  161.06   91.63  170.53    90.2  182.5191.44923  199.67   91.89
  207.88   92.31  216.08   92.41  232.49   91.86   248.9   91.71  273.52    92.3
  306.34   92.13  314.55    92.2  322.76   92.54  330.96      93  347.37   94.55
  355.58   95.66  371.99   98.39   388.4   100.8  413.02   103.9  421.98  104.49
#Mann= 3 , 0 , 0
       0      .1       0  154.78    .045       0  182.51      .1       0
Bank Sta=154.78,182.51
XS Rating Curve= 0 ,0
Exp/Cntr=0.3,0.1

Type RM Length L Ch R = 1 ,2891.653,296.67,362.7,311.71
XS GIS Cut Line= 4
1573922.14930741695984.0137906521573811.65979627696255.904646486
1573833.32440633696326.3146290481573824.65856233696454.135828197
#Sta/Elev= 30
       0   91.13   37.78   87.99   45.34   87.57      68    87.2  120.89   85.48
  143.56   85.04  158.67   85.04  204.01   85.53  226.68   86.27  234.23   86.22
  272.01   85.28  293.48   85.16  300.81   84.91  310.8383.76916  315.46   83.31
  322.78   83.23  336.93   84.64  352.07   86.51  367.15   87.92  374.17   88.01
  381.18   87.34   388.2   85.97  395.22   85.11   430.3   87.12  437.31   87.69
  451.34   89.64  472.39   93.91  479.41   94.99  486.42   95.81  495.27   96.27
#Mann= 3 , 0 , 0
       0      .1       0  310.83    .045       0  336.93      .1       0
#XS Ineff= 2 , 0
                          369.65           89.12
Permanent Ineff=
       F       F
Bank Sta=310.83,336.93
XS Rating Curve= 0 ,0
Exp/Cntr=0.3,0.1

Type RM Length L Ch R = 1 ,2528.951,376.68,459.22,358.15
XS GIS Cut Line= 5
1573627.97509755695962.4840891061573559.34764619696100.630257487
1573527.26208448696187.0830208961573526.37081891696233.428832233
 1573516.5668973696407.225624681
#Sta/Elev= 30
       0   88.92    7.82   88.49   39.08   85.72   62.53   84.01  101.61   82.37
  125.06    81.9  140.69   80.95  169.19   80.26  206.52   80.34  221.45   79.43
  228.92    79.3  246.47   79.96  254.2779.78143  267.47   78.84  280.8879.42291
  327.88   82.19  334.89   82.44   341.9   82.02  348.91   82.18  355.92   82.02
  369.94   82.32  383.97   82.31     405   83.08  412.01   83.56  419.02   84.43
  426.03   85.68  440.06   89.14  447.07   90.34  454.08   90.94   466.9    90.9
#Mann= 3 , 0 , 0
       0      .1       0  254.27    .045       0  280.88      .1       0
Bank Sta=254.27,280.88
XS Rating Curve= 0 ,0
Exp/Cntr=0.3,0.1

Type RM Length L Ch R = 1 ,2069.734,202.37,193.49,170.11
XS GIS Cut Line= 4
1573185.01609322695956.2452299151573177.88596845696161.236318439
 1573185.9073588696220.0598481741573206.40646769696285.122237146
#Sta/Elev= 30
       0   88.43       7   87.48   21.01   85.19   35.02    84.2   49.03   82.21
   56.03   81.42   77.05    80.7   84.05   79.95   91.06   78.24   98.06   75.89
  105.06   74.28  126.08   72.47  136.2171.79984  147.09   71.14  154.09   71.51
  162.4972.87269   168.1   73.61  175.11   73.88  196.12    73.4  205.12   73.73
  226.31      74  233.37   73.95  254.57   75.33  271.82   75.96   286.5   76.88
  293.84   78.16  301.18   80.15  315.86   85.07   323.2   87.06   332.7   88.09
#Mann= 3 , 0 , 0
       0      .1       0  136.21    .045       0  162.49      .1       0
Bank Sta=136.21,162.49
XS Rating Curve= 0 ,0
Exp/Cntr=0.3,0.1

Type RM Length L Ch R = 1 ,1876.248,173.18,176.04,168
XS GIS Cut Line= 3
1572947.04817742696023.0901500881573068.26029934696351.967157319
1573118.17117305696394.747906253
#Sta/Elev= 30
       0   79.92   29.84   75.72   59.68   72.57   67.14   72.25   82.06   70.83
   96.98   70.63  128.4969.00748  141.75   67.58  154.6369.03577  164.13   69.54
  171.59   69.13  179.05   70.02  193.97      71  216.35   71.46  223.81   71.96
  246.19   72.48  261.11   73.31  276.03   73.08  290.95   73.54  305.87   74.62
  313.33   74.79  328.25   74.44  343.17   74.81   350.5   75.26  359.72   75.28
  368.94   75.65  378.16   76.22  387.38   77.48  405.82   80.53  416.24   81.78
#Mann= 3 , 0 , 0
       0      .1       0  128.49    .045       0  154.63      .1       0
Bank Sta=128.49,154.63
XS Rating Curve= 0 ,0
Exp/Cntr=0.3,0.1

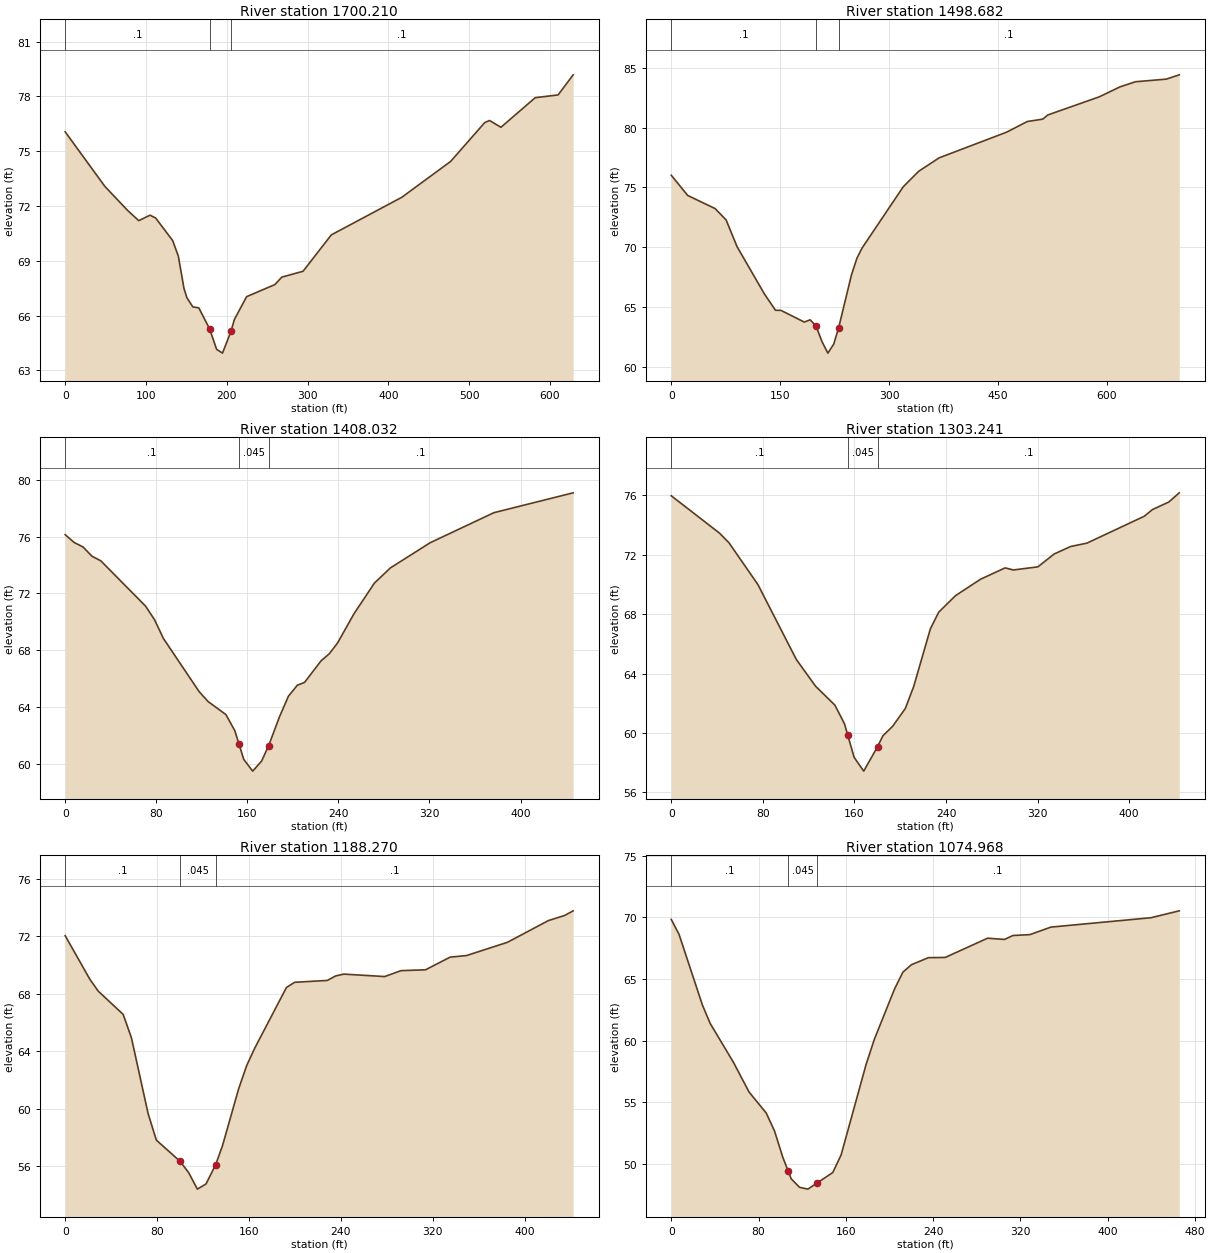
Type RM Length L Ch R = 1 ,1700.210,160.23,201.53,228.3
XS GIS Cut Line= 6
1572828.50985229696042.6979933231572830.29238348696193.321880117
1572852.57402357696263.731862709 1572978.2424735696432.181061536
1573029.04461285696507.0473721471573043.30486248696609.542916387
#Sta/Elev= 30
       0   76.06      49   73.08   77.01   71.77   91.01    71.2  105.01    71.5
  112.01   71.34  133.01   70.11  140.01   69.26  147.01   67.49  150.63   66.98
  157.98   66.48  165.32   66.43  178.7865.27128  187.35   64.16  194.69   63.95
  205.2465.15419  209.37   65.79  224.49   67.04  259.42    67.7  268.15   68.11
  294.35   68.43  329.29   70.42  416.62   72.48  476.94   74.44  519.24   76.57
  525.12   76.68  539.26   76.31  581.66   77.93  609.93   78.08  628.61   79.18
#Mann= 3 , 0 , 0
       0      .1       0  178.78    .045       0  205.24      .1       0
Bank Sta=178.78,205.24
XS Rating Curve= 0 ,0
Exp/Cntr=0.3,0.1

Type RM Length L Ch R = 1 ,1498.682,93.72,90.65,86.86
XS GIS Cut Line= 5
1572746.51341687696022.1988844871572680.55976231696184.409224108
1572639.56154464696253.9279410691572609.89817731696450.859740913
1572650.25673182696692.430617407
#Sta/Elev= 30
       0   76.01   22.67   74.32   60.45   73.22   75.56   72.27   90.68   70.03
  128.46   66.06  143.57   64.71  151.13    64.7  183.23   63.72  191.36   63.91
  199.49   63.38  207.61   62.09  215.74   61.12  223.87   61.88  230.68 63.2638
  248.25   67.67  255.81   69.07  262.89   69.92  319.52   75.04  340.76   76.34
  369.08   77.47  462.06   79.62  490.45   80.51  511.74   80.71  518.84   81.06
  589.81   82.58   618.2   83.41  639.49   83.84  682.07   84.06  699.89   84.42
#Mann= 3 , 0 , 0
       0      .1       0  199.49    .045       0  230.68      .1       0
Bank Sta=199.49,230.68
XS Rating Curve= 0 ,0
Exp/Cntr=0.3,0.1

Type RM Length L Ch R = 1 ,1408.032,102.12,104.79,107.58
XS GIS Cut Line= 4
1572653.22585145696037.8955402231572558.38150601696225.566266328
1572544.25575244696278.0333510341572546.27371721696459.650182739
#Sta/Elev= 30
       0   76.15    7.84    75.6   15.69   75.28   23.53   74.63   31.37    74.3
   70.59   71.11   78.43   70.16   86.27   68.83  117.65   65.08  125.49   64.38
  141.18   63.46  149.02   62.32  152.57   61.41  156.86    60.3  164.71   59.47
  172.55   60.18  178.76   61.27  188.24    63.3  196.08   64.75  203.92   65.53
  210.28   65.73  224.77   67.25  232.02   67.75  239.27   68.51  253.77   70.58
  271.61   72.73  285.61    73.8  320.61   75.58  376.62    77.7  446.24    79.1
#Mann= 3 , 0 , 0
       0      .1       0  152.57    .045       0  178.76      .1       0
Bank Sta=152.57,178.76
XS Rating Curve= 0 ,0
Exp/Cntr=0.3,0.1

Type RM Length L Ch R = 1 ,1303.241,118.24,114.97,109.86
XS GIS Cut Line= 4
1572578.95548369695998.1347132031572465.76475218696168.366443262
1572442.59184647 696245.015285061572474.67740817696400.986765444
#Sta/Elev= 30
       0   75.98   42.03   73.47   50.44   72.81   75.66      70  109.28   64.94
  126.09   63.14  142.91   61.87  151.31   60.61  154.1159.85756  159.72   58.35
  168.12   57.42  180.1659.06543  184.94   59.81  193.34   60.44  204.43   61.64
  211.74   63.12  226.37   67.02  233.68   68.14  248.31   69.25  270.24   70.36
  291.65   71.12   298.8   70.98  320.24   71.19  334.53   72.06  348.82   72.56
  363.12   72.79  413.14    74.6  420.29   75.05  434.58   75.56  443.74   76.18
#Mann= 3 , 0 , 0
       0      .1       0  154.11    .045       0  180.16      .1       0
Bank Sta=154.11,180.16
XS Rating Curve= 0 ,0
Exp/Cntr=0.3,0.1

Type RM Length L Ch R = 1 ,1188.270,127.87,113.3,96.02
XS GIS Cut Line= 5
1572417.12397024695972.3116843251572394.92635746696062.111117795
1572378.78263907696103.479396105 1572381.8095863696151.910551235
1572429.23175904696404.156150818
#Sta/Elev= 30
       0   72.04   21.63   68.99   28.84   68.18   50.47   66.57   57.69   64.93
   72.11   59.69   79.32   57.83  100.02   56.35  107.53   55.56  115.04   54.42
  122.56   54.78  130.91   56.11  136.91   57.44  150.94   61.39  157.95   63.01
  164.96   64.22  192.56   68.44  199.68    68.8  228.17   68.93  235.29   69.24
  242.42   69.37  278.03    69.2  292.27   69.61  313.64   69.67  335.01   70.55
  349.26   70.66  384.87   71.58  420.48   73.09  434.73   73.45   442.1   73.77
#Mann= 3 , 0 , 0
       0      .1       0  100.02    .045       0  130.91      .1       0
Bank Sta=100.02,130.91
XS Rating Curve= 0 ,0
Exp/Cntr=0.3,0.1

Type RM Length L Ch R = 1 ,1074.968,196.79,206.24,207.41
XS GIS Cut Line= 5
 1572247.4046796695977.635604352 1572263.6305383696063.118109196
1572307.11947493696163.910115242 1572372.1818639696300.273752391
1572386.44211353696417.029546291
#Sta/Elev= 30
       0   69.84    7.12   68.63    28.5   62.91   35.62   61.41      57   58.25
   71.25   55.85   87.01   54.14   94.63   52.68  102.26   50.54   107.249.41845
  109.88   48.81   117.5   48.12  125.13   47.97  133.2748.44317     148   49.32
  155.62   50.74  178.49   58.07  186.12   60.13  204.54   64.19  212.29   65.57
  220.05   66.17  235.56   66.74  251.07   66.76  289.85   68.32  305.37   68.22
  313.12   68.54  328.63   68.61  347.87   69.22  439.55   69.98   465.5   70.54
#Mann= 3 , 0 , 0
       0      .1       0   107.2    .045       0  133.27      .1       0
Bank Sta=107.2,133.27
XS Rating Curve= 0 ,0
Exp/Cntr=0.3,0.1