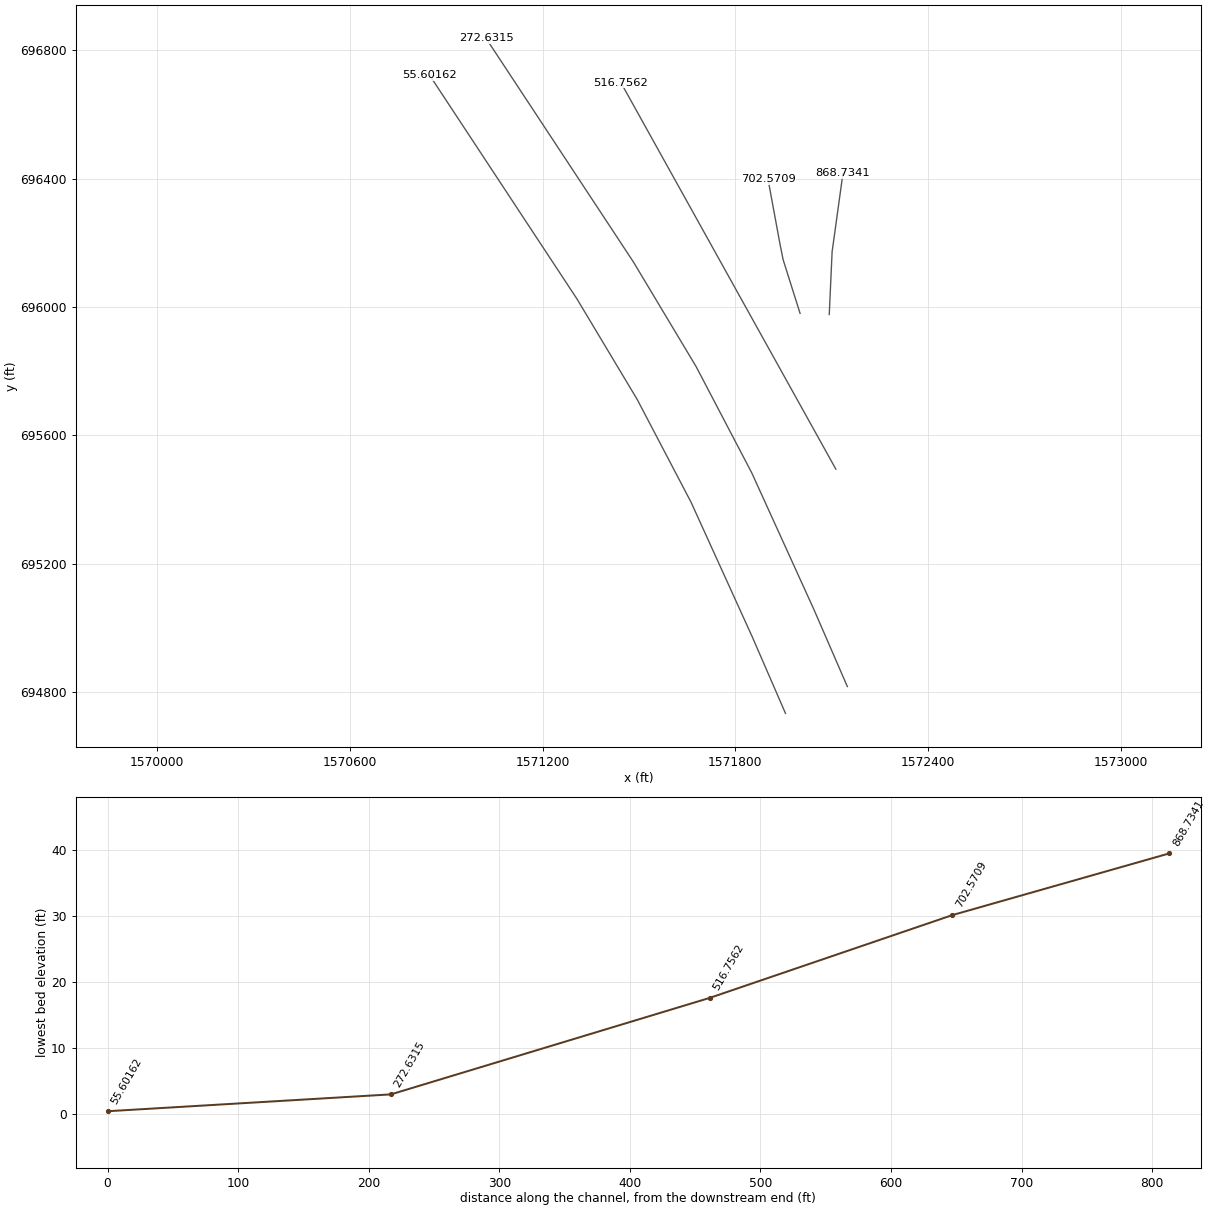
HEC-RAS study SusquehannaRiverTrib.prj: SusquehannaRiverTrib

--- SusquehannaRiverTrib.g01 (geometry) --- (continued)

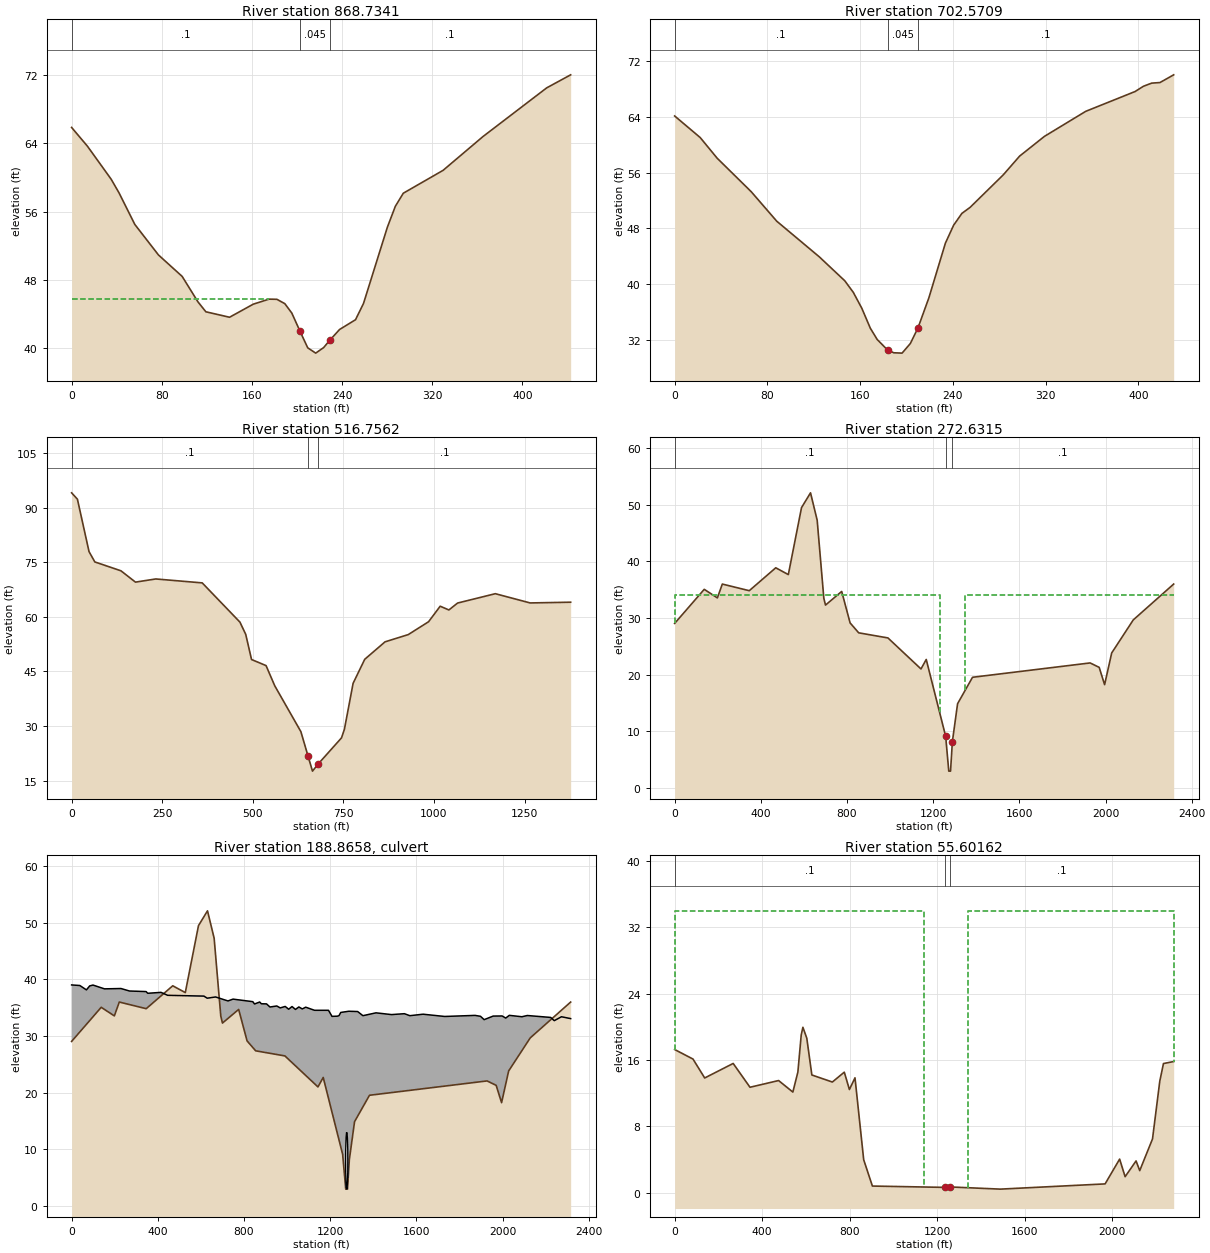
Type RM Length L Ch R = 1 ,868.7341,160.74,166.16,169.6
XS GIS Cut Line= 3
 1572092.3244648695976.7443387511572101.23712078 696171.93150565
1572135.10521367696417.029546291
#Sta/Elev= 30
       0   65.86   14.01   63.67   35.04   59.81   42.04   58.21   56.06   54.51
   77.08   50.93    98.1   48.42  112.12   45.44  119.12   44.28  140.15   43.64
  161.17   45.17  175.18   45.76  182.19   45.74   189.2   45.23  195.39   44.13
  202.7241.98635  209.52   40.06  216.59   39.44  223.66   40.09  228.8940.91969
  237.79   42.21  251.92   43.35  258.99   45.25  280.19   54.18  287.26   56.63
  294.32   58.16  329.65   60.84  364.99   64.79  421.52   70.49  442.82   72.02
#Mann= 3 , 0 , 0
       0      .1       0  202.72    .045       0  228.89      .1       0
#XS Ineff= 2 , 0
           175.3   45.76
Permanent Ineff=
       F       F
Bank Sta=202.72,228.89
XS Rating Curve= 0 ,0
Exp/Cntr=0.3,0.1

Type RM Length L Ch R = 1 ,702.5709,178.41,185.82,186.8
XS GIS Cut Line= 4
1572001.41537334695980.309401155 1571948.8307028 696146.97606881
1571939.91804682696190.648083299 1571901.5936259696398.312968642
#Sta/Elev= 30
       0   64.12   22.02   61.03    36.7   58.06   66.06   53.26   88.08   49.03
  124.78   43.92   146.8   40.48  154.14   38.82  161.48   36.54  168.82   33.68
  174.77   32.06   183.730.55713  189.05   30.16   196.2   30.11  203.34   31.49
  209.9233.72628  219.34   38.05  233.57   45.88  240.69   48.46  247.81   50.15
  254.93   51.02   283.4   55.66  297.64   58.37  318.99   61.19  354.58   64.78
  397.29   67.63  404.41   68.38  411.53   68.83  418.65   68.91  430.51   70.02
#Mann= 3 , 0 , 0
       0      .1       0   183.7    .045       0  209.92      .1       0
Bank Sta=183.7,209.92
XS Rating Curve= 0 ,0
Exp/Cntr=0.3,0.1

Type RM Length L Ch R = 1 ,516.7562,234.62,244.12,231.91
XS GIS Cut Line= 2
1572112.86348106695495.1616079211571443.50971124 696698.88896741
#Sta/Elev= 30
       0   94.07   16.02   92.32   48.06   77.92   64.08   75.08  136.16   72.64
  176.21   69.53  232.27    70.4  360.43   69.32  464.55   58.54  480.57   55.17
  496.59   48.26  536.63   46.59  560.66   41.04  632.75   28.44  652.4321.74878
  664.79   17.59  680.5319.55821  744.88   26.73  752.89   29.09  776.92   41.73
  808.96   48.32  865.02   53.12   929.1   55.11  985.16   58.64  1017.2   62.91
 1041.23   61.88 1065.26   63.78 1169.38   66.35 1265.49   63.81 1377.31   64.01
#Mann= 3 , 0 , 0
       0      .1       0  652.43    .045       0  680.53      .1       0
Bank Sta=652.43,680.53
XS Rating Curve= 0 ,0
Exp/Cntr=0.5,0.3

Type RM Length L Ch R = 1 ,272.6315,210.01,217.03,210.42
BEGIN DESCRIPTION:
Channel bottom lowered to meet culvert invert based on study assumption that any deposition in culvert will be removed by flow prior to peak of a 100-yr flood event.  The bridge/culvert survey photos show channel invert above culvert invert at upstream end of culvert.
END DESCRIPTION:
XS GIS Cut Line= 6
1572148.66656485694818.1864611211572044.44393662 695058.27072978
  1571851.179665695483.2409781811571677.61726798695814.696821794
1571483.05142601696139.3534971481571023.65540987696836.659706101
#Sta/Elev= 30
       0   29.05  137.36   35.06  198.41   33.55   221.3   35.99  346.33   34.82
  469.39   38.86  527.67   37.66   588.9   49.47   630.7   52.08  661.57   47.25
  692.45    33.5  700.17   32.28  775.39   34.69  814.39   29.14   854.3   27.39
  989.99   26.49 1143.43   21.02 1167.82   22.69 1258.019.131591 1272.43       3
  1280.6       3 1289.05 8.17833 1313.29   14.89 1382.66   19.55 1928.49   22.08
 1970.51    21.3 1995.72   18.25 2028.64   23.84  2128.8   29.67 2316.35   35.99
#Mann= 3 , 0 , 0
       0      .1       0 1258.01    .045       0 1289.05      .1       0
#XS Ineff= 2 , 0
       0 1231.31      34 1348.42       0      34
Permanent Ineff=
       F       F
Bank Sta=1258.01,1289.05
XS Rating Curve= 0 ,0
Exp/Cntr=0.5,0.3

Type RM Length L Ch R = 2 ,188.8658,,,
BEGIN DESCRIPTION:
Railroad
MDE Bridge #: CE033108FS-3
Top of road obtained from DEM.
Opening estimated from MDE2 bridge/culvert surveys photos and limited structure data (culvert size and invert were not provided).
END DESCRIPTION:
Bridge Culvert--1,0,-1,-1, 0
Deck Dist Width WeirC Skew NumUp NumDn MinLoCord MaxHiCord MaxSubmerge Is_Ogee
80,46,2.6,0, 60, 60, , , 0.95, 0, 2,2,,
       0   38.16   68.68   83.94    99.2  152.62  228.93  268.72  345.63  353.32
  414.85  445.61  613.96   629.4  667.99  725.68  749.08  841.06  849.01  872.87
  880.82  904.68  920.58  952.39  968.29  991.45 1007.28 1023.12 1038.95 1054.79
 1070.63 1086.46 1127.28 1192.31 1208.57 1232.96 1241.09 1249.22 1286.69 1327.55
 1352.06 1412.82 1485.03 1544.49 1569.98 1631.28 1731.58 1872.66 1897.87 1914.68
 1956.69 1998.22 2014.91  2031.6 2090.03 2115.07 2223.58 2240.27 2273.66 2316.35
   39.01   38.91   38.14   38.84   38.99   38.32   38.38   37.94   37.84   37.54
    37.7   37.18   37.04   36.67   36.89   36.19   36.51   36.06   35.65      36
   35.69   35.67   35.12    35.3   34.96   35.22   34.73    35.2   34.69   35.13
   34.78   35.09   34.54   34.54   33.47    33.5    33.6   34.16   34.37   34.32
   33.59   34.09   33.78   33.94   33.59   33.85   33.45   33.64   33.48   32.89
   33.52   33.54   33.17   33.65    33.4   33.62   33.28   32.71    33.4   33.07
                                                                                
                                                                                
                                                                                
                                                                                
                                                                                
                                                                                
       0   38.16   68.68   83.94    99.2  152.62  228.93  268.72  345.63  353.32
  414.85  445.61  613.96   629.4  667.99  725.68  749.08  841.06  849.01  872.87
  880.82  904.68  920.58  952.39  968.29  991.45 1007.28 1023.12 1038.95 1054.79
 1070.63 1086.46 1127.28 1192.31 1208.57 1232.96 1241.09 1249.22 1286.69 1327.55
 1352.06 1412.82 1485.03 1544.49 1569.98 1631.28 1731.58 1872.66 1897.87 1914.68
 1956.69 1998.22 2014.91  2031.6 2090.03 2115.07 2223.58 2240.27 2265.31  2281.4
   39.01   38.91   38.14   38.84   38.99   38.32   38.38   37.94   37.84   37.54
    37.7   37.18   37.04   36.67   36.89   36.19   36.51   36.06   35.65      36
   35.69   35.67   35.12    35.3   34.96   35.22   34.73    35.2   34.69   35.13
   34.78   35.09   34.54   34.54   33.47    33.5    33.6   34.16   34.37   34.32
   33.59   34.09   33.78   33.94   33.59   33.85   33.45   33.64   33.48   32.89
   33.52   33.54   33.17   33.65    33.4   33.62   33.28   32.71   33.33   33.37
                                                                                
                                                                                
                                                                                
                                                                                
                                                                                
                                                                                
BR Coef=-1 , 0 , 0 ,, 0 ,,,0.8,0,,0,
WSPro=,,,, 1 ,,,, 0 ,,,, 0 ,,,,-1 ,-1 ,-1 , 0 , 0 , 0 , 0 , 0
Culvert=1,10,,150,0.015,0.5,1,1,1,3,1277,3,1244,Culvert #1  , 0 ,33.5
Culvert Bottom n=0.015
BC Design=,, 0 ,, 0 ,,,,,,
BC Use User HTab Curves=0
BC User HTab FreeFlow(D)= 0

Type RM Length L Ch R = 1 ,55.60162,47.75,55.6,50.53
BEGIN DESCRIPTION:
Channel bottom left as obtained from the DEM since the bridge/culvert survey info did not provide any information.
END DESCRIPTION:
XS GIS Cut Line= 6
1571956.03440315694734.5631971361571852.54658636694972.954775184
1571661.70748267 695392.656689511571494.27540502 695712.17725867
1571306.76943167696025.0843377261570847.53693321696722.281901538
#Sta/Elev= 30
       0   17.28   83.94   16.13  137.36   13.85  267.58    15.6  344.49   12.73
  475.23   13.54   540.4   12.15  563.36   14.56  578.67   19.04  586.33   19.96
  604.13   18.65  627.29   14.21  720.95   13.36  775.55   14.55  798.95   12.46
  824.51   13.87  864.27    3.99  904.04     .82 1234.24.6600324 1260.24.7116769
 1488.99     .45 1967.86    1.08 2034.33    4.07 2059.37    1.95 2109.45    3.85
 2126.14    2.68 2184.57     6.5 2217.96   13.48 2234.65   15.59  2281.4   15.83
#Mann= 3 , 0 , 0
       0      .1       0 1234.24    .045       0 1260.24      .1       0
#XS Ineff= 2 , 0
       0    1140      34    1340       0      34
Permanent Ineff=
       F       F
Bank Sta=1234.24,1260.24
XS Rating Curve= 0 ,0
Exp/Cntr=0.5,0.3

Chan Stop Cuts=-1
Use User Specified Reach Order=0
User Specified Reach Order=SusquehannaTrib ,Reach1