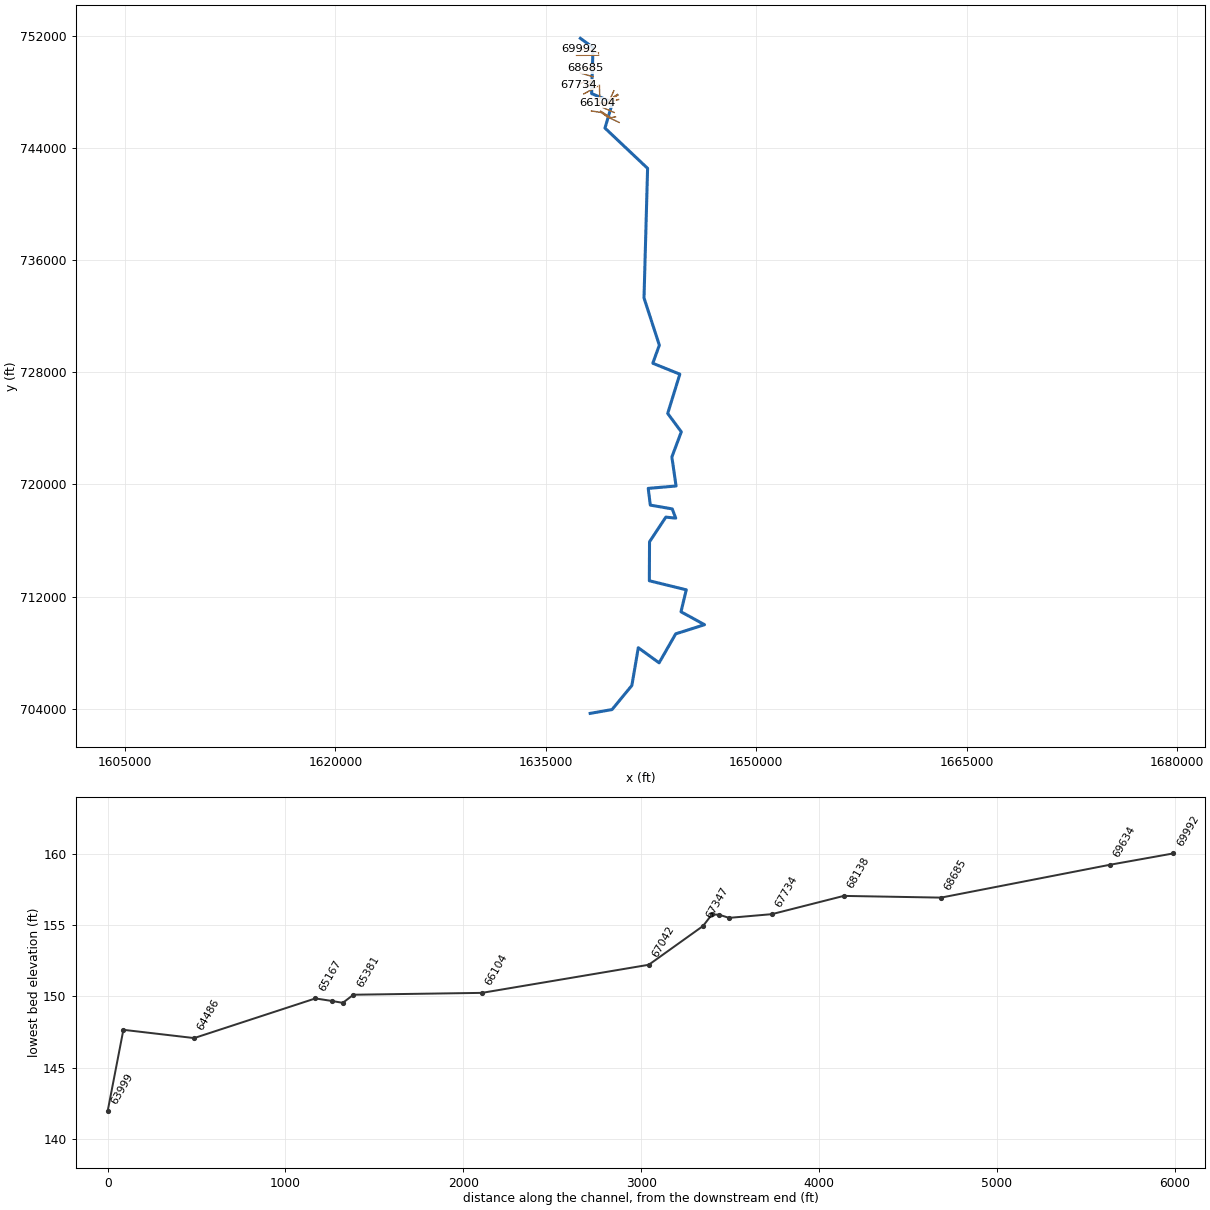
--- bigelkcreek.prj (project) ---

Proj Title=Big Elk Creek
Current Plan=p15
Default Exp/Contr=0.3,0.1
English Units
Geom File=g23
Flow File=f01
Flow File=f02
Plan File=p15
Plan File=p16
Y Axis Title=Elevation
X Axis Title(PF)=Main Channel Distance
X Axis Title(XS)=Station
BEGIN DESCRIPTION:
Big Elk Creek - Georeferenced HEC-RAS model.
Projection:  MD Stateplane.  Horizontal datum:  NAD83.  Vertrial datum: NAVD88.  Units:Feet.  Created by: Ann Banitt, USACE- St Paul District as part of FEMA Map Modernization study for Cecil County, MD.
The lower portions of this model were once detailed studies.  Two existing HEC2 models were provided my MDE.
1.  BigElk2.dat Delaware Avenue to the Farrs Creek Weir
2. Big Elk Creek  Conrail upstream to JFK Memorial Hwy.
Discussions with a representative from MDE and the USACE hydraulics chief in Baltimore,MD, it was determined that it woudl be adviseable to extend the hydraulic model downstream  to Bridge Street  A non-georeferenced HEC-RAS model was obtained from USACE, Baltmore District.  The model extends from US40 upstream to upstream of Farrs Creek Dam.
The under water portion of the cross sections in this model were copied from the existing HEC2 and Baltimore RAS models where available.
Stream cross sections used in the Baltimore District HEC-RAS model were a combination of sections surveyed for the Elkton study and data obtained from other sources, such as the Federal Emergency Management Agency (FEMA), Maryland Department of Transportation (MDOT).  The vertical datum was NGVD29 - and converted to NAVD88 for this study.
END DESCRIPTION:
DSS File=dss
DSS Export Rating Curves= 0
DSS Export Rating Curve Sorted= 0
DSS Export Volume Flow Curves= 0
DXF OffsetX= 0
DXF OffsetY= 0
DXF ScaleX= 1
DXF ScaleY= 10

--- bigelkcreek.p15 (plan) ---

Plan Title=Big Elk Creek - Frequency Profiles
Program Version=4.00
Short Identifier=Big Elk Cree
Geom File=g23
Flow File=f01
Subcritical Flow
K Sum by GR= 0
Std Step Tol= 0.01
Critical Tol= 0.01
Num of Std Step Trials= 20
Max Error Tol= 0.3
Flow Tol Ratio= 0.001
Split Flow NTrial= 30
Split Flow Tol= 0.02
Split Flow Ratio= 0.02
Log Output Level= 0
Friction Slope Method= 1
Unsteady Friction Slope Method= 2
Unsteady Bridges Friction Slope Method= 1
Secant Critical Depth
Global Vel Dist= 0 , 0 , 0
Global Log Level= 0
CheckData=True
Encroach Param=-1 ,0,0, 0
Computation Interval=1HOUR
Output Interval=1HOUR
Run HTab= 0
Run UNet= 0
Run PostProcess= 0
Run WQNet= 0
UNET Theta= 1
UNET Theta Warmup= 1
UNET ZTol= 0.02
UNET ZSATol= 0.05
UNET MxIter= 20
UNET MaxInSteps= 0
UNET DtIC= 0
UNET DtMin= 0
UNET MaxCRTS= 20
UNET WFStab= 2
UNET SFStab= 1
UNET WFX= 1
UNET SFX= 1
UNET DSS MLevel= 4
UNET DZMax Abort= 100
UNET Convert EG Bridges= 0
UNET Use Existing IB Tables=-1
UNET Froude Reduction=False
UNET Froude Limit= 1
UNET Froude Power= 10
UNET Time Slicing=0,0, 5
Instantaneous Interval=1HOUR
DSS File=dss
Write IC File= 0
Echo Input=False
Echo Output=False
Write Detailed= 0
Detailed Automatic Start=False, 10
WQ ULTIMATE=-1
WQ Max Comp Step=1HOUR
WQ Output Interval=15MIN
WQ Output Selected Increments= 0
WQ Output face flow=0
WQ Output face velocity=0
WQ Output face area=0
WQ Output face dispersion=0
WQ Output cell volume=0
WQ Output cell surface area=0
WQ Output cell continuity=0
WQ Output face conc=0
WQ Output face dconc_dx=0
WQ Output face courant=0
WQ Output face peclet=0
WQ Output face adv mass=0
WQ Output face disp mass=0
WQ Output cell mass=0
WQ Output cell source sink temp=0
WQ Output cell source sink nsm=0
WQ Output MaxMinRange=-1
WQ Daily Max Min Mean=-1
WQ Daily Range=0
WQ Daily Time=0
WQ Create Restart=0
WQ Fixed Restart=0
WQ System Summary=False
Sorting and Armoring Iterations= 10
XS Update Threshold= 0.02
Hydraulics Update Threshold= 0.02
Energy Slope Method= 0
Volume Change Method= 0
XS Weighting Method= 0
Number of US Weighted Cross Sections= 1
Number of DS Weighted Cross Sections= 1
Upstream XS Weight=0.25
Main XS Weight=0.5
Downstream XS Weight=0.25
Number of DS XS's Weighted with US Boundary= 1
Upstream Boundary Weight= 1
Weight of XSs Associated with US Boundary= 0
Number of US XS's Weighted with DS Boundary= 1
Downstream Boundary Weight= 0.5
Weight of XSs Associated with DS Boundary= 0.5
Sediment Output Level= 4
Mass or Volume Output= 0
Output Increment Type= 1
Profile and TS Output Increment= 10
XS Output Flag= 0
XS Output Increment= 10
Disregard all LS=0
Disregard all Conn=0
Disregard all Breaches=0
Disregard all Pumps=0

--- bigelkcreek.p16 (plan) ---

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Plan Title=Big Elk Creek - Floodway
Short Identifier=Big Elk FW
Geom File=g23
Flow File=f02
Encroach Param=-1 ,0,0, 2
Encroach River=BigElkCreek
Encroach Reach=One
Encroach Node=35059
       1    1450    2100
Encroach Node=34893
       1    1730    1969
Encroach Node=34641
       1    1740    1950
Encroach Node=34539
       1    1480    1960
Encroach Node=33838
       1    1510 2204.97
Encroach Node=33051
       1    1050  1352.7
Encroach Node=32664
       1    1310    1573
Encroach Node=32355
       1     730     932
Encroach Node=32271
       1  666.56  765.13
Encroach Node=32220
       1  662.61  769.06
Encroach Node=31782
       1     450     730
Encroach Node=30744
       1     610 1138.15
Encroach Node=29832
       1     630  970.16
Encroach Node=29196
       1 1093.93    1500
Encroach Node=28571
       1  581.29  909.45
Encroach Node=28116
       1     650  991.85
Encroach Node=27608
       1  446.96 1057.65
Encroach Node=27091
       1  774.35 1582.13
Encroach Node=26532
       1    2750 3802.95
Encroach Node=25392
       1    3250 3646.95
Encroach Node=25303
       1    1950    2440
Encroach Node=25233
       1 1853.27    2523
Encroach Node=25131
       1    1320    2000
Encroach Node=23986
       1    1605    1980
Encroach Node=23465
       1 1935.54 2255.51
Encroach Node=22629
       1  2127.9 2468.74
Encroach Node=22181
       1    2340 2573.99
Encroach Node=21517
       1    2300 2507.33
Encroach Node=21427
       1    2352    2512
Encroach Node=21266
       1    2355 2531.64
Encroach Node=21194
       1    2210 2697.17
Encroach Node=20845
       1    1450    2515
Encroach Node=20555
       1    1380 2600.71
Encroach Node=20116
       1    1440  2669.8
Encroach Node=19470
       1    1450 2311.69
Encroach Node=19077
       1    1630    1980
Encroach Node=19008
       1    1683    1949
Encroach Node=18837
       1    1625    1801
Encroach Node=18769
       1 1574.75 1705.54
Encroach Node=18570
       1    1400 1606.09
Encroach Node=18420
       1    1180 1299.08
Encroach Node=18309
       1     900 1247.27
Encroach Node=18008
       1     700    1409
Encroach Node=17712
       1     700    1450
Encroach Node=17426
       1  603.75    1380
Encroach Node=16975
       1 1071.93    1700
Encroach Node=16639
       1 1242.71    2015
Encroach Node=16378
       1 1428.13    2200
Encroach Node=15642
       1 1762.03    2520
Encroach Node=15247
       1    1480 2349.01
Encroach Node=14850
       1 1595.87 2545.87
Encroach Node=14790
       1 1694.68 2549.87
Encroach Node=14762
       1 1694.68 2549.87
Encroach Node=14725
       1 1876.12 2617.99
Encroach Node=14638
       1 1519.76 2154.76
Encroach Node=14448
       1    1400    2015
Encroach Node=14373
       1    1160    1930
Encroach Node=13989
       1     700    2300
Encroach Node=13697
       1  913.75    2380
Encroach Node=13563
       1  913.04    2370
Encroach Node=13453
       1 1281.69    2700
Encroach Node=13017
       1 1130.21 2579.85
Encroach Node=12438
       1 1101.81    2070
Encroach Node=12131
       1 1067.38 1881.42
Encroach Node=11849
       1   941.6 1816.86
Encroach Node=11721
       1    1020 1962.07
Encroach Node=11607
       1     880 1834.03
Encroach Node=11494
       1     800 1749.31
Encroach Node=11299
       1     800 1855.66
Encroach Node=11264
       1     820 1890.18
Encroach Node=11161
       1  766.34 1921.13
Encroach Node=11102
       1  749.37 1961.98
Encroach Node=10733
       1    1000  2512.4
Encroach Node=10277
       1 1123.41    2664
Encroach Node=9900
       1  472.59    2385
Encroach Node=9850
       1     450    2385
Encroach Node=9810
       1     450    2370
Encroach Node=9760
       1     450    2400
Encroach Node=9158
       1  621.16 2705.89
Encroach Node=8411
       1  861.05    2500
Encroach Node=7601
       1 1085.88    2400
Encroach Node=6818
       1 1135.06 2178.59
Encroach Node=6317
       1 1066.05 2100.91
Encroach Node=6223
       1    1040 2071.42
Encroach Node=6133
       1    1020 2070.69
Encroach Node=6011
       1     980  2010.2
Encroach Node=5916
       1     950    1980
Encroach Node=5675
       1 1037.01 2022.18
Encroach Node=5455
       1    1300 1951.45
Encroach Node=5242
       1    1435    1930
Encroach Node=5038
       1    1520    1880
Encroach Node=4805
       1    1400    1700
Encroach Node=4739
       1    1450    1800
Encroach Node=4473
       1    1285    1630
Encroach Node=4367
       1 1156.48 1525.17
Encroach Node=4024
       1     850    1460
Encroach Node=3744
       1  411.83 1490.46

--- bigelkcreek.f01 (steady flow) ---

Flow Title=Big Elk -  Frequency Profiles
Program Version=4.00
Number of Profiles= 5
Profile Names=10Ycur,50Ycur,100Ycur,500Ycur,100Yult
River Rch & RM=BigElkCreek,One             ,69992
    6420   12500   16100   27600   16300
River Rch & RM=BigElkCreek,One             ,65261
    6420   12500   16100   27600   16500
River Rch & RM=BigElkCreek,One             ,63414
    6430   12500   16100   27600   16700
River Rch & RM=BigElkCreek,One             ,62308
    6430   12500   16100   27600   16800
River Rch & RM=BigElkCreek,One             ,55500
    6440   12500   16100   27600   17200
River Rch & RM=BigElkCreek,One             ,55209
    6450   12500   16100   27600   17300
River Rch & RM=BigElkCreek,One             ,52458
    6470   12500   16100   27600   17500
River Rch & RM=BigElkCreek,One             ,49507
    6490   12600   16200   27700   16200
River Rch & RM=BigElkCreek,One             ,47449
    6630   12800   16500   28200   18300
River Rch & RM=BigElkCreek,One             ,44440
    6720   13000   16700   28500   18600
River Rch & RM=BigElkCreek,One             ,38055
    6766   13103   16806   28616   18996
River Rch & RM=BigElkCreek,One             ,35313
    6782   13109   16817   28739   19093
River Rch & RM=BigElkCreek,One             ,23465
    6903   13366   17210   29439   19600
River Rch & RM=BigElkCreek,One             ,19077
    6923   13478   17332   29589   19615
River Rch & RM=BigElkCreek,One             ,17712
    7006   13680   17675   30198   19847
Boundary for River Rch & Prof#=BigElkCreek,One             , 1
Up Type= 0
Dn Type= 3
Dn Slope=0.00067
Boundary for River Rch & Prof#=BigElkCreek,One             , 2
Up Type= 0
Dn Type= 3
Dn Slope=0.00067
Boundary for River Rch & Prof#=BigElkCreek,One             , 3
Up Type= 0
Dn Type= 3
Dn Slope=0.00067
Boundary for River Rch & Prof#=BigElkCreek,One             , 4
Up Type= 0
Dn Type= 3
Dn Slope=0.00067
Boundary for River Rch & Prof#=BigElkCreek,One             , 5
Up Type= 0
Dn Type= 3
Dn Slope=0.00067
DSS Import GetInterval= 0
DSS Import GetPeak= 0
DSS Import FillOption= 0

--- bigelkcreek.f02 (steady flow) ---

Flow Title=Big Elk -  Floodway
Program Version=4.00
Number of Profiles= 2
Profile Names=100Ycur,Floodway
River Rch & RM=BigElkCreek,One             ,69992
   16100   16100
River Rch & RM=BigElkCreek,One             ,65261
   16100   16100
River Rch & RM=BigElkCreek,One             ,63414
   16100   16100
River Rch & RM=BigElkCreek,One             ,62308
   16100   16100
River Rch & RM=BigElkCreek,One             ,55500
   16100   16100
River Rch & RM=BigElkCreek,One             ,55209
   16100   16100
River Rch & RM=BigElkCreek,One             ,52458
   16100   16100
River Rch & RM=BigElkCreek,One             ,49507
   16200   16200
River Rch & RM=BigElkCreek,One             ,47449
   16500   16500
River Rch & RM=BigElkCreek,One             ,44440
   16700   16700
River Rch & RM=BigElkCreek,One             ,38055
   16806   16806
River Rch & RM=BigElkCreek,One             ,35313
   16817   16817
River Rch & RM=BigElkCreek,One             ,23465
   17210   17210
River Rch & RM=BigElkCreek,One             ,19077
   17332   17332
River Rch & RM=BigElkCreek,One             ,17712
   17675   17675
Boundary for River Rch & Prof#=BigElkCreek,One             , 1
Up Type= 0
Dn Type= 3
Dn Slope=0.00067
Boundary for River Rch & Prof#=BigElkCreek,One             , 2
Up Type= 0
Dn Type= 3
Dn Slope=0.00067
DSS Import GetInterval= 0
DSS Import GetPeak= 0
DSS Import FillOption= 0

--- bigelkcreek.g23 (geometry) ---

Geom Title=Big Elk Creek Geometry
Program Version=4.00

River Reach=BigElkCreek     ,One
Reach XY= 30
1637457.10478756751813.2040194571638358.35516116751158.697954237
1638258.22511214747872.2107608021639753.38649185747252.620464563
1639210.40488441745412.0647567661642248.39577949742539.840416312
1641993.21993871733295.8399792161643086.79200763 729928.83099243
1642619.11501235728638.8745556471644547.11673377727859.787531152
1643681.11518492725059.0483819691644652.26973869723747.673051983
1643978.33539103721952.1080735621644277.86169484719883.305124551
1642293.49952187719714.423244461 1642443.2626738718521.097547144
1644005.41998252718250.2493355571644253.96312062 717592.24737072
1643548.16433534717664.7390236561642386.70340371715906.614915222
1642373.16077985713125.6401622151645005.43438672712480.118487388
1644629.83238158 710914.506879241646308.70638643709992.275365964
1644251.20590828709338.6336286521643068.51076709707271.027855739
 1641584.7053358708350.6241217261641128.90506625705660.305027306
1639714.10048121703938.8199532331638155.44316545 703667.05015555

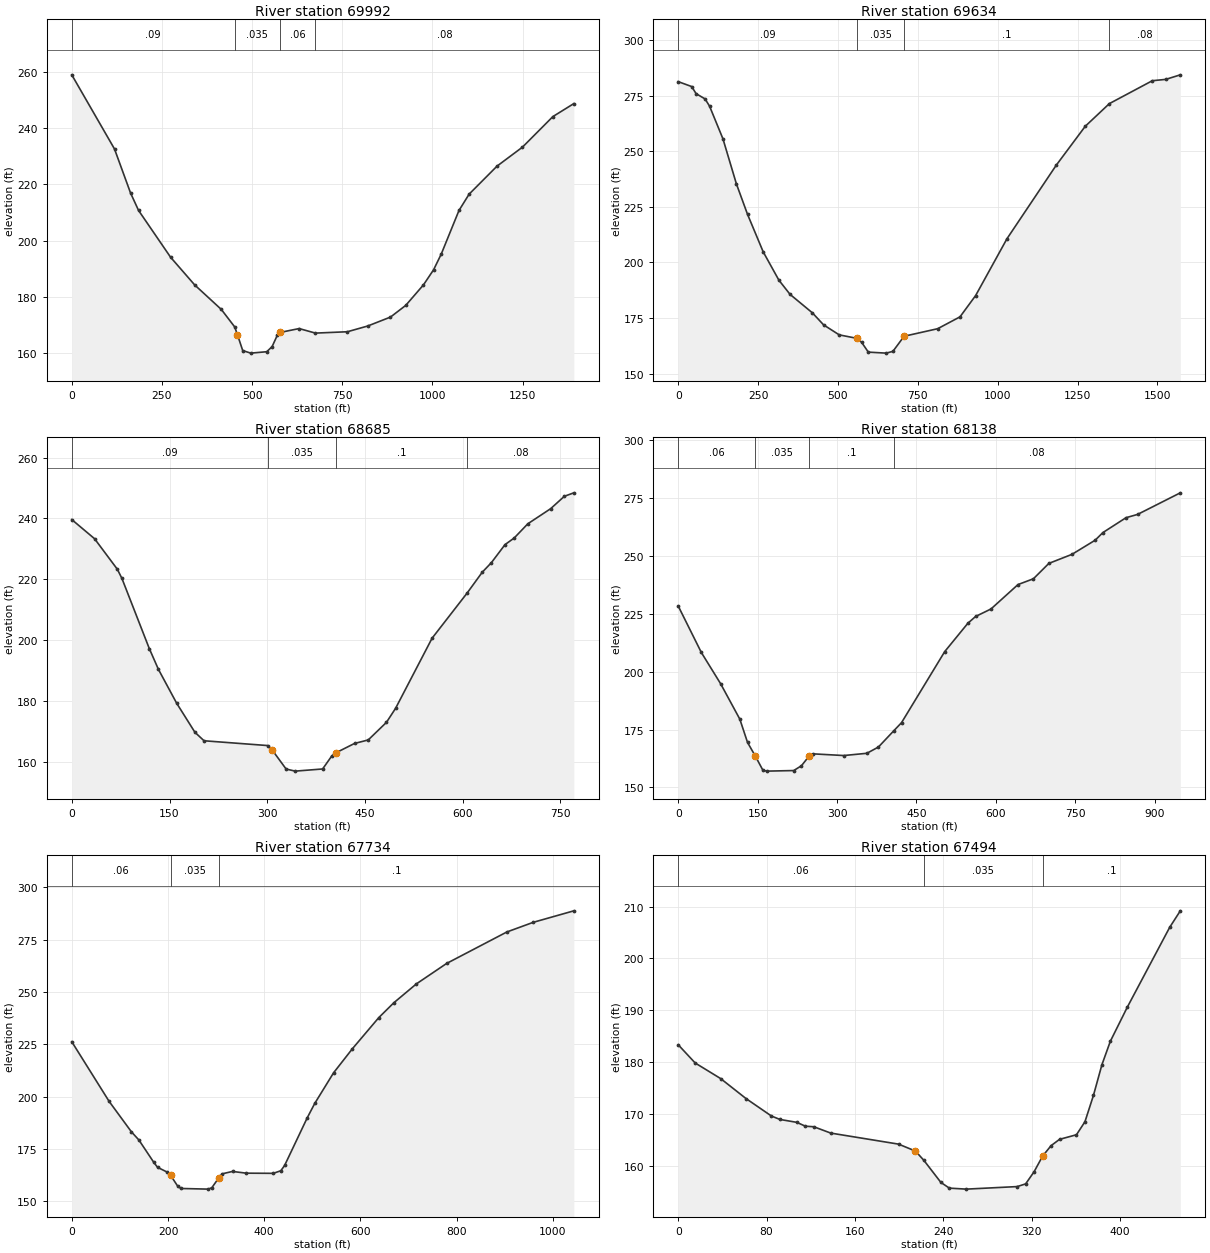
Type RM Length L Ch R = 1 ,69992   ,342,358.61,388.08
XS GIS Cut Line= 3
1638743.58577432750770.0335008061638187.60779428750962.058045045
1637387.72372019751041.205911621
#Sta/Elev= 30
       0  258.83  118.49   232.5  162.93  216.89  185.14  210.69  274.01  194.06
  340.66  184.25  414.72  175.52  451.75  169.32  459.16  166.62  473.97  160.93
  496.19  160.02  540.62  160.52  555.43  162.34  570.24  166.47  577.65  167.37
  630.41  168.74  675.54  167.13  764.06  167.61  820.33  169.64  883.64  172.82
  925.85  176.96  975.09  184.26 1003.22  189.63 1024.32  195.17 1073.56  210.68
  1101.7  216.47 1179.08  226.42 1249.42  233.14 1333.83     244    1392  248.62
#Mann= 4 ,-1 , 0
       0     .09       0  451.75    .035       0  577.65     .06       0
  675.54     .08       0
Bank Sta=459.16,577.65
XS Rating Curve= 0 ,0
Exp/Cntr=0.3,0.1

Type RM Length L Ch R = 1 ,69634   ,936.62,948.29,935.72
XS GIS Cut Line= 2
1638754.61248583750603.2630308871637183.02431732750598.193391621
#Sta/Elev= 30
       0  281.33      42  279.13      56  275.92      84  273.56      98  270.32
     140  255.59     182  235.38     217  221.61     266  204.76     315  192.05
     350  185.65     420  177.33     455  171.93     504  167.43     560  165.85
     574  164.09     595  159.67     651  159.22     672  160.02     707  166.81
  812.01   170.2  882.01  175.54  931.01  185.14 1029.01  210.68 1183.01   243.7
 1274.01  261.25 1349.53  271.45 1484.01  281.75 1526.01  282.35 1571.59   284.4
#Mann= 4 ,-1 , 0
       0     .09       0     560    .035       0     707      .1       0
 1349.53     .08       0
Bank Sta=560,707
XS Rating Curve= 0 ,0
Exp/Cntr=0.3,0.1

Type RM Length L Ch R = 1 ,68685   ,562.5,546.99,514.01
XS GIS Cut Line= 2
1638556.89655496749670.4494082781637786.31138848749675.519047543
#Sta/Elev= 30
       0  239.61      35  233.31      70  223.26      77  220.25     119   197.2
     133  190.37     161  179.24     189  169.69     203   166.9  301.01  165.32
  308.01  163.75  329.01   157.6  343.01  156.92  385.01  157.63  399.01  161.89
  406.01  163.01  434.01  166.02  455.01  167.17  483.01  172.96  497.01  177.57
  553.01  200.61  606.54  215.38  630.01   222.3  644.01  225.44  665.01  231.39
  679.01  233.54  700.01  238.23  735.02  243.19  756.02  247.26   770.6   248.4
#Mann= 4 ,-1 , 0
       0     .09       0  301.01    .035       0  406.01      .1       0
  606.54     .08       0
Bank Sta=308.01,406.01
XS Rating Curve= 0 ,0
Exp/Cntr=0.3,0.1

Type RM Length L Ch R = 1 ,68138   ,386.74,404.27,412.3
XS GIS Cut Line= 3
1638345.52971028 749083.445252971637917.15865934749204.731032446
1637433.65099761749345.369832382
#Sta/Elev= 30
       0   228.4   43.65  208.33   80.03  194.85   116.4   179.5  130.95  169.44
   145.5  163.61  160.05   157.4  167.33  157.04  218.25  157.29  232.81  159.36
  247.36  163.55  254.63  164.51  312.83  163.78  356.48  164.75  378.31  167.46
   407.3  174.48  421.96  177.99  503.53   208.7  547.27  220.95  561.85  223.89
  591.01  227.14  642.04  237.69   671.2   240.2  700.36  246.84   744.1  250.76
  787.85  256.87  802.43  260.16  846.17   266.6  868.04  268.02  948.76  277.35
#Mann= 4 ,-1 , 0
       0     .06       0   145.5    .035       0  247.36      .1       0
   407.3     .08       0
Bank Sta=145.5,247.36
XS Rating Curve= 0 ,0
Exp/Cntr=0.3,0.1

Type RM Length L Ch R = 1 ,67734   ,197.47,240.7,286.1
XS GIS Cut Line= 4
1638266.56875226748823.5320995751638093.84165666748741.281101674
1637878.34404218748784.0516205881637312.99123774 748500.67170909
#Sta/Elev= 30
       0  226.25   77.53  197.75  124.05  183.13  139.56  179.24  170.57  168.52
  178.32  166.18  198.45  163.88  205.58  162.29  219.86  157.28  226.99  156.07
  284.09  155.76  291.22  156.48   305.5  161.14  312.63  163.08  334.04  164.22
  362.59  163.39  418.84  163.31   434.5  164.56  442.33  167.08  489.31  189.85
  504.97  196.75  544.12   211.4  583.27  222.91  638.09  237.79  669.41   244.9
  716.39  253.94  779.03  263.68  904.31  278.74  959.12  283.35 1043.41  288.84
#Mann= 3 , 0 , 0
       0     .06       0  205.58    .035       0   305.5      .1       0
Bank Sta=205.58,305.5
XS Rating Curve= 0 ,0
Exp/Cntr=0.3,0.1

Type RM Length L Ch R = 1 ,67494   ,54.8,55.94,52.08
XS GIS Cut Line= 2
 1638238.8075535748625.0135237571637824.02294008748439.008548737
#Sta/Elev= 30
       0  183.34   15.34  179.83   38.36  176.83   61.37  172.97   84.39   169.6
   92.06  168.94   107.4  168.38  115.07  167.64  122.75  167.53  138.09  166.31
  199.46  164.18  214.81  162.84  222.48  161.03  237.82  156.79  245.49  155.69
  260.83   155.5  306.86  155.99  314.54  156.51  322.21  158.86  329.88  161.86
  337.55  163.88  345.22   165.1  360.57  165.99  368.24   168.5  375.91  173.56
  383.58  179.48  391.25  184.03   406.6   190.6  444.95  205.99  454.58  209.18
#Mann= 3 ,-1 , 0
       0     .06       0  222.48    .035       0  329.88      .1       0
Bank Sta=214.81,329.88
XS Rating Curve= 0 ,0
Exp/Cntr=0.5,0.3

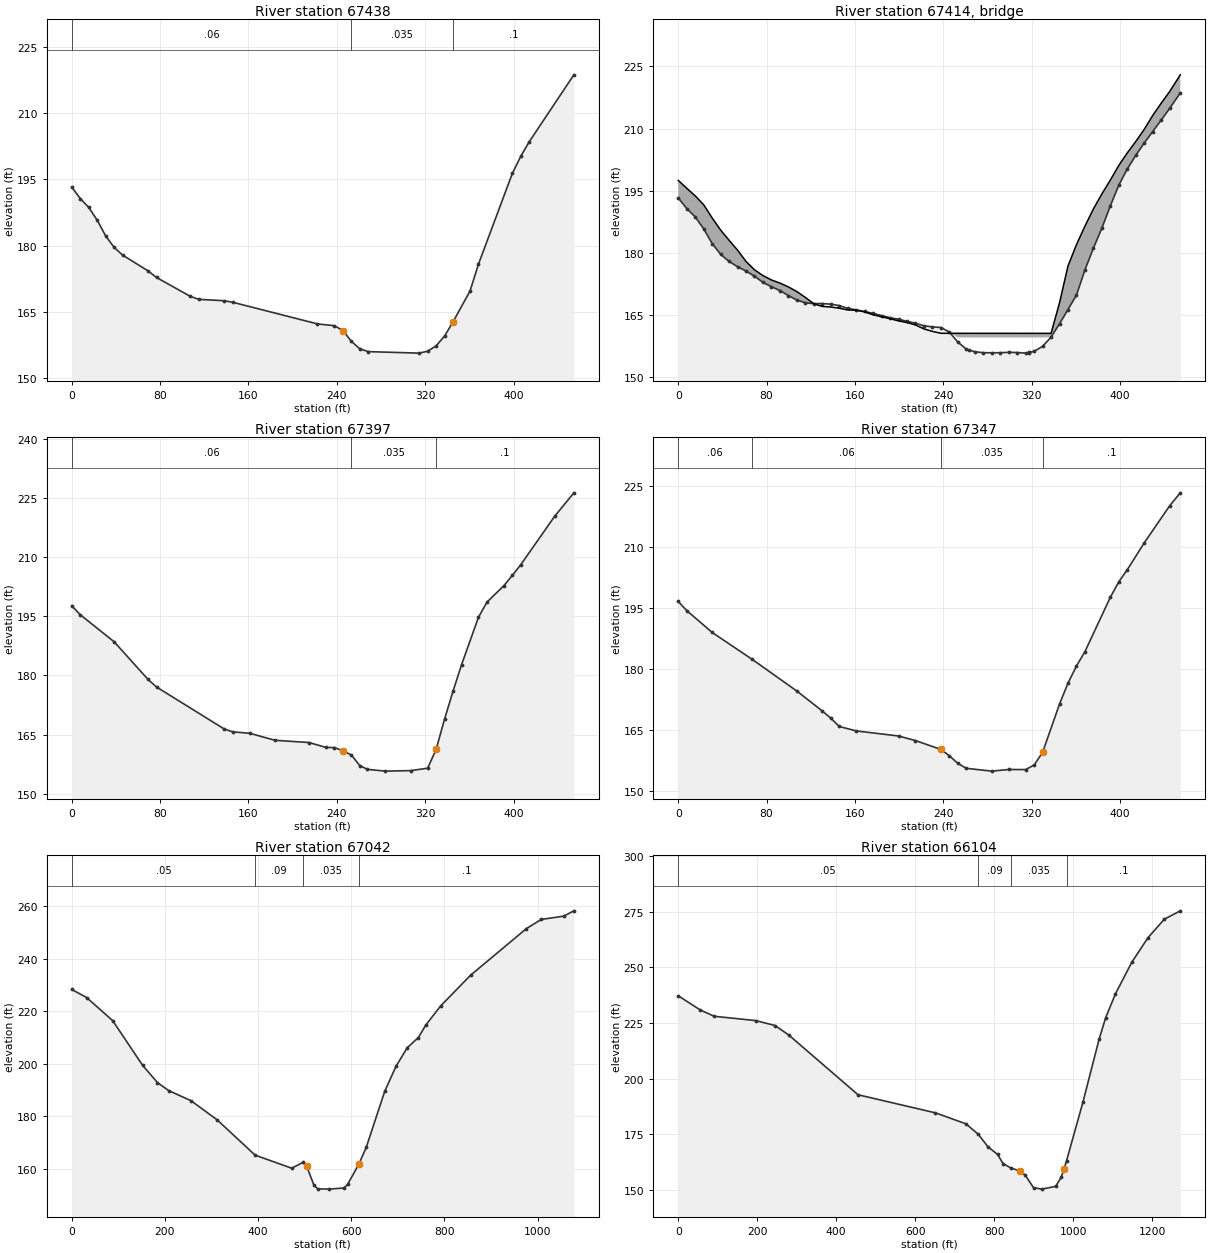
Type RM Length L Ch R = 1 ,67438   ,41.65,40.36,40
XS GIS Cut Line= 2
1638259.26648892748579.3908105491637844.48187555748393.385835528
#Sta/Elev= 30
       0  193.23    7.67  190.65   15.34  188.65   23.01  185.77   30.69  182.21
   38.36   179.6   46.03  177.87   69.04  174.31   76.72  172.81   107.4  168.54
  115.07  167.87  138.09  167.56  145.76  167.21  222.48  162.32  237.82  161.91
  245.49  160.82  253.16  158.38  260.83  156.68  268.51  156.06  314.54  155.72
  322.21  156.15  329.88  157.36  337.55  159.58  345.22   162.8  360.57  169.74
  368.24  175.84  398.92  196.33   406.6  200.23  414.27  203.51  454.58   218.6
#Mann= 3 ,-1 , 0
       0     .06       0  253.16    .035       0  345.22      .1       0
#XS Ineff= 2 , 0
       0     226   160.5     357       0   160.5
Permanent Ineff=
       F       F
Bank Sta=245.49,345.22
XS Rating Curve= 0 ,0
Exp/Cntr=0.5,0.3

Type RM Length L Ch R = 3 ,67414   ,,,
BEGIN DESCRIPTION:
Ped Bridge - No survey info.  Assumed elevation based on lidar bank elevation.  Assumed 1' deck thickness.
END DESCRIPTION:
Bridge Culvert--1,0,-1,-1, 0
Deck Dist Width WeirC Skew NumUp NumDn MinLoCord MaxHiCord MaxSubmerge Is_Ogee
20,8,2.6,0, 48, 48, , , 0.95, 0, 0,0,,
       0    7.67   15.34   23.01   30.69   38.36   46.03    53.7   61.37   69.04
   76.72   84.39   92.06   99.73   107.4  115.07  122.75  130.42  138.09  145.76
  153.43   161.1  168.78  176.45  184.12  191.79  199.46  207.13  214.81  222.48
  230.15  237.82  337.55  345.22  352.89  360.57  368.24  375.91  383.58  391.25
  398.92   406.6  414.27  421.94  429.61  437.28  444.95  454.58
  197.46  195.57  193.73  191.59   188.4  185.46  182.99  180.61  177.87  175.86
  174.45   173.4  172.65  171.72  170.59  169.19  167.65     167  166.86  166.57
  166.16  166.08  165.68  164.98   164.5  164.04  163.51  163.11  162.53  161.57
  160.97  160.51   160.5  167.88  176.77  181.93  186.42  190.57   194.2  197.55
  201.09  204.11  206.86  209.81  213.16  216.12  218.93  222.97
                                                                                
                                                                                
                                                                                
           159.5   159.5
                                                                
       0    7.67   15.34   23.01   30.69   38.36   46.03    53.7   61.37   69.04
   76.72   84.39   92.06   99.73   107.4  115.07  122.75  130.42  138.09  145.76
  153.43   161.1  168.78  176.45  184.12  191.79  199.46  207.13  214.81  222.48
  230.15  237.82  337.55  345.22  352.89  360.57  368.24  375.91  383.58  391.25
  398.92   406.6  414.27  421.94  429.61  437.28  444.95  454.58
  197.46  195.57  193.73  191.59   188.4  185.46  182.99  180.61  177.87  175.86
  174.45   173.4  172.65  171.72  170.59  169.19  167.65     167  166.86  166.57
  166.16  166.08  165.68  164.98   164.5  164.04  163.51  163.11  162.53  161.57
  160.97  160.51   160.5  167.88  176.77  181.93  186.42  190.57   194.2  197.55
  201.09  204.11  206.86  209.81  213.16  216.12  218.93  222.97
                                                                                
                                                                                
                                                                                
           159.5   159.5
                                                                
BR Coef=-1 , 0 , 0 ,, 0 ,,,0.8,0,,0,
WSPro=,,,, 1 ,,,, 0 ,,,, 0 ,,,,-1 ,-1 ,-1 , 0 , 0 , 0 , 0 , 0
BR U #Sta/Elev= 63
       0  193.23    7.67  190.65   15.34  188.65   23.01  185.77   30.69  182.21
   38.36   179.6   46.03  177.87    53.7  176.59   61.37  175.55   69.04  174.31
   76.72  172.81   84.39  171.76   92.06  170.84   99.73  169.63   107.4  168.54
  115.07  167.87  122.75  167.68  130.42   167.7  138.09  167.56  145.76  167.21
  153.43  166.54   161.1  166.16  168.78  165.78  176.45  165.32  184.12  164.79
  191.79  164.26  199.46  163.92  207.13  163.41  214.81  162.94  222.48  162.32
  230.15  162.06  237.82  161.91  245.49  160.82  253.16  158.38  260.83  156.68
  263.11  156.49  268.51  156.06  276.18  155.82  283.85   155.8  291.52  155.82
  299.19  155.91  306.86  155.87  314.54  155.72  317.21  155.87  317.43  155.88
  322.21  156.15  329.88  157.36  337.55  159.58  345.22   162.8  352.89  166.26
  360.57  169.74  368.24  175.84  375.91  181.09  383.58  185.92  391.25  191.32
  398.92  196.33   406.6  200.23  414.27  203.51  421.94  206.49  429.61  209.26
  437.28  212.03  444.95  214.85  454.58   218.6
BR U #Mann= 3
       0     .06  263.11    .033  317.21      .1
BR D #Sta/Elev= 62
       0  197.64    7.67  195.37   15.34  193.55   23.01  191.99   30.69  190.22
   38.36  188.52   46.03  186.38    53.7  183.99   61.37  181.57   69.04  178.98
   76.72  177.06   84.39  175.68   92.06  174.25   99.73   173.1   107.4  171.64
  115.07  170.58  122.75   169.3  130.42  167.82  138.09  166.41  145.76  165.69
  153.43  165.57   161.1  165.33  168.78  164.83  176.45  164.19  184.12  163.55
  191.79  163.54  199.46  163.53  207.13  163.16  214.81  162.99  222.48   162.4
  230.15  161.75  237.82  161.71  245.49  160.91  253.16  159.82  260.83  157.12
  267.75  156.19  268.51  156.09  276.18  155.83  283.85  155.74  291.52  155.78
  299.19  155.82  306.86  155.87  314.54  156.12  317.75  156.27  322.21  156.48
  329.88  161.24  337.55  168.93  345.22  176.02  352.89  182.68  360.57  188.57
  368.24  194.73  375.91  198.56  383.58  200.54  391.25  202.74  398.92  205.34
   406.6  208.08  414.27  211.09  421.94  214.39  429.61  217.45  437.28  220.34
  444.95  222.94  454.58  226.26
BR D #Mann= 3
       0     .06  267.75    .033  317.75      .1
BC Design=,, 0 ,, 0 ,,,,,,
BC Use User HTab Curves=0
BC User HTab FreeFlow(D)= 0

Type RM Length L Ch R = 1 ,67397   ,50.72,50,50
XS GIS Cut Line= 2
1638275.63363726748542.8926399951637860.84902391748356.887664974
#Sta/Elev= 30
       0  197.64    7.67  195.37   38.36  188.52   69.04  178.98   76.72  177.06
  138.09  166.41  145.76  165.69   161.1  165.33  184.12  163.55  214.81  162.99
  230.15  161.75  237.82  161.71  245.49  160.91  253.16  159.82  260.83  157.12
  267.75  156.19  283.85  155.74  306.86  155.87  322.21  156.48  329.88  161.24
  337.55  168.93  345.22  176.02  352.89  182.68  368.24  194.73  375.91  198.56
  391.25  202.74  398.92  205.34   406.6  208.08  437.28  220.34  454.58  226.26
#Mann= 3 ,-1 , 0
       0     .06       0  253.16    .035       0  329.88      .1       0
#XS Ineff= 2 , 0
       0     234   159.5     347       0   159.5
Permanent Ineff=
       F       F
Bank Sta=245.49,329.88
XS Rating Curve= 0 ,0
Exp/Cntr=0.5,0.3

Type RM Length L Ch R = 1 ,67347   ,299.77,305.29,309.67
XS GIS Cut Line= 2
1638296.09257273748497.2699268011637881.30795938 748311.26495178
#Sta/Elev= 30
       0  196.57    7.67  194.34   30.69  188.97   67.01  182.35   107.4  174.58
  130.42  169.69  138.09  167.94  145.76  165.89   161.1   164.8  199.46  163.55
  214.81  162.43  237.82  160.25  245.49   158.7  253.16  156.83  260.83  155.62
  283.85  154.93  299.19  155.33  314.54  155.31  322.21  156.42  329.88  159.53
  345.22  171.39  352.89  176.52  360.57  180.74  368.24  184.26  391.25  197.61
  398.92  201.41   406.6  204.37  421.94  210.96  444.95  220.05  454.58  223.23
#Mann= 4 ,-1 , 0
       0     .06       0   67.01     .06       0  237.82    .035       0
  329.88      .1       0
Bank Sta=237.82,329.88
XS Rating Curve= 0 ,0
Exp/Cntr=0.3,0.1

Type RM Length L Ch R = 1 ,67042   ,864.86,938.4,1001.38
XS GIS Cut Line= 2
1638648.15006149748372.6217594741637705.19716039747850.448916405
#Sta/Elev= 30
       0  228.28   32.01  225.19   88.02  216.36  152.03  199.39  184.04  192.79
  208.04  189.76  256.05  185.89  312.06  178.61  393.64  165.16   472.1  160.18
   496.1  162.37   504.1     161  520.11  153.63  528.11  152.34  552.11  152.21
  584.12  152.64  592.12     154  616.13  161.66  632.13  168.09  672.14   189.6
  696.14  199.01  720.15  206.06  744.15  209.97  760.16  214.75  792.16  222.05
  856.17   233.7   976.2   251.5 1008.21  254.97 1056.22  256.21 1077.88  258.24
#Mann= 4 ,-1 , 0
       0     .05       0  393.64     .09       0   496.1    .035       0
  616.13      .1       0
Bank Sta=504.1,616.13
XS Rating Curve= 0 ,0
Exp/Cntr=0.3,0.1

Type RM Length L Ch R = 1 ,66104   ,756.35,722.52,693.15
XS GIS Cut Line= 4
1638815.44815686 748458.805626781638835.72671387747657.802624792
1638825.87553801747476.2607539451638673.49825773 747231.95292753
#Sta/Elev= 30
       0  237.23   56.02  230.83   91.03  228.02  196.06  226.07  245.08  223.86
  280.09  219.54  455.15   192.7  651.21  184.56  728.23  179.63  759.42  174.94
  784.25  169.27  808.27  165.88  822.29  161.76  843.32  159.61  864.35  158.52
  878.37  156.51   899.4   150.9  920.44  150.24  955.49  151.49  969.51  155.62
  976.52  159.29  983.07  163.04 1024.32  189.26 1065.57  217.78 1082.07  227.35
 1106.82  238.13 1148.07  252.29 1189.32  263.41 1230.57   271.7    1271  275.46
#Mann= 4 ,-1 , 0
       0     .05       0  759.42     .09       0  843.32    .035       0
  983.07      .1       0
Bank Sta=864.35,976.52
XS Rating Curve= 0 ,0
Exp/Cntr=0.3,0.1

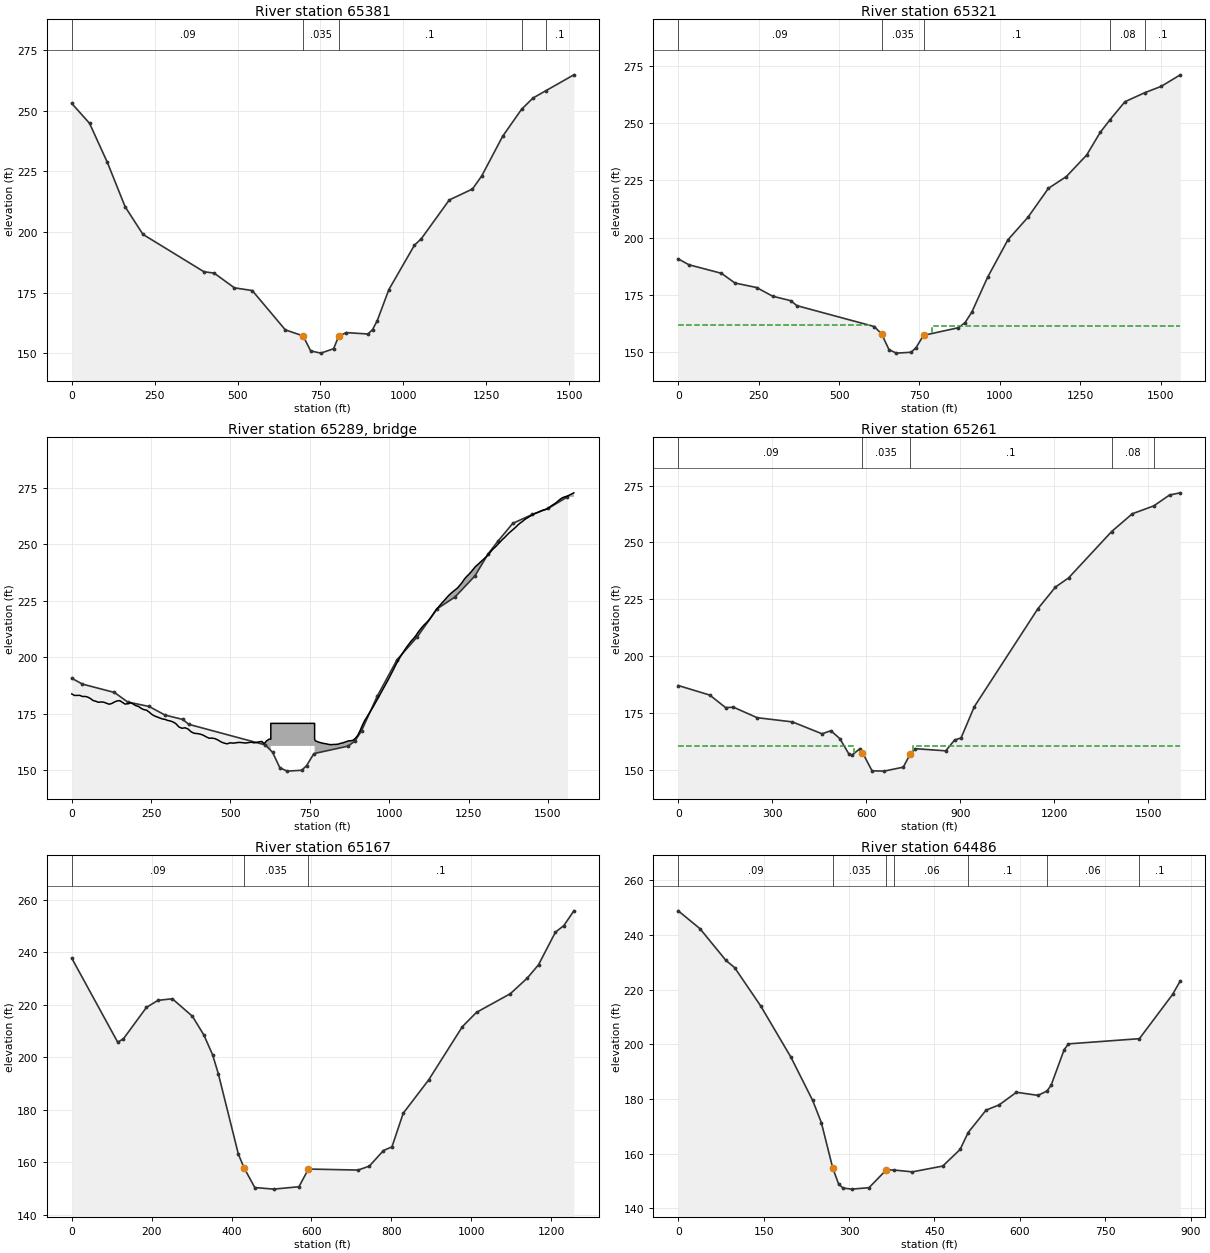
Type RM Length L Ch R = 1 ,65381   ,59.32,59.52,60.13
XS GIS Cut Line= 3
1639841.09694268748073.9992997051639479.63041577747264.807188272
1638852.23751497747236.531825691
#Sta/Elev= 30
       0  253.06   53.67  244.85  107.33  228.75     161  210.45  214.67  199.08
  398.67  183.67  429.33  183.11  490.67  177.02  544.33  175.92     644  159.71
  697.66  157.22  720.66  151.01  751.33  150.11  789.66  151.92     805  157.06
     828  158.57  893.26     158  907.28  159.84  921.29  163.49  956.33   176.3
  1033.4  194.59 1054.43  197.32 1138.51  213.26 1208.58  217.79 1236.61  223.21
 1299.67  239.55 1356.65  250.66 1390.77  255.26 1429.48  258.28 1514.28  264.86
#Mann= 5 ,-1 , 0
       0     .09       0  697.66    .035       0     805      .1       0
 1356.65     .08       0 1429.48      .1       0
Bank Sta=697.66,805
XS Rating Curve= 0 ,0
Exp/Cntr=0.5,0.3

Type RM Length L Ch R = 1 ,65321   ,60.14,60.11,87.28
BEGIN DESCRIPTION:
Modified under water portion by 0.5 feet as per "flow depth" in bridge inspection notes.
END DESCRIPTION:
XS GIS Cut Line= 6
1640101.79057638747815.7923361061639818.03171372747627.821202829
1639630.17469572747457.1295868011639548.83988678747274.126266748
1639525.52032672747223.8051107671638814.44587792 747202.93097809
#Sta/Elev= 30
       0  190.68   33.59   188.1  134.34  184.39  176.33  180.15   243.5  178.19
  293.88  174.37  349.83  172.44  368.74  170.27  609.51  161.15  632.49  157.91
  655.47  151.04  678.46  149.54  724.42  149.92  739.74  151.98  762.72  157.29
  870.93  160.63  891.94  162.86  912.95  167.44  961.97  182.65 1024.99  198.97
 1088.02  208.94 1151.05  221.48 1207.07  226.65  1270.1  236.02 1312.12   245.9
 1343.03  251.49 1389.15   259.3 1450.76  263.24  1501.2  265.96  1561.3  271.04
#Mann= 5 ,-1 , 0
       0     .09       0  632.49    .035       0  762.72      .1       0
 1343.03     .08       0 1450.76      .1       0
#XS Ineff= 2 , 0
       0     600  161.74     790       0   161.3
Permanent Ineff=
       F       F
Bank Sta=632.49,762.72
XS Rating Curve= 0 ,0
Exp/Cntr=0.5,0.3

Type RM Length L Ch R = 3 ,65289   ,,,
BEGIN DESCRIPTION:
Unnamed Bridge in Natural Reserve  - Approximate Reach
Top of road from LIDAR.
END DESCRIPTION:
Bridge Culvert--1,0,-1,-1, 0
Deck Dist Width WeirC Skew NumUp NumDn MinLoCord MaxHiCord MaxSubmerge Is_Ogee
25,14,2.6,0, 192, 193, , , 0.95, 0, 0,0,,
       0     8.4   16.79   25.19   33.59   41.98   50.38   58.78   67.17   75.57
   83.97   92.36  100.76  109.16  117.55  125.95  134.34  142.74  151.14  159.53
  167.93  176.33  184.72  193.12  201.52  209.91  218.31  226.71   235.1   243.5
   251.9  260.29  268.69  277.09  285.48  293.88  302.28  310.67  319.07  327.47
  338.08  347.54  356.99  366.45  375.91  385.37  394.83  404.29  413.74   423.2
  432.66  442.12  451.58  461.03  470.49  479.95  489.41  498.87  508.32  517.78
  527.24   536.7  546.16  555.61  565.07  574.53  583.29  590.95  598.61  606.27
  613.93  621.59  626.99     627     765  765.01  767.14  777.48  785.19  792.91
  800.62  808.34  816.05  823.77  831.48   839.2  846.91  851.72  858.73  865.73
  872.73  879.73  886.74  893.74  900.74  907.75  914.75  921.75  928.76  935.76
  942.76  949.76  956.77  963.77  970.77  977.78  984.78  991.78  998.79 1005.79
 1012.79 1019.79  1026.8  1033.8  1040.8 1047.81 1054.81 1061.81 1068.82 1075.82
 1082.82 1089.82 1096.83 1103.83 1110.83 1117.84 1124.84 1131.84 1138.85 1145.85
 1152.85 1159.86 1166.86 1173.86 1180.86 1187.87 1194.87 1201.87 1208.88 1215.88
 1222.88 1229.89 1236.89 1243.89  1250.9  1257.9  1264.9  1271.9 1278.91 1285.91
 1292.91 1299.92 1306.92 1313.92 1320.93 1327.93 1334.93 1341.93 1348.94 1355.94
 1362.94 1369.95 1376.95 1383.95 1390.96 1397.96 1404.96 1411.97 1418.97 1425.97
 1432.97 1439.98 1446.98 1453.98 1460.99 1467.99 1474.99    1482    1489    1496
 1503.01 1510.01 1517.01 1524.01 1531.02 1538.02 1545.02 1552.03 1559.03 1566.03
 1573.04 1581.65
  183.75  183.07  183.09  183.11   182.6  182.63  182.35   181.7  180.82   180.5
  180.04  180.17  180.09  179.66  179.18   179.5  180.18  180.63  180.77  180.01
  179.24  179.42  179.84  179.31  178.56  178.23  177.38  176.79  176.58  175.73
  174.71  174.01  173.53  173.09  172.65  172.46  171.99  171.76  171.32  170.62
  169.05  168.53  168.74  168.18  166.96  166.31  166.18  165.95  165.48  164.75
  164.11  164.17  163.91  163.28  162.47  161.95  161.63  162.09  161.93  162.11
  162.27  162.17  161.98  162.14  162.36  162.06  162.35  162.56  162.69  161.72
     163   163.7   163.7   170.7   170.7   163.7     163  162.38   162.1  161.82
  161.67   161.4  161.26  161.36  161.38  161.49  161.87  161.97  162.31   162.7
  162.98  162.99  163.27  164.12  165.38   167.3  169.62  171.71  173.35   174.9
   176.5   178.1  179.82  181.62  183.46  185.21  186.96  188.61  190.55  192.49
  194.34  196.36  198.28  199.93  201.49  203.05  204.47  205.76   207.1  208.16
  209.32  210.82  212.15  213.36  214.45   215.4  216.44  217.75  219.22  220.66
  221.83  222.99  224.18  225.21  226.38  227.43  228.36  229.15  229.94  230.78
  231.97  233.14  234.62  235.76  236.71   237.8  239.03  240.21  241.04  241.94
  242.82  243.75  244.68  245.74  246.95  248.06  248.94     250  251.09  252.06
  252.97  254.01  254.99  255.82  256.69  257.53  258.53   259.4  260.06   260.9
  261.57  262.14  262.78  263.29  263.81  264.17  264.63  265.05  265.34  265.61
  266.22  267.01  267.67  268.26  269.13  269.93   270.6  271.02   271.3  271.72
  272.23  272.84
                                                                                
                                                                                
                                                                                
                                                                                
                                                                                
                                                                                
                                                                                
                           160.7   160.7
                                                                                
                                                                                
                                                                                
                                                                                
                                                                                
                                                                                
                                                                                
                                                                                
                                                                                
                                                                                
                                                                                
                
     -40   -31.6  -23.21  -14.81   -6.41    1.98   10.38   18.78   27.17   35.57
   43.97   52.36   60.76   69.16   77.55   85.95   94.34  102.74  111.14  119.53
  127.93  136.33  144.72  153.12  161.52  169.91  178.31  186.71   195.1   203.5
   211.9  220.29  228.69  237.09  245.48  253.88  262.28  270.67  279.07  287.47
  298.08  307.54  316.99  326.45  335.91  345.37  354.83  364.29  373.74   383.2
  392.66  402.12  411.58  421.03  430.49  439.95  449.41  458.87  468.32  477.78
  487.24   496.7  506.16  515.61  525.07  534.53  543.29  550.95  558.61  566.27
  573.93  581.59  586.99     587     725  725.01  727.14  737.48  745.19  752.91
  760.62  768.34  776.05  783.77  791.48   799.2  806.91  811.72  818.73  825.73
  832.73  839.73  846.74  853.74  860.74  867.75  874.75  881.75  888.76  895.76
  902.76  909.76  916.77  923.77  930.77  937.78  944.78  951.78  958.79  965.79
  972.79  979.79   986.8   993.8  1000.8 1007.81 1014.81 1021.81 1028.82 1035.82
 1042.82 1049.82 1056.83 1063.83 1070.83 1077.84 1084.84 1091.84 1098.85 1105.85
 1112.85 1119.86 1126.86 1133.86 1140.86 1147.87 1154.87 1161.87 1168.88 1175.88
 1182.88 1189.89 1196.89 1203.89  1210.9  1217.9  1224.9  1231.9 1238.91 1245.91
 1252.91 1259.92 1266.92 1273.92 1280.93 1287.93 1294.93 1301.93 1308.94 1315.94
 1322.94 1329.95 1336.95 1343.95 1350.96 1357.96 1364.96 1371.97 1378.97 1385.97
 1392.97 1399.98 1406.98 1413.98 1420.99 1427.99 1434.99    1442    1449    1456
 1463.01 1470.01 1477.01 1484.01 1491.02 1498.02 1505.02 1512.03 1519.03 1526.03
 1533.04 1541.65 1602.01
  183.75  183.07  183.09  183.11   182.6  182.63  182.35   181.7  180.82   180.5
  180.04  180.17  180.09  179.66  179.18   179.5  180.18  180.63  180.77  180.01
  179.24  179.42  179.84  179.31  178.56  178.23  177.38  176.79  176.58  175.73
  174.71  174.01  173.53  173.09  172.65  172.46  171.99  171.76  171.32  170.62
  169.05  168.53  168.74  168.18  166.96  166.31  166.18  165.95  165.48  164.75
  164.11  164.17  163.91  163.28  162.47  161.95  161.63  162.09  161.93  162.11
  162.27  162.17  161.98  162.14  162.36  162.06  162.35  162.56  162.69  161.72
     163   163.7   163.7   170.7   170.7   163.7     163  162.38   162.1  161.82
  161.67   161.4  161.26  161.36  161.38  161.49  161.87  161.97  162.31   162.7
  162.98  162.99  163.27  164.12  165.38   167.3  169.62  171.71  173.35   174.9
   176.5   178.1  179.82  181.62  183.46  185.21  186.96  188.61  190.55  192.49
  194.34  196.36  198.28  199.93  201.49  203.05  204.47  205.76   207.1  208.16
  209.32  210.82  212.15  213.36  214.45   215.4  216.44  217.75  219.22  220.66
  221.83  222.99  224.18  225.21  226.38  227.43  228.36  229.15  229.94  230.78
  231.97  233.14  234.62  235.76  236.71   237.8  239.03  240.21  241.04  241.94
  242.82  243.75  244.68  245.74  246.95  248.06  248.94     250  251.09  252.06
  252.97  254.01  254.99  255.82  256.69  257.53  258.53   259.4  260.06   260.9
  261.57  262.14  262.78  263.29  263.81  264.17  264.63  265.05  265.34  265.61
  266.22  267.01  267.67  268.26  269.13  269.93   270.6  271.02   271.3  271.72
  272.23  272.84  272.84
                                                                                
                                                                                
                                                                                
                                                                                
                                                                                
                                                                                
                                                                                
                           160.7   160.7
                                                                                
                                                                                
                                                                                
                                                                                
                                                                                
                                                                                
                                                                                
                                                                                
                                                                                
                                                                                
                                                                                
                        
BR Coef=-1 , 0 , 0 ,, 0 ,,,0.8,0,,0,
WSPro=,,,, 1 ,,,, 0 ,,,, 0 ,,,,-1 ,-1 ,-1 , 0 , 0 , 0 , 0 , 0
BR U #Sta/Elev= 30
       0  190.68   33.59   188.1  134.34  184.39  176.33  180.15   243.5  178.19
  293.88  174.37  349.83  172.44  368.74  170.27  609.51  161.15  632.49  157.91
  655.47  151.04  678.46  149.54  724.42  149.92  739.74  151.98  762.72  157.29
  870.93  160.63  891.94  162.86  912.95  167.44  961.97  182.65 1024.99  198.97
 1088.02  208.94 1151.05  221.48 1207.07  226.65  1270.1  236.02 1312.12   245.9
 1343.03  251.49 1389.15   259.3 1450.76  263.24  1501.2  265.96  1561.3  271.04
BR U #Mann= 5
       0     .09  632.49    .033  762.72      .1 1343.03     .08 1450.76      .1
BR D #Sta/Elev= 30
       0  187.24  100.76  183.03  151.14  177.54  176.33  177.72   251.9  173.11
  364.16  171.28  458.74  166.06  487.12  167.39  515.49  163.95  543.86  157.36
  553.32  156.56  580.05  159.55  587.71  157.84  618.35  149.82  656.66  149.67
  717.94  151.41  740.92  157.33  756.24  159.52  853.53  158.58  881.54  163.29
  902.55  164.26  944.57  177.92 1147.65  220.96 1203.68  230.45  1245.7  234.49
 1382.85   254.8 1448.78   262.6 1517.26  266.05 1567.84  270.85 1602.01  271.79
BR D #Mann= 5
       0     .09  587.71    .033  740.92      .1 1382.85     .08 1517.26      .1
BC Design=,, 0 ,, 0 ,,,,,,
BC Use User HTab Curves=0
BC User HTab FreeFlow(D)= 0

Type RM Length L Ch R = 1 ,65261   ,96.8,94.07,27.91
BEGIN DESCRIPTION:
Modified under water portion by 0.5 feet as per "flow depth" in bridge inspection notes.
END DESCRIPTION:
XS GIS Cut Line= 6
  1640134.925822747765.7717853641639854.98829399747580.332028881
1639679.87296996747421.2178367531639603.47693069 747249.32674855
1639564.36136343747164.9194717411638816.20646524747142.956814244
#Sta/Elev= 30
       0  187.24  100.76  183.03  151.14  177.54  176.33  177.72   251.9  173.11
  364.16  171.28  458.74  166.06  487.12  167.39  515.49  163.95  543.86  157.36
  553.32  156.56  580.05  159.55  587.71  157.84  618.35  149.82  656.66  149.67
  717.94  151.41  740.92  157.33  756.24  159.52  853.53  158.58  881.54  163.29
  902.55  164.26  944.57  177.92 1147.65  220.96 1203.68  230.45  1245.7  234.49
 1382.85   254.8 1448.78   262.6 1517.26  266.05 1567.84  270.85 1602.01  271.79
#Mann= 5 ,-1 , 0
       0     .09       0  587.71    .035       0  740.92      .1       0
 1382.85     .08       0 1517.26      .1       0
#XS Ineff= 2 , 0
       0     562   160.7     750       0   160.7
Permanent Ineff=
       F       F
Bank Sta=587.71,740.92
XS Rating Curve= 0 ,0
Exp/Cntr=0.5,0.3

Type RM Length L Ch R = 1 ,65167   ,747.06,681.77,475.17
XS GIS Cut Line= 4
 1640183.2895516747448.3372979911639752.78409803747346.958671674
1639658.30989212747166.2254081961639052.55138642747089.915070981
#Sta/Elev= 30
       0  237.82  115.06   205.8  129.45  207.14  186.98  219.09  215.74  221.75
   251.7  222.36  302.04   215.7  330.81  208.51  352.38  201.09  366.76  193.87
  417.11  163.12  431.49  157.89  458.08  150.46  505.47  149.85  568.66  150.76
  592.36   157.5  716.77  157.11  744.99  158.64  780.27  164.56  801.43  165.95
  829.66  178.76  893.15  191.41  977.82  211.76 1013.09  217.19 1097.76  224.29
 1140.09  230.22 1168.31  235.31 1210.64  247.73 1231.81  250.25 1256.76  255.86
#Mann= 3 ,-1 , 0
       0     .09       0  431.49    .035       0  592.36      .1       0
Bank Sta=431.49,592.36
XS Rating Curve= 0 ,0
Exp/Cntr=0.3,0.1

Type RM Length L Ch R = 1 ,64486   ,411.21,397.88,371.27
XS GIS Cut Line= 2
1639870.97837757746524.528308988 1639060.4588936746872.458624065
#Sta/Elev= 30
       0  248.77   38.09  242.27   83.79  230.66   99.03  228.03  144.74  214.05
  198.06  195.25  236.15  179.49  251.38  171.41  271.52  154.72  281.85  148.89
  289.47  147.46  304.71  147.07  335.18   147.6  365.65  154.13   379.9  154.03
  411.36  153.38  464.68   155.5  495.15  161.57  509.38  167.76  540.86  175.95
  563.71  177.85  594.18  182.46  632.27  181.33  647.77  182.93  655.12  185.06
  677.97  198.03  685.59  200.15  810.15  202.05  868.42   218.2  882.04  223.21
#Mann= 7 ,-1 , 0
       0     .09       0  271.52    .035       0  365.65      .1       0
   379.9     .06       0  509.38      .1       0  647.77     .06       0
  810.15      .1       0
Bank Sta=271.52,365.65
XS Rating Curve= 0 ,0
Exp/Cntr=0.3,0.1

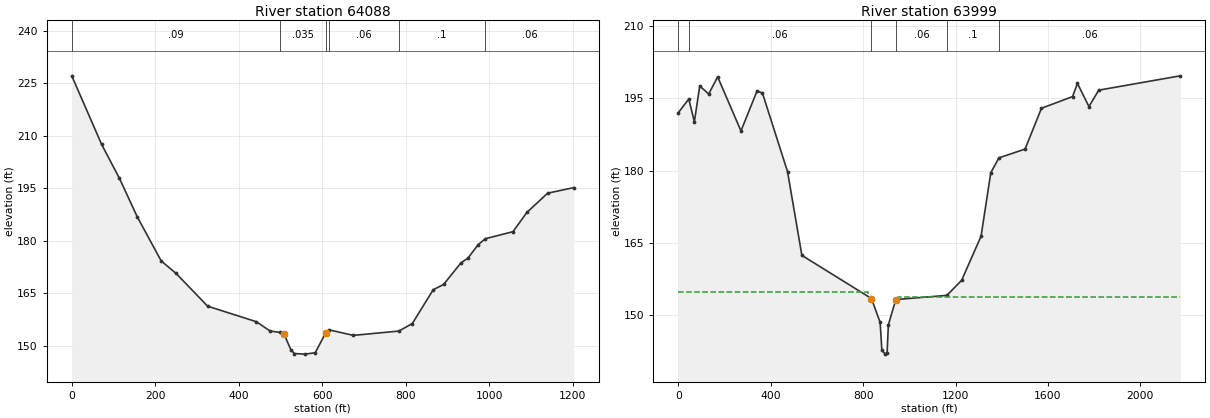
Type RM Length L Ch R = 1 ,64088   ,74.62,88.5,82.89
XS GIS Cut Line= 3
1639961.06162938746215.7965922651639642.09201662746150.700752929
 1638903.2923094746624.290308878
#Sta/Elev= 30
       0  227.17   71.44   207.6  114.31  197.86  157.17  186.82  214.33  174.28
  250.05   170.7  325.54  161.35  441.95  156.93  475.21  154.26  500.15  153.83
  508.47  153.42   525.1  148.89  533.41  147.82  558.36  147.65   583.3  148.04
  608.25  153.67  616.47  154.59  674.76  153.01  783.82  154.24  816.11   156.4
     866  166.04  890.95  167.55  932.52  173.72  949.15  175.06  974.09  178.97
  991.24  180.63 1057.24  182.64  1090.5  188.13 1140.39  193.64 1203.11  195.23
#Mann= 6 ,-1 , 0
       0     .09       0  500.15    .035       0  608.25      .1       0
  616.47     .06       0  783.82      .1       0  991.24     .06       0
Bank Sta=508.47,608.25
XS Rating Curve= 0 ,0
Exp/Cntr=0.5,0.3

Type RM Length L Ch R = 1 ,63999   ,57.57,57.03,57.31
BEGIN DESCRIPTION:
Modified under water portion by 5 feet
END DESCRIPTION:
XS GIS Cut Line= 6
1640220.90831181745813.8605689411639486.62807891 746163.74642238
1639383.80834064746204.8743176911639167.34203364746363.589129686
1638922.72088936746527.0429831451638245.02137795 746632.80933024
#Sta/Elev= 30
       0  191.97   45.63  194.82   69.79  190.11   93.05  197.53  131.82  195.87
  170.59  199.42  271.39  188.21  341.18   196.5  364.44  196.05     473  179.76
  535.03  162.41     836  153.47  873.69  148.51  881.23  142.72  896.31  141.94
  903.85  142.23  909.25  148.01  941.55  153.25 1162.37  154.12 1226.22  157.23
 1310.41  166.38  1352.5  179.54 1387.67  182.62 1500.92  184.45 1571.76   192.9
 1706.37  195.33 1727.63  198.06 1777.22  193.26 1819.73  196.66 2172.65  199.63
#Mann= 6 ,-1 , 0
       0     .09       0   45.63     .06       0     836    .035       0
  941.55     .06       0 1162.37      .1       0 1387.67     .06       0
#XS Ineff= 2 , 0
       0     820   154.9     950       0   153.8
Permanent Ineff=
       F       F
Bank Sta=836,941.55
XS Rating Curve= 0 ,0
Exp/Cntr=0.5,0.3