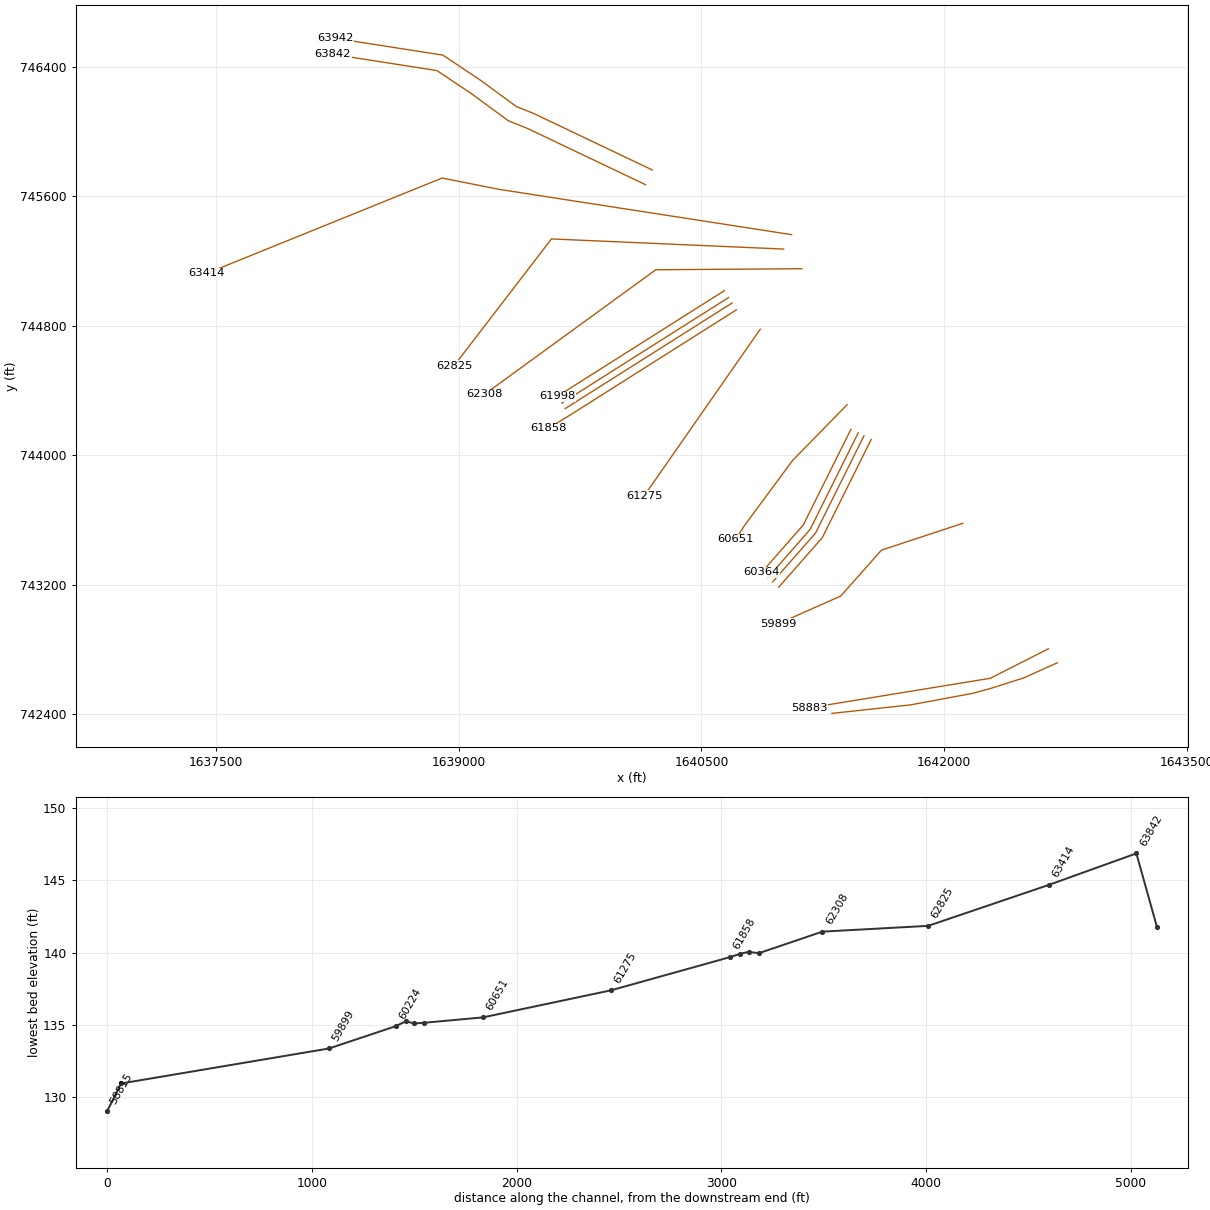
HEC-RAS study bigelkcreek.prj: Big Elk Creek

--- bigelkcreek.g23 (geometry) --- (continued)

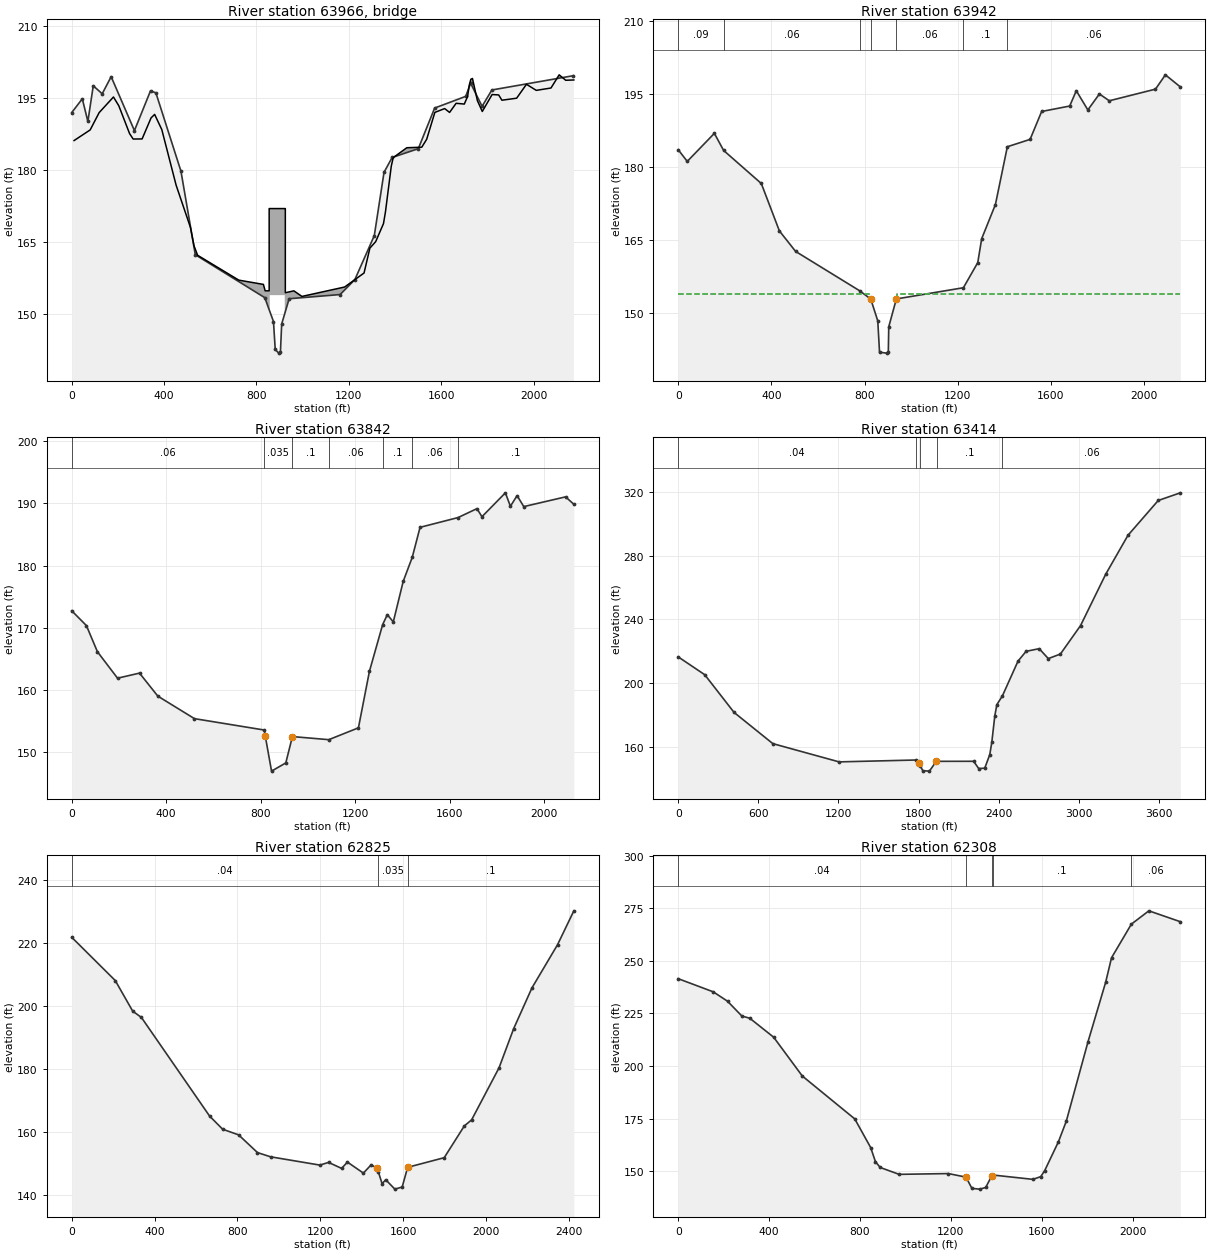
Type RM Length L Ch R = 3 ,63966   ,,,
BEGIN DESCRIPTION:
Tawes Drive - CE050407FS-9   Covered Bridge.  Approximate Reach.  Covered Bridge - 16 feet in height.  Stone abutments - vertical faced.
Top of road from LIDAR.
END DESCRIPTION:
Bridge Culvert--1,0,-1,-1, 0
Deck Dist Width WeirC Skew NumUp NumDn MinLoCord MaxHiCord MaxSubmerge Is_Ogee
25,16,2.6,0, 60, 60, , , 0.95, 0, 0,0,,
      10   79.79  118.56  180.59  203.85  250.38  265.88  304.65  343.43  358.93
  389.95  451.98  514.01  529.52  545.03  723.37  830.05  837.59 854.999     855
 857.499   857.5   922.5  922.51     925 925.001  962.04   996.9 1182.02 1265.94
 1291.19 1316.45 1350.12 1358.54  1383.8 1392.22 1451.15 1515.98 1537.23 1572.66
 1615.17 1636.42 1664.76 1700.18 1714.35 1721.44 1728.52 1735.61 1756.86 1778.11
 1820.62 1848.96 1863.13 1926.89  1969.4 2011.91 2075.67  2111.1 2139.44 2174.67
  186.14  188.36  191.95   195.2  193.36  187.59  186.46  186.48  190.85  191.58
  188.42  176.86  168.08  164.25  162.29  157.12  156.23   154.9   154.9     172
     172     172     172     172     172   154.5  154.89  153.73  155.69   158.6
  163.77  165.13  168.87  171.26  180.79  182.59  184.65  184.76  186.41     192
  192.79  191.99  193.89  193.73   195.3  197.62  198.89  199.05  194.45  192.19
  195.71  195.63  194.53  194.95  197.84  196.58  197.07  199.81  198.68  198.74
                                                                                
                                                                                
             154     154
                                                                                
                                                                                
                                                                                
       0   69.79  108.56  170.59  193.85  240.38  255.88  294.65  333.43  348.93
  379.95  441.98  504.01  519.52  535.03  713.37  820.05  827.59 844.999     845
 847.499   847.5   912.5  912.51     915 915.001  952.04   986.9 1172.02 1255.94
 1281.19 1306.45 1340.12 1348.54  1373.8 1382.22 1441.15 1505.98 1527.23 1562.66
 1605.17 1626.42 1654.76 1690.18 1704.35 1711.44 1718.52 1725.61 1746.86 1768.11
 1810.62 1838.96 1853.13 1916.89  1959.4 2001.91 2065.67  2101.1 2129.44 2164.67
  186.14  188.36  191.95   195.2  193.36  187.59  186.46  186.48  190.85  191.58
  188.42  176.86  168.08  164.25  162.29  157.12  156.23   154.9   154.9     172
     172     172     172     172     172   154.5  154.89  153.73  155.69   158.6
  163.77  165.13  168.87  171.26  180.79  182.59  184.65  184.76  186.41     192
  192.79  191.99  193.89  193.73   195.3  197.62  198.89  199.05  194.45  192.19
  195.71  195.63  194.53  194.95  197.84  196.58  197.07  199.81  198.68  198.74
                                                                                
                                                                                
             154     154
                                                                                
                                                                                
                                                                                
BR Coef=-1 , 0 , 0 ,, 0 ,,,0.8,0,,0,
WSPro=,,,, 1 ,,,, 0 ,,,, 0 ,,,,-1 ,-1 ,-1 , 0 , 0 , 0 , 0 , 0
BR U #Sta/Elev= 30
       0  191.97   45.63  194.82   69.79  190.11   93.05  197.53  131.82  195.87
  170.59  199.42  271.39  188.21  341.18   196.5  364.44  196.05     473  179.76
  535.03  162.41     836  153.47  873.69  148.51  881.23  142.72  896.31  141.94
  903.85  142.23  909.25  148.01  941.55  153.25 1162.37  154.12 1226.22  157.23
 1310.41  166.38  1352.5  179.54 1387.67  182.62 1500.92  184.45 1571.76   192.9
 1706.37  195.33 1727.63  198.06 1777.22  193.26 1819.73  196.66 2172.65  199.63
BR U #Mann= 6
       0     .09   45.63     .06     836    .033  941.55     .06 1162.37      .1
 1387.67     .06
BR D #Sta/Elev= 30
       0  183.57   38.77  181.18  155.08  186.94  194.89  183.43  356.69  176.64
  434.23  166.91  504.01  162.69  779.54  154.59  826.63   152.9  856.79  148.42
  864.33  141.99  894.48   141.8  902.02  141.95  903.93  147.21  936.57  152.93
  1224.5  155.23 1286.15   160.4 1302.99  165.31 1361.92  172.32 1413.13  184.19
 1510.82   185.7 1560.41  191.43 1680.85  192.55 1709.19  195.69 1758.79  191.75
 1808.38  195.03 1850.89  193.63 2049.26  196.02 2091.77  198.96 2155.81  196.48
BR D #Mann= 7
       0     .09  194.89     .06  779.54     .06  826.63    .033  936.57     .06
  1224.5      .1 1413.13     .06
BC Design=,, 0 ,, 0 ,,,,,,
BC Use User HTab Curves=0
BC User HTab FreeFlow(D)= 0

Type RM Length L Ch R = 1 ,63942   ,101,100.05,100.85
BEGIN DESCRIPTION:
Modified under water portion by 2 feet as per "flow depth" in bridge inspection notes.
END DESCRIPTION:
XS GIS Cut Line= 6
1640196.38903993745762.4037394231639463.76027802746111.502663925
1639355.77887928746154.6952234211639134.75162026746316.812042788
1638901.50782681746472.6636431961638236.23197138746576.491070926
#Sta/Elev= 30
       0  183.57   38.77  181.18  155.08  186.94  194.89  183.43  356.69  176.64
  434.23  166.91  504.01  162.69  779.54  154.59  826.63   152.9  856.79  148.42
  864.33  141.99  894.48   141.8  902.02  141.95  903.93  147.21  936.57  152.93
  1224.5  155.23 1286.15   160.4 1302.99  165.31 1361.92  172.32 1413.13  184.19
 1510.82   185.7 1560.41  191.43 1680.85  192.55 1709.19  195.69 1758.79  191.75
 1808.38  195.03 1850.89  193.63 2049.26  196.02 2091.77  198.96 2155.81  196.48
#Mann= 7 ,-1 , 0
       0     .09       0  194.89     .06       0  779.54     .06       0
  826.63    .035       0  936.57     .06       0  1224.5      .1       0
 1413.13     .06       0
#XS Ineff= 2 , 0
       0     822     154     940       0     154
Permanent Ineff=
       F       F
Bank Sta=826.63,936.57
XS Rating Curve= 0 ,0
Exp/Cntr=0.5,0.3

Type RM Length L Ch R = 1 ,63842   ,406.73,427.85,503.48
XS GIS Cut Line= 6
1640153.37277338745672.1285999271639423.64132918746019.846947327
1639306.60438564746066.6617247311639077.57545646746234.746978059
1638864.29192765746377.2612924131638220.81195977746477.687107235
#Sta/Elev= 30
       0   172.7   62.03  170.32  108.56  166.11  193.85  161.84   286.9  162.66
  364.44  158.95  519.52  155.32  815.88  153.48  819.74  152.46  846.04  146.86
  906.35  148.18  934.39  152.43 1088.44  151.93    1214  153.84 1260.58  162.95
 1316.59  170.48 1336.35  172.08 1361.61  170.91  1403.7  177.46 1441.82  181.31
    1475  186.16 1635.74  187.73 1715.88  189.17 1737.14  187.87 1836.32  191.72
 1857.58  189.55 1885.92  191.27 1914.25   189.5 2091.37  191.07 2126.27  189.87
#Mann= 7 ,-1 , 0
       0     .06       0  815.88    .035       0  934.39      .1       0
 1088.44     .06       0 1316.59      .1       0 1441.82     .06       0
 1635.74      .1       0
Bank Sta=819.74,934.39
XS Rating Curve= 0 ,0
Exp/Cntr=0.3,0.1

Type RM Length L Ch R = 1 ,63414   ,388.48,589.02,696.61
XS GIS Cut Line= 4
1641057.50339927745362.8458094151639247.96925738745643.083397776
1638896.61139624745712.7993589341637441.34873216745123.305991367
#Sta/Elev= 30
       0  216.43  198.34  205.25  417.92  181.57  708.34  161.95 1204.19  150.49
 1782.73  151.67 1806.28  149.93 1813.37  147.94 1831.11  144.94 1881.07  144.68
 1931.02  150.73 1938.16  150.83 2211.98  150.86 2249.74  146.31 2295.05  146.54
 2332.82  155.08 2347.92  162.81 2370.58   179.5 2385.68  186.42 2427.47  191.98
 2544.28  213.79  2604.7  219.93 2702.89   221.6 2770.86  215.36 2861.49  218.22
 3012.54  236.12 3201.35  268.44 3367.51  292.81 3594.08  314.68 3759.44  319.49
#Mann= 5 ,-1 , 0
       0     .04       0 1782.73      .1       0 1813.37    .035       0
 1938.16      .1       0 2427.47     .06       0
Bank Sta=1806.28,1931.02
XS Rating Curve= 0 ,0
Exp/Cntr=0.3,0.1

Type RM Length L Ch R = 1 ,62825   ,431.31,516.74,475.34
XS GIS Cut Line= 3
1641008.09065574745273.7485329361639572.61807138745336.432925284
1638970.84790501744552.878021166
#Sta/Elev= 30
       0  221.77   210.2  208.04  294.28  198.34  336.32  196.34  665.63  165.04
  728.69  160.86  805.77  159.07  896.85  153.45  959.91  152.11 1198.14  149.48
 1240.18  150.33 1303.24  148.43 1331.27  150.43 1408.34  146.94 1445.67  149.55
 1472.15  148.59 1480.97  147.29 1498.63  143.57 1516.28  144.83 1560.41  141.85
 1595.71  142.52 1622.19  148.77 1798.72  151.83  1895.8   161.9 1931.11  163.84
  2063.5  180.35 2134.11  192.77 2222.37  205.71 2345.94  219.41 2424.81  230.18
#Mann= 3 ,-1 , 0
       0     .04       0 1480.97    .035       0 1622.19      .1       0
Bank Sta=1472.15,1622.19
XS Rating Curve= 0 ,0
Exp/Cntr=0.3,0.1

Type RM Length L Ch R = 1 ,62308   ,321.58,310.2,301
XS GIS Cut Line= 3
1641120.75702639745152.2672787461640217.59131306745145.861848146
1639160.69526556744377.210177243
#Sta/Elev= 30
       0  241.53     154  235.29  217.01  230.82  280.01  223.78  315.01  222.72
  420.01  213.71  546.01  195.26  777.02  174.85  847.02  161.23  868.02  154.53
  889.02  151.74  972.43  148.48 1188.82  148.85 1266.72  147.16 1292.69   141.8
 1327.31  141.45 1353.28  142.23 1379.24  147.58  1385.7  148.15 1561.01   146.1
 1595.63  147.39 1612.94  150.22 1673.53  163.97 1708.15  173.75 1803.36  211.39
 1881.26  239.77 1907.23  251.47 1994.56  267.47 2071.68  273.81 2210.04  268.64
#Mann= 5 ,-1 , 0
       0     .04       0 1266.72    .035       0 1379.24     .06       0
  1385.7      .1       0 1994.56     .06       0
Bank Sta=1266.72,1379.24
XS Rating Curve= 0 ,0
Exp/Cntr=0.3,0.1

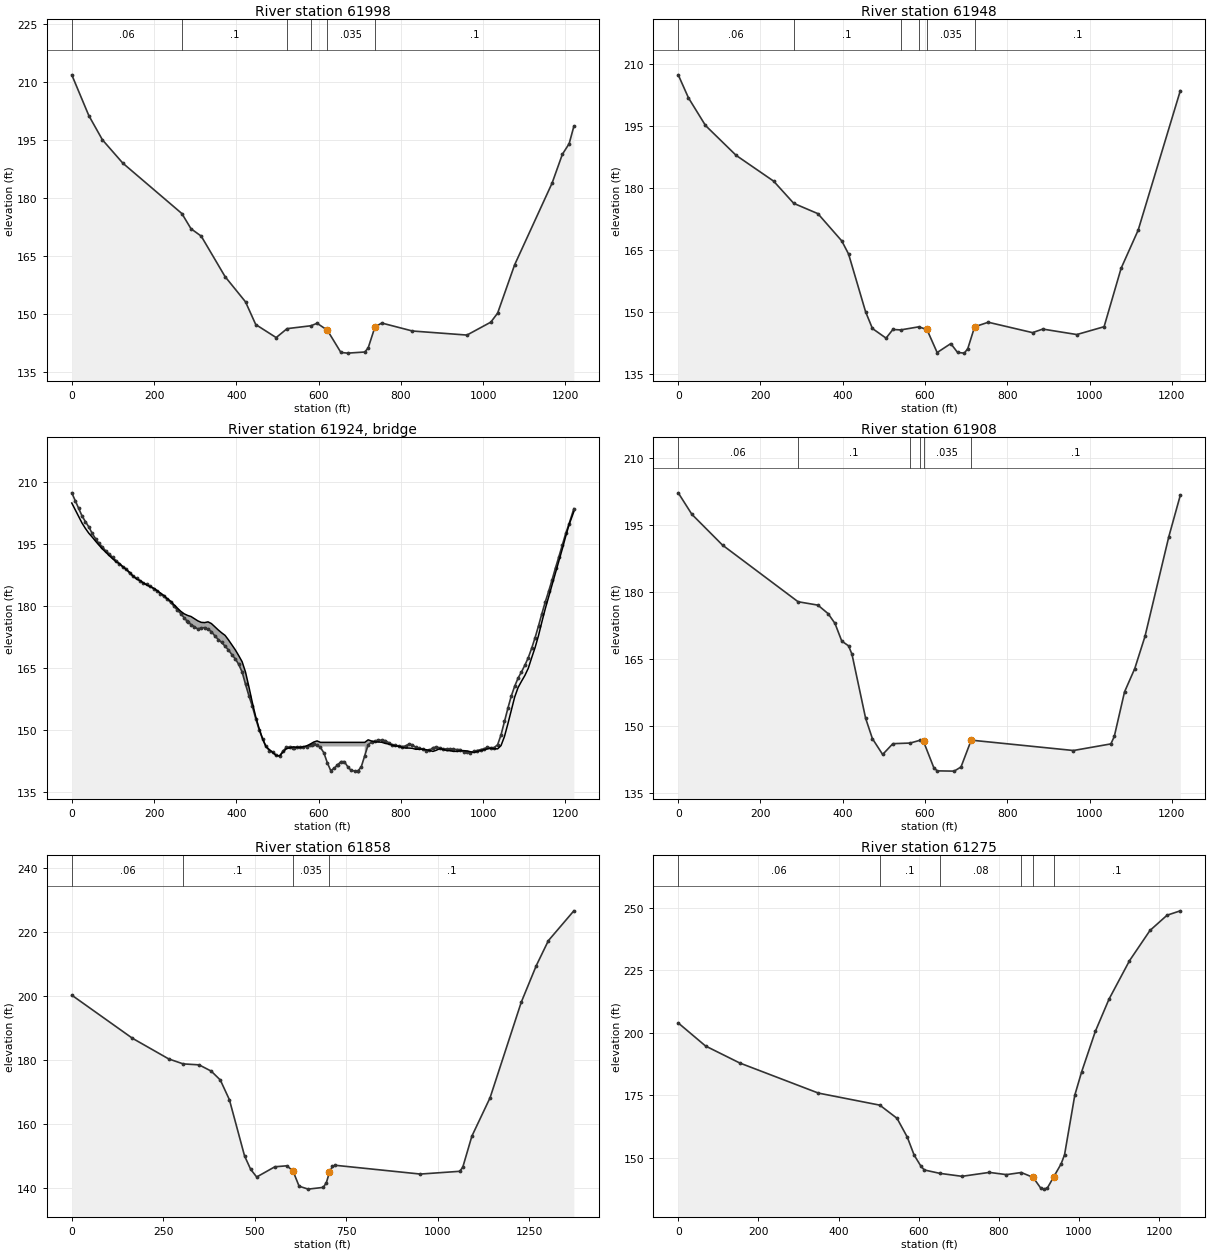
Type RM Length L Ch R = 1 ,61998   ,50.59,50.21,50.06
XS GIS Cut Line= 2
1640641.13998452745016.4996895641639609.51421143744363.782514557
#Sta/Elev= 30
       0  211.92   41.42  201.39   74.55  195.11  124.25  189.07  267.72  176.05
  289.92  172.12  314.77  170.21  372.76  159.74  422.46  153.22  447.31  147.35
  497.01  143.98  523.47  146.29  581.82  147.04  596.41  147.68  621.26  145.91
  654.39  140.13  670.96  139.96  712.38  140.25  720.66  141.29  737.23  146.75
  753.79  147.74  828.34  145.68  960.88  144.63 1018.86  147.97 1035.43   150.3
 1076.85  162.81 1167.97  183.95 1192.82  191.36 1209.38  194.13 1220.77  198.59
#Mann= 6 ,-1 , 0
       0     .06       0  267.72      .1       0  523.47     .06       0
  581.82     .07       0  621.26    .035       0  737.23      .1       0
Bank Sta=621.26,737.23
XS Rating Curve= 0 ,0
Exp/Cntr=0.5,0.3

Type RM Length L Ch R = 1 ,61948   ,40.23,40.17,40.05
XS GIS Cut Line= 2
1640667.87370729744974.2467835551639636.24793421744321.529608548
#Sta/Elev= 30
       0  207.28   24.85  201.72   66.27  195.04  140.82  187.82  231.94   181.6
   280.9  176.23  339.62  173.74  397.61  167.16  414.17  163.99  455.59  150.03
  472.16     146  505.29  143.67  521.86  145.76   540.8  145.66  584.75   146.4
  604.69  145.76  629.54  140.19  662.68  142.35  679.24  140.21  695.72  140.05
  704.09  141.16  720.66  146.41  753.79  147.51  861.48     145  886.33  145.86
  969.16  144.54 1035.43  146.43 1076.85  160.55 1118.27  169.75 1220.77  203.45
#Mann= 6 ,-1 , 0
       0     .06       0   280.9      .1       0   540.8     .06       0
  584.75     .07       0  604.69    .035       0  720.66      .1       0
#XS Ineff= 2 , 0
       0     579   143.9     737       0  144.58
Permanent Ineff=
       F       F
Bank Sta=604.69,720.66
XS Rating Curve= 0 ,0
Exp/Cntr=0.5,0.3

Type RM Length L Ch R = 3 ,61924   ,,,
BEGIN DESCRIPTION:
Ped Bridge - No survey info.  Assumed elevation based on lidar bank elevation.  Assumed 1' deck thickness.
END DESCRIPTION:
Bridge Culvert--1,0,-1,-1, 0
Deck Dist Width WeirC Skew NumUp NumDn MinLoCord MaxHiCord MaxSubmerge Is_Ogee
20,8,2.6,0, 136, 136, , , 0.95, 0, 0,0,,
       0    8.28   16.57   24.85   33.13   41.42    49.7   57.98   66.27   74.55
   82.83   91.12    99.4  107.68  115.97  124.25  132.54  140.82   149.1  157.39
  165.67  173.95  182.24  190.52   198.8  207.09  215.37  223.65  231.94  240.22
   248.5  256.79  265.07  273.35  281.64  289.92   298.2  306.49  314.77  323.05
  331.34  339.62   347.9  356.19  364.47  372.76  381.04  389.32  397.61  405.89
  414.17  422.46  430.74  439.02  447.31  455.59  463.87  472.16  480.44  488.72
  497.01  505.29  513.57  521.86  530.14  538.42  546.71  554.99  563.27  571.56
  579.84  588.12  596.41  604.69  712.38  720.66  728.94  737.23  745.51  753.79
  762.08  770.36  778.64  786.93  795.21  803.49  811.78  820.06  828.34  836.63
  844.91   853.2  861.48  869.76  878.05  886.33  894.61   902.9  911.18  919.46
  927.75  936.03  944.31   952.6  960.88  969.16  977.45  985.73  994.01  1002.3
 1010.58 1018.86 1027.15 1035.43 1043.71    1052 1060.28 1068.56 1076.85 1085.13
 1093.42  1101.7 1109.98 1118.27 1126.55 1134.83 1143.12  1151.4 1159.68 1167.97
 1176.25 1184.53 1192.82  1201.1 1209.38 1220.77
  204.82   203.2  201.53  199.99  198.68  197.52  196.59  195.58  194.64   193.7
  192.94  192.11  191.34  190.63  190.14   189.4  188.74  188.09  187.15  186.46
  186.11  185.51  185.01  184.64  184.26  183.66  183.08  182.51  181.73  181.13
  180.24  179.43  178.65  178.05  177.66   177.4  176.89  176.35  175.99  175.93
  176.11  175.69  174.92  174.15  173.46  172.84  171.75  170.53  169.35  167.96
  166.49  163.98   160.4  156.63  153.18  150.35  147.88  145.98  145.24  144.53
  143.81  143.74  144.64  145.48  145.67  145.91  145.81  145.77  145.94  146.18
  146.57  147.07  147.35     147     147  147.61  147.32   147.1  147.09  147.02
  146.75   146.6  146.35  146.11  146.07  145.79  145.62  145.62  145.56  145.32
  145.36  145.34  145.23  145.07  144.81  145.09  145.47  145.33  145.02     145
  144.81  144.83  144.95     145  144.93  144.74  144.56  144.81     145  145.23
  145.42  145.58  145.47  145.43  146.22  148.39  151.44  154.71  157.93  160.23
  161.74  163.16   164.9  167.46  169.91  172.79  176.13  179.32  182.21  185.02
  187.94   190.8  193.76  196.82  199.65  202.74
                                                                                
                                                                                
                                                                                
                                                                                
                                                                                
                                                                                
                                                                                
                             146     146
                                                                                
                                                                                
                                                                                
                                                                                
                                                                                
                                                
       0    8.28   16.57   24.85   33.13   41.42    49.7   57.98   66.27   74.55
   82.83   91.12    99.4  107.68  115.97  124.25  132.54  140.82   149.1  157.39
  165.67  173.95  182.24  190.52   198.8  207.09  215.37  223.65  231.94  240.22
   248.5  256.79  265.07  273.35  281.64  289.92   298.2  306.49  314.77  323.05
  331.34  339.62   347.9  356.19  364.47  372.76  381.04  389.32  397.61  405.89
  414.17  422.46  430.74  439.02  447.31  455.59  463.87  472.16  480.44  488.72
  497.01  505.29  513.57  521.86  530.14  538.42  546.71  554.99  563.27  571.56
  579.84  588.12  596.41  604.69  712.38  720.66  728.94  737.23  745.51  753.79
  762.08  770.36  778.64  786.93  795.21  803.49  811.78  820.06  828.34  836.63
  844.91   853.2  861.48  869.76  878.05  886.33  894.61   902.9  911.18  919.46
  927.75  936.03  944.31   952.6  960.88  969.16  977.45  985.73  994.01  1002.3
 1010.58 1018.86 1027.15 1035.43 1043.71    1052 1060.28 1068.56 1076.85 1085.13
 1093.42  1101.7 1109.98 1118.27 1126.55 1134.83 1143.12  1151.4 1159.68 1167.97
 1176.25 1184.53 1192.82  1201.1 1209.38 1220.77
  204.82   203.2  201.53  199.99  198.68  197.52  196.59  195.58  194.64   193.7
  192.94  192.11  191.34  190.63  190.14   189.4  188.74  188.09  187.15  186.46
  186.11  185.51  185.01  184.64  184.26  183.66  183.08  182.51  181.73  181.13
  180.24  179.43  178.65  178.05  177.66   177.4  176.89  176.35  175.99  175.93
  176.11  175.69  174.92  174.15  173.46  172.84  171.75  170.53  169.35  167.96
  166.49  163.98   160.4  156.63  153.18  150.35  147.88  145.98  145.24  144.53
  143.81  143.74  144.64  145.48  145.67  145.91  145.81  145.77  145.94  146.18
  146.57  147.07  147.35     147     147  147.61  147.32   147.1  147.09  147.02
  146.75   146.6  146.35  146.11  146.07  145.79  145.62  145.62  145.56  145.32
  145.36  145.34  145.23  145.07  144.81  145.09  145.47  145.33  145.02     145
  144.81  144.83  144.95     145  144.93  144.74  144.56  144.81     145  145.23
  145.42  145.58  145.47  145.43  146.22  148.39  151.44  154.71  157.93  160.23
  161.74  163.16   164.9  167.46  169.91  172.79  176.13  179.32  182.21  185.02
  187.94   190.8  193.76  196.82  199.65  202.74
                                                                                
                                                                                
                                                                                
                                                                                
                                                                                
                                                                                
                                                                                
                             146     146
                                                                                
                                                                                
                                                                                
                                                                                
                                                                                
                                                
BR Coef=-1 , 0 , 0 ,, 0 ,,,0.8,0,,0,
WSPro=,,,, 1 ,,,, 0 ,,,, 0 ,,,,-1 ,-1 ,-1 , 0 , 0 , 0 , 0 , 0
BR U #Sta/Elev= 153
       0  207.28    8.28  205.42   16.57  203.61   24.85  201.72   33.13  200.33
   41.42  199.05    49.7  197.47   57.98  196.19   66.27  195.04   74.55  194.19
   82.83  193.22   91.12   192.5    99.4  191.67  107.68   190.9  115.97  190.18
  124.25  189.43  132.54  188.86  140.82  187.82   149.1  187.16  157.39  186.62
  165.67  186.04  173.95  185.46  182.24  185.14  190.52  184.72   198.8  184.12
  207.09  183.63  215.37  182.91  223.65  182.26  231.94   181.6  240.22  180.84
   248.5  179.92  256.79  178.92  265.07  178.11  273.35  177.07   280.9  176.23
  281.64  176.15  289.92  175.47   298.2  174.93  306.49  174.38  314.77  174.63
  323.05  174.72  331.34   174.3  339.62  173.74   347.9  172.71  356.19  171.84
  364.47  171.13  372.76  170.23  381.04  169.31  389.32  168.18  397.61  167.16
  405.89  165.84  414.17  163.99  422.46  161.02  430.74  158.25  439.02  155.71
  447.31  152.74  455.59  150.03  463.87  147.88  472.16     146  480.44  145.03
  488.72  144.68  497.01   143.9  505.29  143.67  513.57  144.91  521.86  145.76
  530.14  145.94  538.42  145.61   540.8  145.66  546.71  145.78  554.99  145.83
  563.27  145.85  571.56  145.98  579.84  146.27  584.75   146.4  588.12  146.49
  596.41  146.32  604.69  145.76  612.98  144.48  621.26   142.1  629.54  140.19
  637.83  140.72  645.42  141.45  646.11  141.52  654.39  142.34  662.68  142.35
  670.96  141.12  679.24  140.21  687.53   140.1  695.72  140.05  695.81  140.05
  704.09  141.16  712.38  143.82  720.66  146.41  728.94  147.05  737.23  147.28
  745.51  147.57  753.79  147.51  762.08  147.42  770.36  146.93  778.64  146.45
  786.93  146.26  795.21  146.14  803.49  145.98  811.78  146.13  820.06  146.61
  828.34  146.39  836.63  145.77  844.91  145.54   853.2   145.4  861.48     145
  869.76  145.07  878.05  145.71  886.33  145.86  894.61  145.69   902.9  145.38
  911.18  145.42  919.46  145.46  927.75  145.37  936.03  145.26  944.31  145.24
   952.6  144.76  960.88  144.58  969.16  144.54  977.45  144.82  985.73  145.03
  994.01  145.22  1002.3  145.44 1010.58   145.8 1018.86  145.68 1027.15  145.74
 1035.43  146.43 1043.71  148.81    1052  152.05 1060.28   155.2 1068.56  158.16
 1076.85  160.55 1085.13  162.51 1093.42  164.02  1101.7  165.64 1109.98  167.45
 1118.27  169.75 1126.55   172.3 1134.83  175.14 1143.12  178.12  1151.4  180.96
 1159.68  183.54 1167.97  186.31 1176.25  189.19 1184.53  191.89 1192.82  194.73
  1201.1   197.5 1209.38  199.87 1220.77  203.45
BR U #Mann= 6
       0     .06   280.9      .1   540.8     .06  584.75     .07  645.42    .033
  695.72      .1
BR D #Sta/Elev= 153
       0  202.27    8.28  201.02   16.57  199.68   24.85  198.66   33.13  197.46
   41.42  196.65    49.7  195.91   57.98  195.19   66.27  194.51   74.55  193.74
   82.83  193.11   91.12  192.29    99.4  191.38  107.68  190.56  115.97  189.98
  124.25  189.43  132.54  188.73  140.82  188.02   149.1  187.27  157.39  186.94
  165.67  186.71  173.95  186.23  182.24  185.66  190.52  184.97   198.8  184.46
  207.09  183.94  215.37  183.37  223.65  182.66  231.94  181.95  240.22  181.42
   248.5  180.53  256.79  179.96  265.07  179.51  273.35  178.79  281.64  178.32
  289.92  177.89   291.4  177.87   298.2   177.8  306.49  177.44  314.77  177.28
  323.05  177.21  331.34  177.33  339.62  177.11   347.9  176.47  356.19  175.78
  364.47   175.2  372.76  174.46  381.04  173.03  389.32  171.09  397.61  169.06
  405.89  168.46  414.17  167.98  422.46   166.1  430.74  162.72  439.02   158.9
  447.31  154.84  455.59  151.77  463.87  149.48  472.16  147.19  480.44  145.73
  488.72  144.87  497.01  143.65  505.29  143.71  513.57   145.2  521.86  146.07
  530.14  146.28  538.42  146.52  546.71  146.56  554.99  146.49  563.27  146.19
     564  146.21  571.56  146.43  579.84   146.7  586.95  146.81  588.12  146.83
  596.41  146.56  604.69  145.57  612.98  143.28  621.26  140.73  629.54  139.98
  637.83  139.97  641.76  140.02  646.11  140.06  654.39  140.14  662.68  140.02
  670.96  139.92  679.24   140.1  687.53  140.85  691.93  141.87  695.81  142.78
  704.09  144.87  712.38  146.86  720.66  147.46  728.94  147.21  737.23  147.11
  745.51  146.92  753.79  146.71  762.08  146.56  770.36  146.44  778.64  146.23
  786.93  146.43  795.21   146.2  803.49  146.24  811.78  146.16  820.06  146.05
  828.34  146.05  836.63   145.9  844.91  145.96   853.2  145.75  861.48  145.46
  869.76  145.48  878.05  145.59  886.33  145.49  894.61  145.33   902.9  145.59
  911.18   145.7  919.46   145.6  927.75  145.39  936.03  145.13  944.31  144.82
   952.6   144.6  960.88  144.54  969.16  144.68  977.45  144.65  985.73  144.82
  994.01  144.85  1002.3  145.24 1010.58  145.55 1018.86  145.17 1027.15  144.96
 1035.43  144.95 1043.71  145.21    1052  146.02 1060.28  147.71 1068.56  151.11
 1076.85  154.83 1085.13  157.67 1093.42  159.58  1101.7  161.13 1109.98  162.89
 1118.27  165.03 1126.55   167.4 1134.83  170.09 1143.12  173.13  1151.4  176.53
 1159.68  179.98 1167.97  183.14 1176.25  186.12 1184.53  189.35 1192.82  192.45
  1201.1  195.29 1209.38  198.42 1220.77  201.73
BR D #Mann= 6
       0     .06   291.4      .1     564     .06  586.95     .07  641.76    .033
  691.93      .1
BC Design=,, 0 ,, 0 ,,,,,,
BC Use User HTab Curves=0
BC User HTab FreeFlow(D)= 0

Type RM Length L Ch R = 1 ,61908   ,50,50.09,50.08
XS GIS Cut Line= 2
1640689.26068552744940.4444587531639657.63491243744287.727283731
#Sta/Elev= 30
       0  202.27   33.13  197.46  107.68  190.56   291.4  177.87  339.62  177.11
  364.47   175.2  381.04  173.03  397.61  169.06  414.17  167.98  422.46   166.1
  455.59  151.77  472.16  147.19  497.01  143.65  521.86  146.07     564  146.21
  586.95  146.81  596.41  146.56  621.26  140.73  629.54  139.98  670.96  139.92
  687.53  140.85  712.38  146.86  960.88  144.54    1052  146.02 1060.28  147.71
 1085.13  157.67 1109.98  162.89 1134.83  170.09 1192.82  192.45 1220.77  201.73
#Mann= 6 ,-1 , 0
       0     .06       0   291.4      .1       0     564     .06       0
  586.95     .07       0  596.41    .035       0  712.38      .1       0
#XS Ineff= 2 , 0
       0     579  143.71     733       0   144.6
Permanent Ineff=
       F       F
Bank Sta=596.41,712.38
XS Rating Curve= 0 ,0
Exp/Cntr=0.5,0.3

Type RM Length L Ch R = 1 ,61858   ,478.22,582.45,577.27
XS GIS Cut Line= 3
1640715.99440835744898.1915527431639698.71439607744254.551045567
1639555.37485938744166.405319393
#Sta/Elev= 30
       0  200.19  165.67  186.75  265.07  180.29   304.6  178.75   347.9  178.45
  381.04   176.5  405.89  173.73  430.74  167.59  472.16  150.06  488.72   145.9
  505.29  143.47  554.99  146.66  588.12  146.97  604.69  145.31  621.26   140.6
  646.11  139.69  687.53  140.24  695.81  141.75  704.09  144.89  712.38  146.75
  720.66  147.12   952.6  144.39 1060.28  145.25 1068.56  146.54 1093.42  156.22
 1143.12  168.19 1228.45  198.02 1269.54  209.43 1302.41  217.18 1372.07  226.49
#Mann= 4 ,-1 , 0
       0     .06       0   304.6      .1       0  604.69    .035       0
  704.09      .1       0
Bank Sta=604.69,704.09
XS Rating Curve= 0 ,0
Exp/Cntr=0.3,0.1

Type RM Length L Ch R = 1 ,61275   ,628.47,624.65,622.41
XS GIS Cut Line= 2
1640863.11866555 744778.07386823 1640146.8147929743750.010797113
#Sta/Elev= 30
       0  203.94   68.25   194.7  153.57   187.9  349.79  175.85  503.08  171.02
  546.02  165.75  571.61  158.22  588.68  151.04  605.74  146.55  614.27  145.06
  652.69  143.71  708.12  142.52  776.37  144.09  819.03   143.2  856.05  144.04
  885.62   142.1  904.35  137.87  912.88  137.39  921.41  137.89  937.37  142.39
  955.53  147.51  964.07  151.13  989.66  175.01 1006.72  184.34 1040.85  200.54
 1074.98  213.45 1126.17  228.86 1177.36  240.99 1220.01  247.09    1253  248.84
#Mann= 6 ,-1 , 0
       0     .06       0  503.08      .1       0  652.69     .08       0
  856.05     .06       0  885.62    .035       0  937.37      .1       0
Bank Sta=885.62,937.37
XS Rating Curve= 0 ,0
Exp/Cntr=0.3,0.1

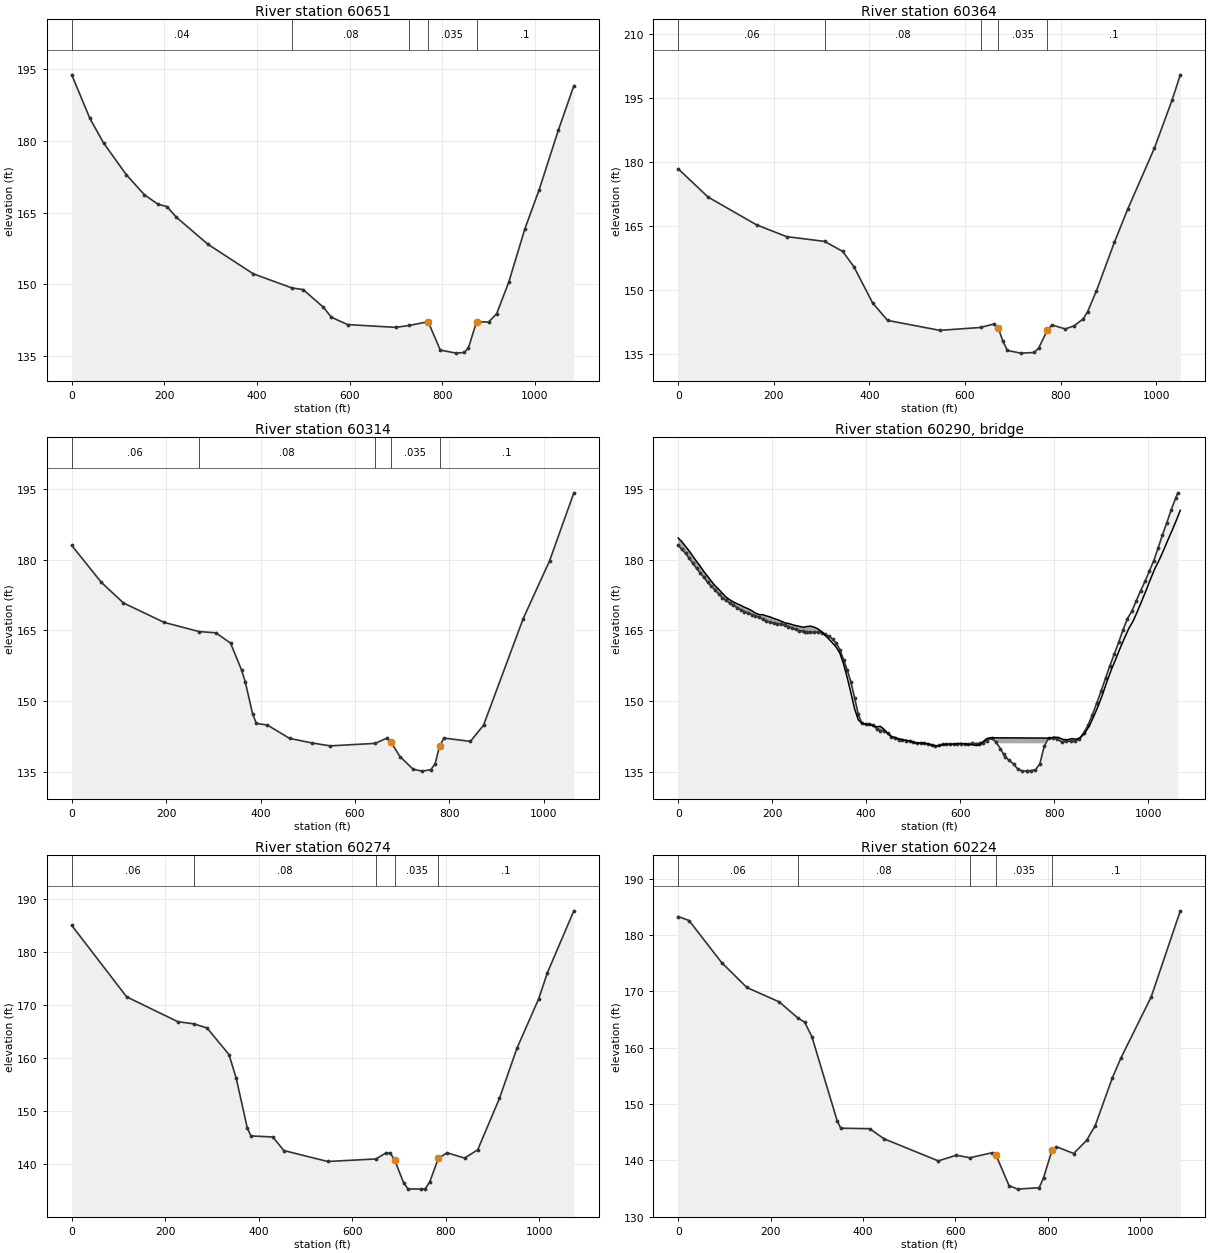
Type RM Length L Ch R = 1 ,60651   ,270.16,286.36,279.32
XS GIS Cut Line= 4
  1641400.372117744311.7115237121641063.22631776743967.040148571
1640765.21351303743563.6692816171640711.02936678743479.382831812
#Sta/Elev= 30
       0  193.88   39.17  184.73   68.54  179.61   117.5  172.97  156.67  168.74
  186.05  166.75  205.63  166.24  225.22  164.07  293.76  158.36  391.68  152.16
   475.6  149.18  499.55  148.85  543.07  145.15  560.48  143.05  595.29  141.51
  699.73  140.92  728.79  141.33  769.35  142.11  795.46  136.17  829.48  135.52
  847.68  135.66  856.38  136.64  873.79  142.08   899.9  142.04  917.31   143.8
  943.42  150.43  978.23  161.61 1008.63  169.69 1050.24  182.23 1083.86  191.59
#Mann= 5 ,-1 , 0
       0     .04       0   475.6     .08       0  728.79     .06       0
  769.35    .035       0  873.79      .1       0
Bank Sta=769.35,873.79
XS Rating Curve= 0 ,0
Exp/Cntr=0.3,0.1

Type RM Length L Ch R = 1 ,60364   ,50.25,50.15,50.04
XS GIS Cut Line= 3
1641423.96001515744159.5981069651641129.49153301743568.169642493
1640872.03128214743275.501152202
#Sta/Elev= 30
       0  178.37   62.56  171.75  164.21  165.22  226.77  162.48  306.11  161.36
  344.06  159.01  367.52  155.42  406.62  146.95   437.9  142.83  547.38  140.49
  632.49  141.17  660.68  141.99     670  140.93  679.33  137.94  688.65  135.78
  716.62  135.15  744.59   135.3  753.91  136.29  772.56  140.59  781.88  141.77
  809.85  140.82   828.5  141.57  847.14  143.17  856.46  144.85  875.11  149.79
   912.4  161.11  940.37   168.9  996.31  183.24  1033.6  194.62 1050.48  200.43
#Mann= 5 ,-1 , 0
       0     .06       0  306.11     .08       0  632.49     .06       0
     670    .035       0  772.56      .1       0
Bank Sta=670,772.56
XS Rating Curve= 0 ,0
Exp/Cntr=0.5,0.3

Type RM Length L Ch R = 1 ,60314   ,40.2,40.12,40.03
XS GIS Cut Line= 3
1641468.71902218744137.3128811721641171.34242132743540.043573692
 1640909.5725569743242.476120993
#Sta/Elev= 30
       0     183   62.56  175.17  109.48  170.79  195.49  166.68  269.18  164.73
  304.97  164.46  336.25  162.29   359.7  156.55  367.52  154.04  383.16   147.2
  390.98  145.23  414.44  144.88  461.36  142.05  508.28  141.09  547.38  140.46
  642.58  140.99  667.21  142.09  676.53  141.21  695.17   138.2  723.14   135.5
  741.79   135.1  760.44   135.4  769.76  136.66  779.08   140.4   788.4  142.12
  844.34  141.41  872.31  144.86  956.22  167.47 1012.16  179.75 1063.53  194.17
#Mann= 5 ,-1 , 0
       0     .06       0  269.18     .08       0  642.58     .06       0
  676.53    .035       0  779.08      .1       0
#XS Ineff= 2 , 0
       0     644  140.46     808       0  141.48
Permanent Ineff=
       F       F
Bank Sta=676.53,779.08
XS Rating Curve= 0 ,0
Exp/Cntr=0.5,0.3

Type RM Length L Ch R = 3 ,60290   ,,,
BEGIN DESCRIPTION:
Ped Bridge - No survey info.  Assumed elevation based on lidar bank elevation.  Assumed 1' deck thickness.
END DESCRIPTION:
Bridge Culvert--1,0,-1,-1, 0
Deck Dist Width WeirC Skew NumUp NumDn MinLoCord MaxHiCord MaxSubmerge Is_Ogee
20,8,2.6,0, 117, 117, , , 0.95, 0, 0,0,,
       0    7.82   15.64   23.46   31.28    39.1   46.92   54.74   62.56   70.38
    78.2   86.02   93.84  101.66  109.48  117.29  125.11  132.93  140.75  148.57
  156.39  164.21  172.03  179.85  187.67  195.49  203.31  211.13  218.95  226.77
  234.59  242.41  250.23  258.05  265.87  273.69  281.51  289.33  297.15  304.97
  312.79  320.61  328.43  336.25  344.06  351.88   359.7  367.52  375.34  383.16
  390.98   398.8  406.62  414.44  422.26  430.08   437.9  445.72  453.54  461.36
  469.18     477  484.82  492.64  500.46  508.28   516.1  523.92  531.74  539.56
  547.38   555.2  563.01  570.83  578.65  586.47  594.29  602.11  609.93  617.75
  625.57  633.39  641.21  649.03  656.85  664.67  791.01  800.34  809.66  818.98
  828.31  837.63  846.95  856.28   865.6  874.92  884.25  893.57  902.89  912.21
  921.54  930.86  940.18  949.51  958.83  968.15  977.48   986.8  996.12 1005.45
 1014.77 1024.09 1033.41 1042.74 1052.06 1061.38 1068.74
  184.57  183.79   182.8  181.82   180.7   179.6  178.58  177.43  176.45  175.43
  174.46  173.72  172.86  172.05  171.49  171.03  170.63  170.31  169.89  169.57
  169.17  168.66  168.34   168.3  168.05  167.83  167.51  167.26  166.93  166.59
  166.44  166.21  165.98  165.83  165.64  165.79  165.87  165.67  165.29  164.75
  163.94  163.13   162.3  161.42  160.13  157.85  154.97  151.73  148.37     146
  145.25  145.11  144.95   144.8  144.51  144.61  144.01  143.12  142.46  142.24
  141.96  141.81  141.62  141.47  141.21  141.02  141.14  140.99  140.92  140.64
  140.45  140.44  140.72  140.77  140.78  140.84  140.94  140.98  140.87  140.74
  140.71  140.55  140.68  141.38  142.02  142.18  142.11  142.31  142.25  141.82
  141.77  141.99  141.88  142.21  143.19  144.69  146.67  148.85  151.28  154.02
  156.54  158.76  161.08  163.26  165.32  166.93  169.01  171.24  173.53  175.91
  178.13  179.97  182.05  184.27  186.37  188.61  190.47
                                                                                
                                                                                
                                                                                
                                                                                
                                                                                
                                                                                
                                                                                
                                                                                
                                             141     141
                                                                                
                                                                                
                                                        
       0    7.82   15.64   23.46   31.28    39.1   46.92   54.74   62.56   70.38
    78.2   86.02   93.84  101.66  109.48  117.29  125.11  132.93  140.75  148.57
  156.39  164.21  172.03  179.85  187.67  195.49  203.31  211.13  218.95  226.77
  234.59  242.41  250.23  258.05  265.87  273.69  281.51  289.33  297.15  304.97
  312.79  320.61  328.43  336.25  344.06  351.88   359.7  367.52  375.34  383.16
  390.98   398.8  406.62  414.44  422.26  430.08   437.9  445.72  453.54  461.36
  469.18     477  484.82  492.64  500.46  508.28   516.1  523.92  531.74  539.56
  547.38   555.2  563.01  570.83  578.65  586.47  594.29  602.11  609.93  617.75
  625.57  633.39  641.21  649.03  656.85  664.67  791.01  800.34  809.66  818.98
  828.31  837.63  846.95  856.28   865.6  874.92  884.25  893.57  902.89  912.21
  921.54  930.86  940.18  949.51  958.83  968.15  977.48   986.8  996.12 1005.45
 1014.77 1024.09 1033.41 1042.74 1052.06 1061.38 1068.74
  184.57  183.79   182.8  181.82   180.7   179.6  178.58  177.43  176.45  175.43
  174.46  173.72  172.86  172.05  171.49  171.03  170.63  170.31  169.89  169.57
  169.17  168.66  168.34   168.3  168.05  167.83  167.51  167.26  166.93  166.59
  166.44  166.21  165.98  165.83  165.64  165.79  165.87  165.67  165.29  164.75
  163.94  163.13   162.3  161.42  160.13  157.85  154.97  151.73  148.37     146
  145.25  145.11  144.95   144.8  144.51  144.61  144.01  143.12  142.46  142.24
  141.96  141.81  141.62  141.47  141.21  141.02  141.14  140.99  140.92  140.64
  140.45  140.44  140.72  140.77  140.78  140.84  140.94  140.98  140.87  140.74
  140.71  140.55  140.68  141.38  142.02  142.18  142.11  142.31  142.25  141.82
  141.77  141.99  141.88  142.21  143.19  144.69  146.67  148.85  151.28  154.02
  156.54  158.76  161.08  163.26  165.32  166.93  169.01  171.24  173.53  175.91
  178.13  179.97  182.05  184.27  186.37  188.61  190.47
                                                                                
                                                                                
                                                                                
                                                                                
                                                                                
                                                                                
                                                                                
                                                                                
                                             141     141
                                                                                
                                                                                
                                                        
BR Coef=-1 , 0 , 0 ,, 0 ,,,0.8,0,,0,
WSPro=,,,, 1 ,,,, 0 ,,,, 0 ,,,,-1 ,-1 ,-1 , 0 , 0 , 0 , 0 , 0
BR U #Sta/Elev= 133
       0     183    7.82  182.18   15.64  181.32   23.46  180.26   31.28  179.21
    39.1  178.11   46.92  177.13   54.74  176.21   62.56  175.17   70.38  174.36
    78.2  173.57   86.02  172.72   93.84   171.9  101.66  171.35  109.48  170.79
  117.29  170.33  125.11   169.8  132.93  169.33  140.75  168.96  148.57  168.62
  156.39  168.34  164.21  167.99  172.03  167.75  179.85  167.34  187.67  167.02
  195.49  166.68  203.31  166.52  211.13  166.37  218.95  166.31  226.77  166.08
  234.59  165.78  242.41   165.5  250.23  165.17  258.05  164.92  265.87  164.82
  269.18  164.73  273.69  164.62  281.51  164.56  289.33  164.57  297.15  164.63
  304.97  164.46  312.79  164.14  320.61  163.72  328.43  163.12  336.25  162.29
  344.06  160.86  351.88  158.78   359.7  156.55  367.52  154.04  375.34  150.68
  383.16   147.2  390.98  145.23   398.8  145.06  406.62  145.17  414.44  144.88
  422.26  144.11  430.08  143.72   437.9   143.7  445.72  143.15  453.54  142.43
  461.36  142.05  469.18  141.81     477  141.72  484.82   141.6  492.64  141.49
  500.46  141.29  508.28  141.09   516.1  141.04  523.92  140.97  531.74  140.83
  539.56  140.69  547.38  140.46   555.2  140.55  563.01  140.85  570.83  140.86
  578.65  140.89  586.47   140.8  594.29  140.82  602.11  140.83  609.93   140.9
  617.75   140.9  625.57  140.97  633.39  140.96  641.21  140.96  642.58  140.99
  649.03  141.16  656.85  141.58  667.21  142.09  676.53  141.21  685.85  139.87
  692.46  138.69  695.17   138.2   704.5  137.41  713.82  136.59  723.14   135.5
  732.47  135.15  741.79   135.1  742.55  135.11  751.11  135.22  760.44   135.4
  769.76  136.66  779.08   140.4   788.4  142.12  797.73  142.07  807.05  141.89
  816.37  141.29   825.7  141.41  835.02  141.48  844.34  141.41  853.67  141.98
  862.99  143.21  872.31  144.86  881.64  147.07  890.96  149.59  900.28  152.09
   909.6  154.85  918.93  157.49  928.25  159.96  937.57  162.44   946.9  165.12
  956.22  167.47  965.54  169.07  974.87  171.25  984.19  173.37  993.51  175.36
 1002.84  177.57 1012.16  179.75 1021.48  182.46  1030.8  185.27 1040.13  187.86
 1049.45  190.59 1058.77  193.04 1063.53  194.17
BR U #Mann= 5
       0     .06  269.18     .08  642.58     .06  692.46    .033  742.55      .1
BR D #Sta/Elev= 134
       0  184.97    7.82  184.55   15.64  183.65   23.46  182.59   31.28   181.6
    39.1   180.6   46.92  179.69   54.74  178.66   62.56  177.72   70.38  176.68
    78.2  175.48   86.02  174.64   93.84  173.82  101.66  172.99  109.48  172.19
  117.29  171.51  125.11  171.03  132.93  170.69  140.75  170.48  148.57  170.17
  156.39   169.7  164.21  169.23  172.03  169.09  179.85  168.83  187.67  168.46
  195.49  168.22  203.31  168.15  211.13  167.71  218.95  167.23  226.77  166.82
  234.59   166.6  242.41  166.36  250.23  166.53  258.05   166.4  261.62   166.4
  265.87  166.39  273.69  166.59  281.51  166.14  289.33  165.63  297.15  164.83
  304.97  164.22  312.79  163.39  320.61  162.19  328.43  161.93  336.25  160.63
  344.06  158.48  351.88  156.11   359.7  152.99  367.52  149.77  375.34  146.82
  383.16  145.28  390.98  145.21   398.8  145.34  406.62  145.39  414.44  145.11
  422.26  144.92  430.08  145.08   437.9  144.38  445.72  143.16  453.54  142.53
  461.36  142.43  469.18  142.18     477  141.93  484.82  141.99  492.64  141.79
  500.46  141.71  508.28  141.49   516.1  141.22  523.92  141.22  531.74  140.96
  539.56  140.92  547.38  140.46   555.2  140.44  563.01   140.4  570.83  140.55
  578.65  140.55  586.47   140.5  594.29  140.72  602.11  140.72  609.93  140.55
  617.75   140.4  625.57  140.37  633.39  140.46  641.21  140.75  649.03  140.81
  650.61  140.94  656.85  141.47  664.67   141.7  672.42   142.1  681.75  141.99
  691.07  140.65   699.8   138.6  700.39  138.46  709.72  136.48  719.04   135.3
  728.36  135.28  737.69  135.29  747.01  135.25  749.95  135.27  756.33  135.33
  765.66  136.61  774.98  138.56   784.3  141.07  793.62  141.84  802.95   142.1
  812.27  141.54  821.59  141.19  830.92  140.98  840.24  141.11  849.56  141.54
  858.89  142.06  868.21  142.65  877.53  144.54  886.86  146.41  896.18  148.36
   905.5  150.32  914.82  152.36  924.15  154.59  933.47  156.98  942.79  159.54
  952.12  161.78  961.44  163.55  970.76  165.62  980.09  167.58  989.41  169.39
  998.73  171.13 1008.05  173.24 1017.38  176.04  1026.7  177.14 1036.02  179.15
 1045.35  181.11 1054.67  183.16 1063.99  185.11 1073.96  187.72
BR D #Mann= 5
       0     .06  261.62     .08  650.61     .06   699.8    .033  749.95      .1
BC Design=,, 0 ,, 0 ,,,,,,
BC Use User HTab Curves=0
BC User HTab FreeFlow(D)= 0

Type RM Length L Ch R = 1 ,60274   ,50.25,50.15,50.04
XS GIS Cut Line= 3
1641504.52622785744119.4847005461641204.82313202743517.542718634
1640939.60557675743216.056096017
#Sta/Elev= 30
       0  184.97  117.29  171.51  226.77  166.82  261.62   166.4  289.33  165.63
  336.25  160.63  351.88  156.11  375.34  146.82  383.16  145.28  430.08  145.08
  453.54  142.53  547.38  140.46  650.61  140.94  672.42   142.1  681.75  141.99
  691.07  140.65  709.72  136.48  719.04   135.3  747.01  135.25  756.33  135.33
  765.66  136.61   784.3  141.07  802.95   142.1  840.24  141.11  868.21  142.65
  914.82  152.36  952.12  161.78  998.73  171.13 1017.38  176.04 1073.96  187.72
#Mann= 5 ,-1 , 0
       0     .06       0  261.62     .08       0  650.61     .06       0
  691.07    .035       0   784.3      .1       0
#XS Ineff= 2 , 0
       0     669  140.44     804       0  140.98
Permanent Ineff=
       F       F
Bank Sta=691.07,784.3
XS Rating Curve= 0 ,0
Exp/Cntr=0.5,0.3

Type RM Length L Ch R = 1 ,60224   ,360.52,325.38,324.56
XS GIS Cut Line= 3
1641549.28523488744097.1994747671641246.67402034743489.416649833
1640977.14685152743183.031064808
#Sta/Elev= 30
       0  183.27   23.46  182.56   93.84  175.11  148.57  170.68  218.95  168.11
  258.27  165.32  273.69  164.53  289.33  161.96  344.06  147.04  351.88  145.72
  414.44  145.63  445.72  143.83  563.01  139.92  602.11  140.93  631.23  140.48
  678.95  141.35  688.27  140.89  716.24  135.53  734.89  134.91   781.5  135.17
  790.83  136.91  809.47  141.84   818.8  142.44  856.09  141.23  884.06  143.55
   902.7  146.17     940  154.68  958.64  158.21  1023.9     169 1087.01  184.28
#Mann= 5 ,-1 , 0
       0     .06       0  258.27     .08       0  631.23     .06       0
  688.27    .035       0  809.47      .1       0
Bank Sta=688.27,809.47
XS Rating Curve= 0 ,0
Exp/Cntr=0.3,0.1

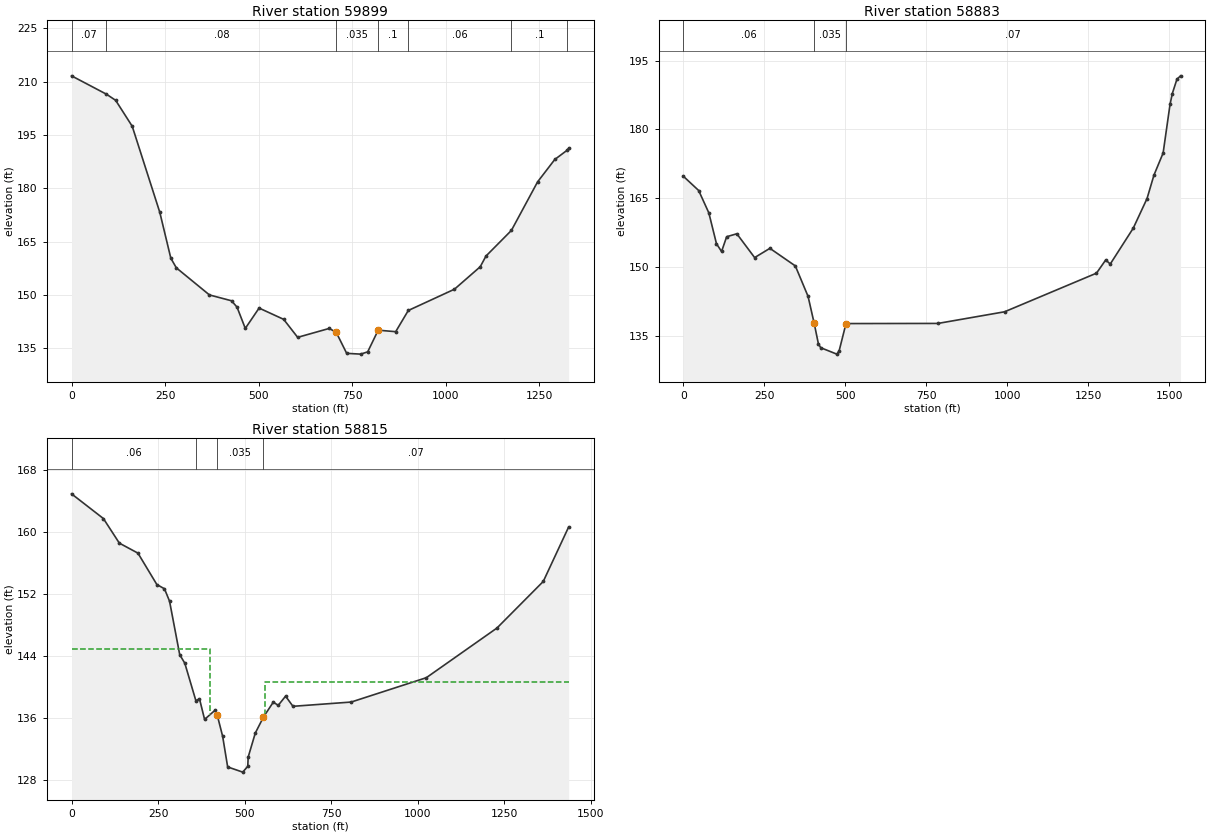
Type RM Length L Ch R = 1 ,59899   ,1049.56,1015.49,771.63
XS GIS Cut Line= 4
1642115.60959351 743578.512181581641612.78851007743412.688207254
1641361.37796834743129.1827027651640977.43475276 742958.61298117
#Sta/Elev= 30
       0  211.61   93.39  206.44  117.93  204.72  162.16  197.44  235.87  173.24
  265.35  160.34  280.09  157.63  368.54  150.01  427.51  148.37  442.25  146.59
  464.36   140.6  501.22  146.32  566.88  143.15  604.31  138.09  688.51  140.59
  707.22  139.52  735.29  133.59  772.71  133.37  791.43  134.01  819.49   140.1
  866.27  139.68  899.93  145.64 1023.28  151.62 1092.21  157.94 1107.53  160.94
 1175.46  168.15 1245.41  181.79 1291.37  188.09 1324.52   190.7 1328.51  191.25
#Mann= 7 ,-1 , 0
       0     .07       0   93.39     .08       0  707.22    .035       0
  819.49      .1       0  899.93     .06       0 1175.46      .1       0
 1324.52     .06       0
Bank Sta=707.22,819.49
XS Rating Curve= 0 ,0
Exp/Cntr=0.3,0.1

Type RM Length L Ch R = 1 ,58883   ,62.17,68.27,87.84
XS GIS Cut Line= 3
1642644.53407857742802.7690895051642285.67960964742620.447867364
1641168.60037552742438.126645207
#Sta/Elev= 30
       0  169.76   47.11  166.66   78.52  161.77  102.07  155.04  117.77  153.35
  133.48  156.57  164.88  157.22  219.85  152.02  266.96  154.04  345.47   150.2
  384.73  143.56  403.54   137.7   416.7  133.18  423.79  132.35  473.44  130.95
  480.53  131.64  501.81  137.62  785.52  137.65   991.2  140.19 1274.91  148.62
 1303.28  151.49 1317.47  150.62 1388.39  158.44 1430.95  164.91 1452.23  170.01
  1480.6  174.85 1501.87  185.44 1508.97  187.83 1523.15  190.94 1534.38  191.69
#Mann= 3 , 0 , 0
       0     .06       0  403.54    .035       0  501.81     .07       0
Bank Sta=403.54,501.81
XS Rating Curve= 0 ,0
Exp/Cntr=0.5,0.3

Type RM Length L Ch R = 1 ,58815   ,67.27,67.05,69.82
BEGIN DESCRIPTION:
Modified under water portion by 1 foot as per "flow depth" in bridge inspection notes.
END DESCRIPTION:
XS GIS Cut Line= 6
 1642699.6220946742716.0306321681642494.89812669742623.866863534
1642292.86616534742559.1619329151642179.08201508742527.773201808
1641792.61745909742456.028099298 1641306.6423327 742403.46801807
#Sta/Elev= 30
       0  164.93   92.12  161.74  138.18  158.57  191.92  157.28  246.55  153.23
  268.58  152.68  283.27  151.08  312.65  144.18  327.35  143.08   359.3  138.25
  369.78  138.49   384.5  135.83  413.93  136.98  421.29  136.34  436.65  133.66
  451.18   129.7  494.75  129.03  509.27  129.78  510.43  130.96  531.05  134.07
  554.69  136.14  583.07  138.06  597.27  137.64  618.56  138.83  639.85  137.52
  808.14  138.07 1025.26  141.21 1229.44  147.62 1363.21  153.63 1436.61  160.66
#Mann= 4 ,-1 , 0
       0     .06       0   359.3     .07       0  421.29    .035       0
  554.69     .07       0
#XS Ineff= 2 , 0
       0     400  144.88     558       0   140.6
Permanent Ineff=
       F       F
Bank Sta=421.29,554.69
XS Rating Curve= 0 ,0
Exp/Cntr=0.5,0.3