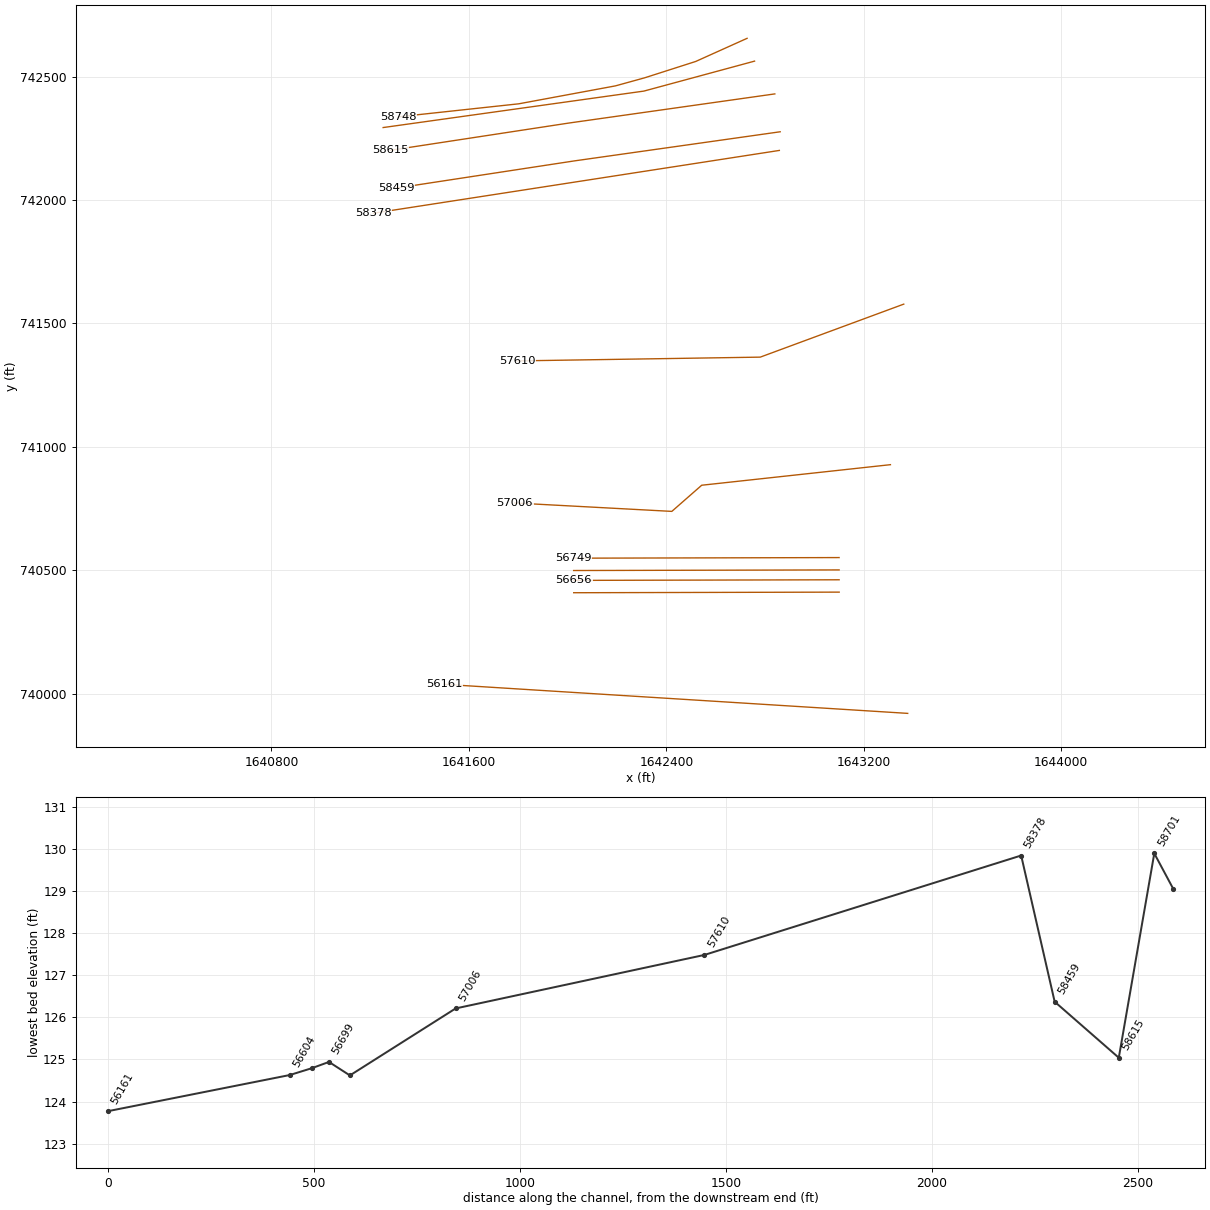
HEC-RAS study bigelkcreek.prj: Big Elk Creek

--- bigelkcreek.g23 (geometry) --- (continued)

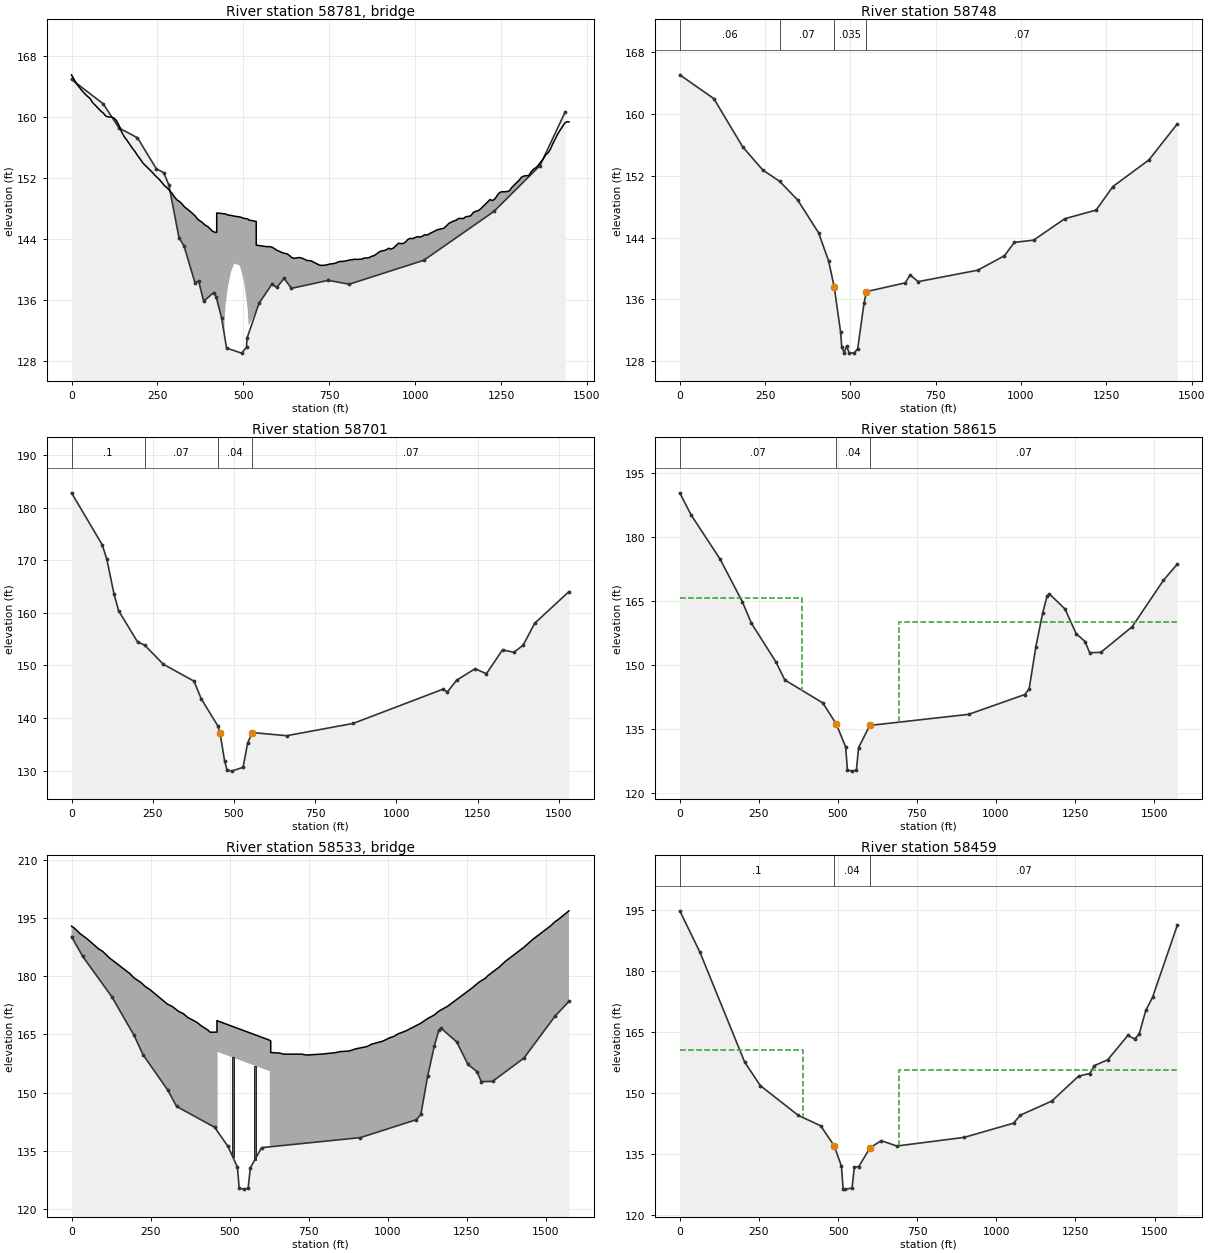
Type RM Length L Ch R = 3 ,58781   ,,,
BEGIN DESCRIPTION:
Telegraph Rd.  CE050407FS-10  Approximate Reach
Top of road from LIDAR.
END DESCRIPTION:
Bridge Culvert--1,0,-1,-1, 0
Deck Dist Width WeirC Skew NumUp NumDn MinLoCord MaxHiCord MaxSubmerge Is_Ogee
20,28,2.6,0, 197, 197, , , 0.95, 0, 0,0,,
       0    7.68   15.35   23.03   30.71   38.38   46.06   53.74   61.41   69.09
   76.77   84.44   92.12    99.8  107.47  115.15  122.83   130.5  138.18  145.86
  153.53  161.21  168.89  176.56  184.24  191.92  199.59  207.27  214.95  222.62
  226.53  233.88  241.22  248.57  255.91  263.26   270.6  277.95  285.29  292.64
  299.98  307.33  314.67  322.02  329.36  336.71  344.05   351.4     359  366.36
  373.72  381.08  388.43  395.79  403.15  410.51  417.87 422.499   422.5  425.23
  445.25   448.1  454.45  463.81  473.48  489.77  502.48  512.91  515.57   537.5
   537.6     569  576.09  583.19  590.29  597.38  604.48  611.58  618.67  625.77
  632.87  639.96  647.06  654.16  661.25  668.35  675.44  683.86  691.01  698.16
  705.32  712.47  719.62  726.78  733.93  741.08  748.24  755.39  762.54   769.7
  776.85     784  787.67  794.78   801.9  809.02  816.14  823.25  830.37  837.49
  844.61  851.72  858.84  865.96  873.08  880.19  887.31  894.43  901.55  908.66
  915.78   922.9  930.02  937.13  944.25  951.37  957.55  964.59  971.63  978.67
  985.71  992.75   999.8 1006.84 1013.88 1020.92 1027.96    1035 1042.04 1049.08
 1056.12 1063.16  1070.2 1077.24 1084.28 1091.33 1098.37 1105.41 1112.45 1119.49
 1126.53 1133.57 1140.61 1147.65 1154.69 1161.73 1168.77 1175.81 1182.86  1189.9
 1196.94 1203.98 1211.02 1218.06  1225.1 1232.14 1239.18 1246.22 1253.26  1260.3
 1267.34 1274.39 1281.43 1288.47 1295.51 1302.55 1309.59 1316.63 1323.67 1330.71
 1337.75 1344.79 1351.83 1358.88 1365.92 1372.96    1380 1387.04 1394.08 1401.12
 1408.16  1415.2 1422.24 1429.28 1436.32 1443.36 1447.66
  165.54   164.9  164.32  163.88  163.45  163.07  162.73  162.44   161.9  161.55
  161.19  160.82  160.54  160.13     160  160.01  159.88  159.57  158.88  158.04
  157.41  156.96  156.45  155.94   155.5  154.96  154.51  153.99  153.65   153.3
  153.13   152.8  152.43  152.11  151.79  151.39  150.99  150.73  150.37  149.99
  149.49  149.11  148.91  148.57  148.19  147.94  147.68  147.37  147.07  146.64
  146.38  146.16  145.83  145.66  145.33  145.02  144.88  144.88  147.41  147.41
   147.3   147.3  147.15   147.1     147   146.9   146.7  146.65   146.5 146.301
 143.195  142.99  143.01  142.93  142.75  142.52   142.4  142.24  142.13  142.08
   141.9  141.59  141.47  141.51  141.57  141.52  141.41   141.2  141.17  141.13
  140.94  140.79  140.61  140.53  140.56  140.59  140.68  140.74  140.77  140.86
  141.01  141.07  141.05   141.1  141.16  141.25  141.27  141.35  141.32  141.34
  141.36  141.51  141.51  141.56  141.73  141.82  142.03  142.28  142.43  142.48
  142.58  142.79  142.67  142.83  143.13  143.44  143.41   143.4  143.59  143.94
  144.09  144.05  144.18  144.31  144.26  144.36  144.57  144.52  144.71  144.86
  145.02  145.19  145.27  145.34  145.43  145.75  146.06  146.22  146.37  146.47
   146.7   146.7  146.69  146.93  146.97  147.05  147.46  147.64   147.7  147.93
  148.24  148.53  148.87  149.18  149.04  149.27  149.74  150.12   150.2   150.2
  150.23  150.33  150.77   151.1  151.41  151.71  152.11  152.27  152.31  152.33
  152.82  153.18  153.37   153.7  154.14  154.51  155.06  155.31  155.82  156.55
  157.17  157.79   158.3  158.78  159.26   159.4  159.36
                                                                                
                                                                                
                                                                                
                                                                                
                                                                                
                                                                                
  133.37  135.25  137.54  139.64   140.8  140.51  138.35  134.68  132.65       0
                                                                                
                                                                                
                                                                                
                                                                                
                                                                                
                                                                                
                                                                                
                                                                                
                                                                                
                                                                                
                                                                                
                                                                                
                                                        
       0   27.68   35.35   43.03   50.71   58.38   66.06   73.74   81.41   89.09
   96.77  104.44  112.12   119.8  127.47  135.15  142.83   150.5  158.18  165.86
  173.53  181.21  188.89  196.56  204.24  211.92  219.59  227.27  234.95  242.62
  246.53  253.88  261.22  268.57  275.91  283.26   290.6  297.95  305.29  312.64
  319.98  327.33  334.67  342.02  349.36  356.71  364.05   371.4     379  386.36
  393.72  401.08  408.43  415.79  423.15  430.51  437.87 442.499   442.5  445.23
  465.25   468.1  474.45  483.81  493.48  509.77  522.48  532.91  535.57   557.5
   557.6     589  596.09  603.19  610.29  617.38  624.48  631.58  638.67  645.77
  652.87  659.96  667.06  674.16  681.25  688.35  695.44  703.86  711.01  718.16
  725.32  732.47  739.62  746.78  753.93  761.08  768.24  775.39  782.54   789.7
  796.85     804  807.67  814.78   821.9  829.02  836.14  843.25  850.37  857.49
  864.61  871.72  878.84  885.96  893.08  900.19  907.31  914.43  921.55  928.66
  935.78   942.9  950.02  957.13  964.25  971.37  977.55  984.59  991.63  998.67
 1005.71 1012.75  1019.8 1026.84 1033.88 1040.92 1047.96    1055 1062.04 1069.08
 1076.12 1083.16  1090.2 1097.24 1104.28 1111.33 1118.37 1125.41 1132.45 1139.49
 1146.53 1153.57 1160.61 1167.65 1174.69 1181.73 1188.77 1195.81 1202.86  1209.9
 1216.94 1223.98 1231.02 1238.06  1245.1 1252.14 1259.18 1266.22 1273.26  1280.3
 1287.34 1294.39 1301.43 1308.47 1315.51 1322.55 1329.59 1336.63 1343.67 1350.71
 1357.75 1364.79 1371.83 1378.88 1385.92 1392.96    1400 1407.04 1414.08 1421.12
 1428.16  1435.2 1442.24 1449.28 1456.32 1463.36 1467.66
  165.54   164.9  164.32  163.88  163.45  163.07  162.73  162.44   161.9  161.55
  161.19  160.82  160.54  160.13     160  160.01  159.88  159.57  158.88  158.04
  157.41  156.96  156.45  155.94   155.5  154.96  154.51  153.99  153.65   153.3
  153.13   152.8  152.43  152.11  151.79  151.39  150.99  150.73  150.37  149.99
  149.49  149.11  148.91  148.57  148.19  147.94  147.68  147.37  147.07  146.64
  146.38  146.16  145.83  145.66  145.33  145.02  144.88  144.88  147.41  147.41
   147.3   147.3  147.15   147.1     147   146.9   146.7  146.65   146.5 146.301
 143.195  142.99  143.01  142.93  142.75  142.52   142.4  142.24  142.13  142.08
   141.9  141.59  141.47  141.51  141.57  141.52  141.41   141.2  141.17  141.13
  140.94  140.79  140.61  140.53  140.56  140.59  140.68  140.74  140.77  140.86
  141.01  141.07  141.05   141.1  141.16  141.25  141.27  141.35  141.32  141.34
  141.36  141.51  141.51  141.56  141.73  141.82  142.03  142.28  142.43  142.48
  142.58  142.79  142.67  142.83  143.13  143.44  143.41   143.4  143.59  143.94
  144.09  144.05  144.18  144.31  144.26  144.36  144.57  144.52  144.71  144.86
  145.02  145.19  145.27  145.34  145.43  145.75  146.06  146.22  146.37  146.47
   146.7   146.7  146.69  146.93  146.97  147.05  147.46  147.64   147.7  147.93
  148.24  148.53  148.87  149.18  149.04  149.27  149.74  150.12   150.2   150.2
  150.23  150.33  150.77   151.1  151.41  151.71  152.11  152.27  152.31  152.33
  152.82  153.18  153.37   153.7  154.14  154.51  155.06  155.31  155.82  156.55
  157.17  157.79   158.3  158.78  159.26   159.4  159.36
                                                                                
                                                                                
                                                                                
                                                                                
                                                                                
                                                                                
  133.37  135.25  137.54  139.64   140.8  140.51  138.35  134.68  132.65       0
                                                                                
                                                                                
                                                                                
                                                                                
                                                                                
                                                                                
                                                                                
                                                                                
                                                                                
                                                                                
                                                                                
                                                                                
                                                        
BR Coef=-1 , 0 , 0 ,, 0 ,,,0.8,0,,0,
WSPro=,,,, 1 ,,,, 0 ,,,, 0 ,,,,-1 ,-1 ,-1 , 0 , 0 , 0 , 0 , 0
BR U #Sta/Elev= 30
       0  164.93   92.12  161.74  138.18  158.57  191.92  157.28  246.55  153.23
  268.58  152.68  283.27  151.08  312.65  144.18  327.35  143.08   359.3  138.25
  369.78  138.49   384.5  135.83  413.93  136.98  421.29  136.34  436.65  133.66
  451.18   129.7  494.75  129.03  509.27  129.78  510.43  130.96  545.58  135.56
  583.07  138.06  597.27  137.64  618.56  138.83  639.85  137.52   747.1  138.58
  808.14  138.07 1025.26  141.21 1229.44  147.62 1363.21  153.63 1436.61  160.66
BR U #Mann= 4
       0     .06   359.3     .07  421.29    .033  545.58     .07
BR D #Sta/Elev= 30
       0  165.08    99.8     162  184.24  155.76  243.07  152.76  293.01  151.28
   345.9  148.85  406.75  144.62  436.19  140.98  452.75  137.56  471.44  131.73
  474.53  129.87   481.8  129.06  489.06  129.95  496.32  129.07  510.84  129.04
  521.44  129.62  539.89   135.5  547.15  137.01  660.75  138.14  674.94  139.16
  698.59   138.3  873.27  139.78  951.56  141.66  980.54  143.38 1036.87  143.67
  1128.4  146.45 1219.93  147.56 1269.21  150.61 1374.82  154.06 1457.75  158.71
BR D #Mann= 4
       0     .06  293.01     .07  452.75    .033  547.15     .07
BC Design=,, 0 ,, 0 ,,,,,,
BC Use User HTab Curves=0
BC User HTab FreeFlow(D)= 0

Type RM Length L Ch R = 1 ,58748   ,51.74,46.48,25.87
BEGIN DESCRIPTION:
Modified under water portion by 1 foot as per "flow depth" in bridge inspection notes.
END DESCRIPTION:
XS GIS Cut Line= 6
 1642727.1259539742654.936133862 1642518.8782704742561.186039448
1642312.11251345742494.9686634391642193.53706795742462.258195698
1641802.29516442742389.6840616021641313.84662798742336.856471553
#Sta/Elev= 30
       0  165.08    99.8     162  184.24  155.76  243.07  152.76  293.01  151.28
   345.9  148.85  406.75  144.62  436.19  140.98  452.75  137.56  471.44  131.73
  474.53  129.87   481.8  129.06  489.06  129.95  496.32  129.07  510.84  129.04
  521.44  129.62  539.89   135.5  547.15  137.01  660.75  138.14  674.94  139.16
  698.59   138.3  873.27  139.78  951.56  141.66  980.54  143.38 1036.87  143.67
  1128.4  146.45 1219.93  147.56 1269.21  150.61 1374.82  154.06 1457.75  158.71
#Mann= 4 ,-1 , 0
       0     .06       0  293.01     .07       0  452.75    .035       0
  547.15     .07       0
#XS Ineff= 2 , 0
       0     420   140.8               0
Permanent Ineff=
       F       F
Bank Sta=452.75,547.15
XS Rating Curve= 0 ,0
Exp/Cntr=0.5,0.3

Type RM Length L Ch R = 1 ,58701   ,89.19,86.14,90.6
XS GIS Cut Line= 3
1642757.39959709742562.5681142961642309.15662591742441.205977708
1641252.52601749 742293.42726256
#Sta/Elev= 30
       0  182.84   94.28  172.97  108.78  170.18  130.54  163.64  145.04   160.4
  203.06  154.49  224.95  153.87  282.83  150.21  377.11  147.01  398.86  143.69
  449.63  138.57  456.88  137.22  471.45  131.75  478.52  130.18  492.65  129.89
     528  130.62  542.13  135.24  556.27  137.23  662.29  136.63  867.26  138.97
 1142.92  145.47 1157.06  144.96 1185.33  147.18 1241.87  149.36 1277.22  148.43
 1326.69  152.96 1362.03   152.5 1390.31  153.86 1425.65  158.01 1531.29  164.05
#Mann= 4 ,-1 , 0
       0      .1       0  224.95     .07       0  449.63     .04       0
  556.27     .07       0
Bank Sta=456.88,556.27
XS Rating Curve= 0 ,0
Exp/Cntr=0.5,0.3

Type RM Length L Ch R = 1 ,58615   ,155.53,155.63,162
XS GIS Cut Line= 3
1642839.53542088742429.7883327161642004.80245581742311.665743306
1641282.88771665742201.409674048
#Sta/Elev= 30
       0  190.26   35.35  185.14  127.26  174.75  197.95  164.73  226.23  159.74
     304  150.65  332.28   146.4  452.46  141.02  494.88  136.08  524.71  130.71
  530.23  125.33  544.37  125.04  558.51  125.25  565.58  130.54  600.93  135.75
  913.86  138.35 1090.89  142.98 1105.05  144.33  1126.3  154.21 1147.54  162.01
  1161.7  166.07 1168.78  166.59 1218.35  163.05 1253.76  157.26 1282.08   155.4
 1296.25   152.8 1331.65  152.87 1430.79  158.87 1529.92  169.78 1573.34  173.52
#Mann= 3 , 0 , 0
       0     .07       0  494.88     .04       0  600.93     .07       0
#XS Ineff= 2 ,-1
       0     388  165.57     693 1573.34  159.89
Permanent Ineff=
       F       F
Bank Sta=494.88,600.93
XS Rating Curve= 0 ,0
Exp/Cntr=0.5,0.3

Type RM Length L Ch R = 3 ,58533   ,,,
BEGIN DESCRIPTION:
Hwy 273 Bridge - Approximate Reach  Top of road from LIDAR.  Channel invert lowered 5' on upstream and downstream sections.    There appears to be piers at the low flow bank elevations.  Piers appear to be relatively thick.  MDE Bridge inspection report indicates 3' railing, and 5' deck thickness.
END DESCRIPTION:
Bridge Culvert--1,0,-1,-1, 0
Deck Dist Width WeirC Skew NumUp NumDn MinLoCord MaxHiCord MaxSubmerge Is_Ogee
65,34,2.6,0, 60, 60, , , 0.95, 0, 0,0,,
       0    7.07   28.28   49.49   84.84   98.98  120.19  183.81  197.95  219.16
   233.3  247.44     304  318.14  339.35  353.49  367.63  395.91  410.04  431.25
  438.32     460 460.001     462     627     630 630.001  657.49  671.63  728.18
  742.32  791.81  834.23  849.72  878.04  899.29  934.69  948.86  984.26 1005.51
 1019.67 1033.83 1055.07 1104.64 1125.89 1147.13 1161.29 1189.62 1267.51 1288.75
    1310 1317.08 1352.48 1373.73 1430.38  1458.7 1515.35 1529.51 1536.59 1573.34
  192.96  192.59  190.96  189.68  187.16  186.43  184.75  180.76  179.59  178.44
  177.36  176.62  172.79  172.25  170.91  170.37  169.39  168.16  167.24  166.13
  165.57   165.6   168.6   168.5   163.5  163.33  160.33  160.19   159.9  159.91
  159.68  159.92  160.29  160.57  160.71  161.29  161.87  162.48  163.26  164.11
   164.5  165.19  165.82  167.89  169.08  170.02     171  172.29  177.04   178.5
  179.57   180.2  182.39  183.99  187.49  189.54  193.05  194.15   194.5  196.93
                                                                                
                                                                                
                           160.5   155.5
                                                                                
                                                                                
                                                                                
       0    7.07   28.28   49.49   84.84   98.98  120.19  183.81  197.95  219.16
   233.3  247.44     304  318.14  339.35  353.49  367.63  395.91  410.04  431.25
  438.32     460 460.001     462     627     630 630.001  657.49  671.63  728.18
  742.32  791.81  834.23  849.72  878.04  899.29  934.69  948.86  984.26 1005.51
 1019.67 1033.83 1055.07 1104.64 1125.89 1147.13 1161.29 1189.62 1267.51 1288.75
    1310 1317.08 1352.48 1373.73 1430.38  1458.7 1515.35 1529.51 1536.59 1572.51
  192.96  192.59  190.96  189.68  187.16  186.43  184.75  180.76  179.59  178.44
  177.36  176.62  172.79  172.25  170.91  170.37  169.39  168.16  167.24  166.13
  165.57   165.6   168.6   168.5   163.5  163.33  160.33  160.19   159.9  159.91
  159.68  159.92  160.29  160.57  160.71  161.29  161.87  162.48  163.26  164.11
   164.5  165.19  165.82  167.89  169.08  170.02     171  172.29  177.04   178.5
  179.57   180.2  182.39  183.99  187.49  189.54  193.05  194.15   194.5  196.93
                                                                                
                                                                                
                           160.5   155.5
                                                                                
                                                                                
                                                                                
Pier Skew, UpSta & Num, DnSta & Num=  ,510, 2 ,510, 2 , 0 , 0 , 0 ,,
       5       5
       0     505
       5       5
       0     505
Pier Skew, UpSta & Num, DnSta & Num=  ,580, 2 ,580, 2 , 0 , 0 , 0 ,,
       5       5
       0     505
       5       5
       0     505
BR Coef=-1 , 1 , 0 ,, 0 ,,,0.8,-1,1.2,0,
WSPro=,,,, 1 ,,,, 0 ,,,, 0 ,,,,-1 ,-1 ,-1 , 0 , 0 , 0 , 0 , 0
BR U #Sta/Elev= 30
       0  190.26   35.35  185.14  127.26  174.75  197.95  164.73  226.23  159.74
     304  150.65  332.28   146.4  452.46  141.02  494.88  136.08  524.71  130.71
  530.23  125.33  544.37  125.04  558.51  125.25  565.58  130.54  600.93  135.75
  913.86  138.35 1090.89  142.98 1105.05  144.33  1126.3  154.21 1147.54  162.01
  1161.7  166.07 1168.78  166.59 1218.35  163.05 1253.76  157.26 1282.08   155.4
 1296.25   152.8 1331.65  152.87 1430.79  158.87 1529.92  169.78 1573.34  173.52
BR U #Mann= 3
       0     .07  494.88    .035  600.93     .07
BR D #Sta/Elev= 30
       0  194.68   63.63  184.53  205.02  157.55  254.51  151.77   374.7  144.46
  445.39  141.91  487.81     137  510.78  132.02  516.09   126.4  523.16  126.37
  544.37  126.63  551.44  131.77  565.58  131.91  600.93  136.48  636.28  138.27
  685.76  136.95  898.85  139.08 1054.63  142.56 1075.88  144.53 1175.01  147.97
 1259.99   154.1 1295.39  154.75 1309.56  156.67 1352.04  158.12 1415.77  164.09
 1437.02  163.23 1451.18  164.36 1472.42  170.25 1493.67  173.44 1571.63  191.08
BR D #Mann= 3
       0      .1  487.81    .035  600.93     .07
BC Design=,, 0 ,, 0 ,,,,,,
BC Use User HTab Curves=0
BC User HTab FreeFlow(D)= 0

Type RM Length L Ch R = 1 ,58459   ,80.54,81.27,88.45
XS GIS Cut Line= 3
1642861.25301445742276.3173382881642027.36261991742158.313980564
1641306.28909138742048.186387122
#Sta/Elev= 30
       0  194.68   63.63  184.53  205.02  157.55  254.51  151.77   374.7  144.46
  445.39  141.91  487.81     137  510.78  132.02  516.09   126.4  523.16  126.37
  544.37  126.63  551.44  131.77  565.58  131.91  600.93  136.48  636.28  138.27
  685.76  136.95  898.85  139.08 1054.63  142.56 1075.88  144.53 1175.01  147.97
 1259.99   154.1 1295.39  154.75 1309.56  156.67 1352.04  158.12 1415.77  164.09
 1437.02  163.23 1451.18  164.36 1472.42  170.25 1493.67  173.44 1571.63  191.08
#Mann= 3 , 0 , 0
       0      .1       0  487.81     .04       0  600.93     .07       0
#XS Ineff= 2 ,-1
       0     388   160.5     693 1571.63   155.5
Permanent Ineff=
       F       F
Bank Sta=487.81,600.93
XS Rating Curve= 0 ,0
Exp/Cntr=0.5,0.3

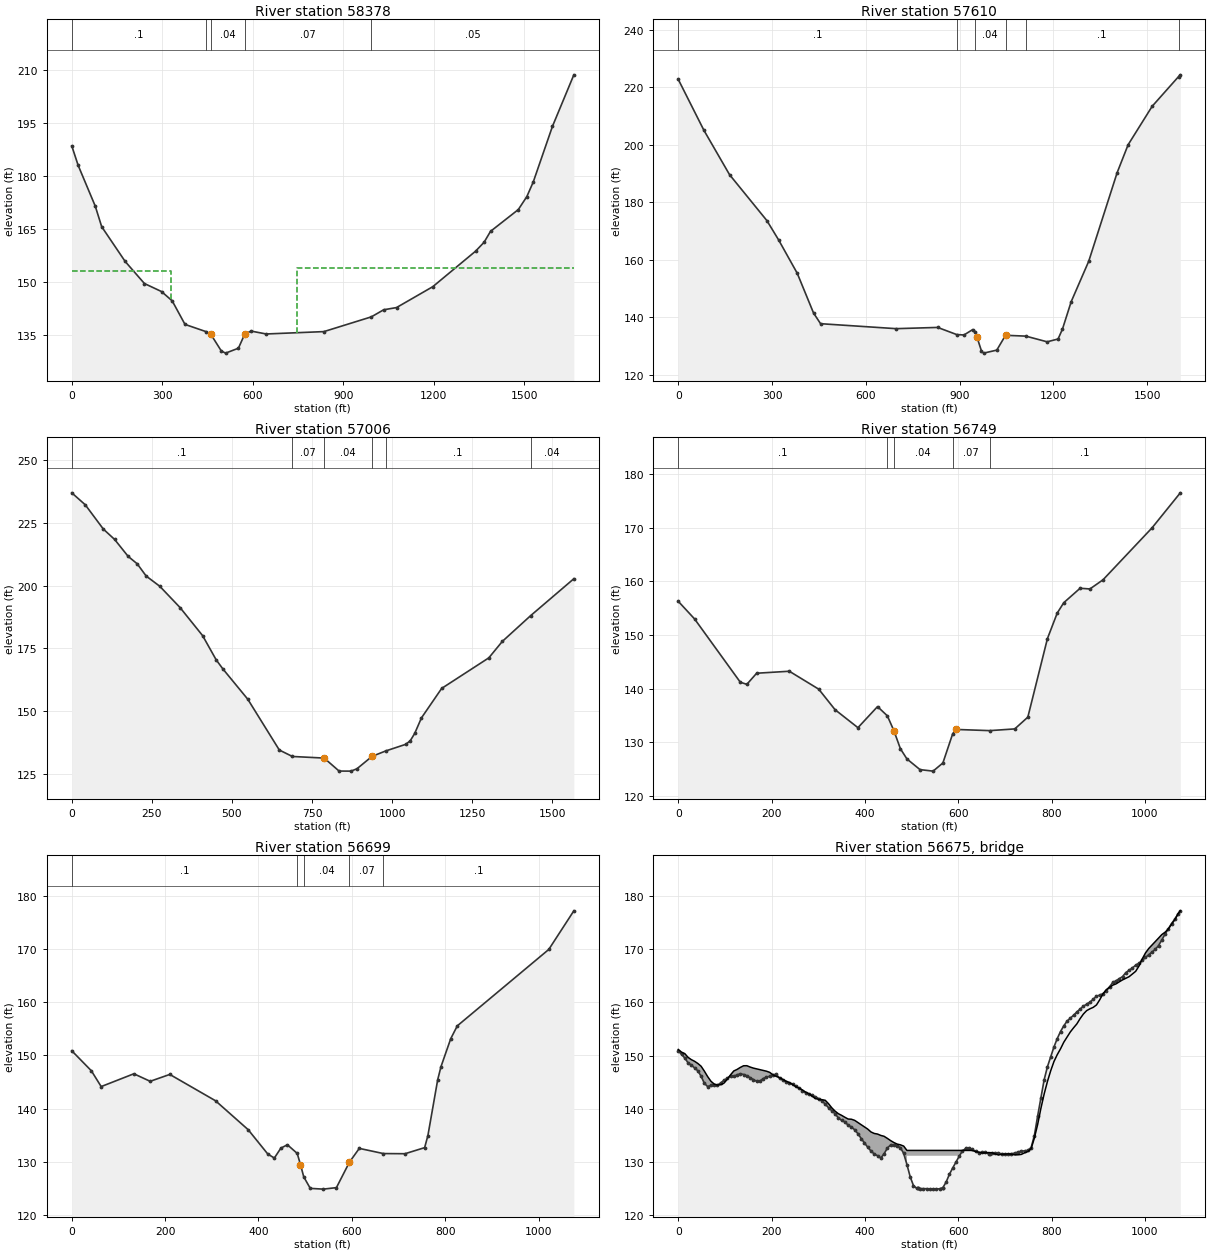
Type RM Length L Ch R = 1 ,58378   ,779.35,768.7,763.35
XS GIS Cut Line= 2
1642857.91492699742200.7319762861641212.87736695 741946.23653239
#Sta/Elev= 30
       0  188.49   21.25  182.96   77.92  171.43   99.17  165.62  177.08  155.78
  240.83  149.54   297.5  147.27  332.91  144.64  375.41  137.97  446.25  135.89
  460.41  135.25  495.83  130.45     510  129.84   552.5  131.23  573.75  135.28
  594.99  136.07  644.58  135.26  835.83  135.93   993.1   140.1 1034.16  142.11
 1076.66  142.73 1197.07  148.65 1338.74  158.69 1367.07  161.22 1388.32   164.3
  1480.4  170.46 1508.73  174.13 1529.98  178.27 1593.73  194.03  1664.6   208.6
#Mann= 5 ,-1 , 0
       0      .1       0  446.25     .07       0  460.41     .04       0
  573.75     .07       0   993.1     .05       0
#XS Ineff= 2 ,-1
       0  327.37153.1837  745.55  1664.6153.8067
Permanent Ineff=
       F       F
Bank Sta=460.41,573.75
XS Rating Curve= 0 ,0
Exp/Cntr=0.3,0.1

Type RM Length L Ch R = 1 ,57610   ,522.18,603.65,617.63
XS GIS Cut Line= 3
1643361.96398118 741577.926168711642780.56273268741363.190895438
1641794.65996578741347.912268832
#Sta/Elev= 30
       0  222.83   82.08  205.09  164.17  189.62  283.56  173.63  320.87  166.94
  380.57   155.3  432.81  141.44  455.19  137.73   696.8     136  829.81  136.43
  890.74  133.94  913.82   133.8  941.83  135.68  948.83  134.99  955.83  132.95
  969.83  128.22  976.83  127.48 1018.84  128.53 1046.84  133.69  1111.7   133.4
 1179.86  131.42 1214.86   132.4 1228.86  135.84 1256.87  145.42 1312.87  159.47
 1403.88  190.36 1438.89  200.05  1515.9  213.46 1600.35   223.8 1605.81   224.4
#Mann= 6 ,-1 , 0
       0      .1       0  890.74     .07       0  948.83     .04       0
 1046.84     .07       0  1111.7      .1       0 1600.35     .04       0
Bank Sta=955.83,1046.84
XS Rating Curve= 0 ,0
Exp/Cntr=0.3,0.1

Type RM Length L Ch R = 1 ,57006   ,303.15,256.6,195.42
XS GIS Cut Line= 4
1643307.96475698740927.4097543951642543.30457836 740844.12993294
 1642422.1702926740738.1374329181641786.21529257740772.206450775
#Sta/Elev= 30
       0  236.91   42.25  232.13   98.58  222.48  133.79  218.36  176.03  211.62
   204.2  208.68  232.37  203.79  274.61  199.75  337.99  191.27   408.4   180.1
  450.65  170.49  471.77  166.84  549.23  154.83  647.81   134.6  688.54  132.04
  787.78   131.4  834.29  126.24   871.5  126.21   890.1  127.15  937.15  132.08
  980.16  134.25  1042.3  136.87 1056.32  138.27 1070.34  141.21 1091.37  147.39
 1154.46  159.11 1301.67  171.27 1343.73   177.8 1431.93  188.03 1567.01  202.74
#Mann= 6 ,-1 , 0
       0      .1       0  688.54     .07       0  787.78     .04       0
  937.15     .07       0  980.16      .1       0 1431.93     .04       0
Bank Sta=787.78,937.15
XS Rating Curve= 0 ,0
Exp/Cntr=0.3,0.1

Type RM Length L Ch R = 1 ,56749   ,50.07,50.75,50.38
XS GIS Cut Line= 2
1643100.00143634740550.9832006991642024.31865975740548.549529254
#Sta/Elev= 30
       0  156.28      35  152.99     133  141.19     147   140.8     168  142.87
     238  143.24     301   139.9     336  136.07     385  132.72     427  136.65
     448  134.93     462  132.17     476  128.79     490  126.89     518   124.9
     546  124.62     567  126.14     588  131.58     595  132.39  667.46  132.17
     721  132.49     749  134.68     791  149.33     812  154.09     826  156.02
     861  158.71     882  158.58     910  160.28    1015  169.96 1075.68   176.5
#Mann= 5 ,-1 , 0
       0      .1       0     448     .07       0     462     .04       0
     588     .07       0  667.46      .1       0
Bank Sta=462,595
XS Rating Curve= 0 ,0
Exp/Cntr=0.5,0.3

Type RM Length L Ch R = 1 ,56699   ,40.82,42.2,40.19
XS GIS Cut Line= 2
1643100.11455821740500.9833286851642024.43178162740498.549657226
#Sta/Elev= 30
       0  150.89      42  147.13      63  144.17     133  146.57     168  145.16
     210  146.45     308  141.51     378  136.08     420  131.52     434  130.77
     448  132.63     462  133.26     483  131.64     490  129.54     497  127.24
     511  125.08     539  124.94     567  125.22     595  130.01     616  132.58
  667.57  131.61     714  131.58     756  132.72     763  134.99     784  145.46
     791   147.9     812  153.17     826  155.56    1022  169.89 1075.68  177.13
#Mann= 5 ,-1 , 0
       0      .1       0     483     .07       0     497     .04       0
     595     .07       0  667.57      .1       0
#XS Ineff= 2 , 0
       0     470   132.2     620       0   131.5
Permanent Ineff=
       F       F
Bank Sta=490,595
XS Rating Curve= 0 ,0
Exp/Cntr=0.5,0.3

Type RM Length L Ch R = 3 ,56675   ,,,
BEGIN DESCRIPTION:
Ped Bridge - No survey info.  Assumed elevation based on lidar bank elevation.  Assumed 1' deck thickness.
END DESCRIPTION:
Bridge Culvert--1,0,-1,-1, 0
Deck Dist Width WeirC Skew NumUp NumDn MinLoCord MaxHiCord MaxSubmerge Is_Ogee
20,8,2.6,0, 136, 136, , , 0.95, 0, 0,0,,
       0       7      14      21      28      35      42      49      56      63
      70      77      84      91      98     105     112     119     126     133
     140     147     154     161     168     175     182     189     196     203
     210     217     224     231     238     245     252     259     266     273
     280     287     294     301     308     315     322     329     336     343
     350     357     364     371     378     385     392     399     406     413
     420     427     434     441     448     455     462     469     476     483
     490     630     637     644     651     658     665     672     679     686
     693     700     707     714     721     728     735     742     749     756
     763     770     777     784     791     798     805     812     819     826
     833     840     847     854     861     868     875     882     889     896
     903     910     917     924     931     938     945     952     959     966
     973     980     987     994    1001    1008    1015    1022    1029    1036
    1043    1050    1057    1064    1071 1075.68
  151.14  150.64  150.36  149.66  149.23  148.92  148.51  147.99  147.07  146.05
  145.18  144.65  144.46  144.53  144.82  145.56  146.37   147.1  147.39  147.77
  148.08  148.09  147.84  147.64  147.49  147.32  147.19  147.06  146.84  146.38
  146.08  145.85  145.51  145.18  144.93  144.56  144.16  143.88  143.53  143.14
  142.83  142.38  141.94  141.77  141.72   141.6  140.96  140.19  139.57  139.09
  138.78  138.42  138.09  138.05  137.84  137.43  137.01  136.63   136.2  135.66
  135.38  135.27  135.01  134.85  134.46  134.04  133.68  133.39  133.25  133.01
   132.2   132.2  131.99  131.87  131.72  131.74   131.8  131.76  131.55  131.35
  131.49   131.5  131.55  131.49  131.37  131.38  131.45  131.75     132  132.51
  134.52  137.06  140.09   142.8  145.13  147.14  148.88  150.16  151.25  152.49
  153.47  154.42   155.2  155.93  156.92  157.78  158.42  158.76  159.03  159.48
  160.45  161.56  162.35   162.8   163.2  163.44  163.83  164.19   164.5  164.79
  165.29  165.79  166.77   168.1  169.23  170.07  170.71  171.32  172.02  172.68
  173.13  173.72  174.65  175.48   176.6  177.14
                                                                                
                                                                                
                                                                                
                                                                                
                                                                                
                                                                                
                                                                                
   131.2   131.2
                                                                                
                                                                                
                                                                                
                                                                                
                                                                                
                                                
       0       7      14      21      28      35      42      49      56      63
      70      77      84      91      98     105     112     119     126     133
     140     147     154     161     168     175     182     189     196     203
     210     217     224     231     238     245     252     259     266     273
     280     287     294     301     308     315     322     329     336     343
     350     357     364     371     378     385     392     399     406     413
     420     427     434     441     448     455     462     469     476     483
     490     630     637     644     651     658     665     672     679     686
     693     700     707     714     721     728     735     742     749     756
     763     770     777     784     791     798     805     812     819     826
     833     840     847     854     861     868     875     882     889     896
     903     910     917     924     931     938     945     952     959     966
     973     980     987     994    1001    1008    1015    1022    1029    1036
    1043    1050    1057    1064    1071 1075.68
  151.14  150.64  150.36  149.66  149.23  148.92  148.51  147.99  147.07  146.05
  145.18  144.65  144.46  144.53  144.82  145.56  146.37   147.1  147.39  147.77
  148.08  148.09  147.84  147.64  147.49  147.32  147.19  147.06  146.84  146.38
  146.08  145.85  145.51  145.18  144.93  144.56  144.16  143.88  143.53  143.14
  142.83  142.38  141.94  141.77  141.72   141.6  140.96  140.19  139.57  139.09
  138.78  138.42  138.09  138.05  137.84  137.43  137.01  136.63   136.2  135.66
  135.38  135.27  135.01  134.85  134.46  134.04  133.68  133.39  133.25  133.01
   132.2   132.2  131.99  131.87  131.72  131.74   131.8  131.76  131.55  131.35
  131.49   131.5  131.55  131.49  131.37  131.38  131.45  131.75     132  132.51
  134.52  137.06  140.09   142.8  145.13  147.14  148.88  150.16  151.25  152.49
  153.47  154.42   155.2  155.93  156.92  157.78  158.42  158.76  159.03  159.48
  160.45  161.56  162.35   162.8   163.2  163.44  163.83  164.19   164.5  164.79
  165.29  165.79  166.77   168.1  169.23  170.07  170.71  171.32  172.02  172.68
  173.13  173.72  174.65  175.48   176.6  177.14
                                                                                
                                                                                
                                                                                
                                                                                
                                                                                
                                                                                
                                                                                
   131.2   131.2
                                                                                
                                                                                
                                                                                
                                                                                
                                                                                
                                                
BR Coef=-1 , 0 , 0 ,, 0 ,,,0.8,0,,0,
WSPro=,,,, 1 ,,,, 0 ,,,, 0 ,,,,-1 ,-1 ,-1 , 0 , 0 , 0 , 0 , 0
BR U #Sta/Elev= 159
       0  150.89       7  150.22      14  149.54      21  148.63      28  148.19
      35  147.69      42  147.13      49  146.11      56  144.78      63  144.17
      70  144.39      77   144.5      84  144.44      91  144.86      98  145.36
     105  145.72     112  146.15     119  146.07     126  146.36     133  146.57
     140  146.44     147   146.2     154  145.83     161  145.49     168  145.16
     175   145.2     182  145.66     189  145.97     196  146.09     203  146.39
     210  146.45     217  145.74     224   145.4     231   145.1     238  144.85
     245  144.67     252  144.21     259   143.9     266  143.42     273  142.99
     280  142.74     287  142.52     294  142.25     301  141.92     308  141.51
     315  140.86     322  140.22     329  139.65     336  139.07     343  138.31
     350  137.84     357  137.53     364  136.94     371  136.56     378  136.08
     385  135.33     392  134.43     399  133.59     406   132.8     413  132.08
     420  131.52     427  131.21     434  130.77     441  131.56     448  132.63
     455  133.22     462  133.26     469  133.06     476  132.71     483  131.64
     490  129.54     497  127.24     504   125.6     511  125.08   513.1  125.07
  513.96  125.06     518  125.04     525  125.02     532  125.02     539  124.94
     546  124.99     553  124.96     560     125  566.67  125.21     567  125.22
     574  126.27     581  127.73     588   128.9     595  130.01     602  131.11
     609  132.11     616  132.58     623  132.62     630  132.38     637  132.01
     644  131.76     651  131.83     658  131.82     665  131.56  667.57  131.61
     672  131.72     679  131.76     686  131.65     693  131.58     700  131.54
     707  131.52     714  131.58     721  131.69     728  131.89     735  132.07
     742  132.12     749   132.2     756  132.72     763  134.99     770  138.64
     777  142.09     784  145.46     791   147.9     798  149.75     805  151.61
     812  153.17     819   154.5     826  155.56     833  156.44     840     157
     847  157.56     854  158.17     861  158.71     868  159.24     875  159.64
     882  160.01     889  160.55     896  161.12     903  161.33     910  161.59
     917   162.1     924  162.87     931   163.7     938  164.01     945  164.41
     952  164.81     959  165.56     966     166     973  166.42     980  166.94
     987   167.3     994  167.84    1001   168.4    1008   168.9    1015  169.39
    1022  169.89    1029  170.62    1036  171.65    1043  172.77    1050  173.76
    1057  174.76    1064   175.6    1071  176.59 1075.68  177.13
BR U #Mann= 5
       0      .1   513.1     .07  513.96    .035  566.67     .07  667.57      .1
BR D #Sta/Elev= 159
       0   151.7       7  151.08      14  150.51      21   150.2      28  149.98
      35  149.75      42  149.48      49  149.12      56  148.69      63  148.34
      70  147.64      77   146.5      84   145.7      91  145.47      98  145.42
     105  145.33     112  145.77     119  146.38     126  146.65     133     147
     140  147.41     147  147.95     154  148.27     161  148.21     168  147.97
     175  147.74     182  147.54     189  147.48     196  147.24     203  146.98
     210  146.56     217  146.16     224  145.79     231  145.33     238  145.07
     245  144.82     252  144.48     259  144.22     266  143.99     273  143.72
     280  143.32     287  142.85     294  142.39     301  142.07     308  141.74
     315  141.45     322  141.17     329  141.09     336  140.91     343  140.84
     350  140.86     357   140.5     364  139.89     371  139.55     378  139.43
     385  139.35     392  139.46     399  139.57     406  139.39     413  139.05
     420  138.74     427  138.47     434  138.44     441  138.07     448  137.49
     455  137.08     462  136.63     469  136.01     476  135.04     483  133.64
     490  132.36     497  130.71     504  128.48     511  126.44     518  125.29
  518.91  125.25     525  125.03  527.41  125.01     532  124.96     539  124.91
     546  124.93     553  124.87     560  124.79     567  124.83     574  124.94
  580.12  125.01     581  125.02     588  125.21     595  126.35     602  128.59
     609   130.7     616  132.06     623  132.54     630  132.61     637  132.65
     644  132.23     651  131.95     658  131.44     665  131.53     672  131.52
   672.3  131.51     679  131.28     686  131.21     693   131.2     700  131.21
     707  131.24     714  131.48     721  131.65     728  131.78     735     132
     742  132.55     749  133.27     756  134.14     763  135.37     770  136.82
     777  138.35     784  140.05     791  141.66     798  143.28     805     145
     812  146.68     819  147.97     826  149.15     833   150.5     840  151.79
     847  153.18     854  154.33     861  155.16     868  156.14     875  157.41
     882  158.12     889  158.81     896  159.71     903  160.62     910  161.26
     917  161.89     924  162.59     931  163.32     938  164.22     945  164.94
     952  165.47     959  166.06     966  166.59     973  167.27     980  168.14
     987  168.82     994  169.54    1001  170.18    1008  170.61    1015  171.08
    1022  172.03    1029  173.04    1036  173.84    1043  174.55    1050  175.16
    1057  175.75    1064  176.37    1071   177.3 1075.68  178.01
BR D #Mann= 5
       0      .1  518.91     .07  527.41    .035  580.12     .07   672.3      .1
BC Design=,, 0 ,, 0 ,,,,,,
BC Use User HTab Curves=0
BC User HTab FreeFlow(D)= 0

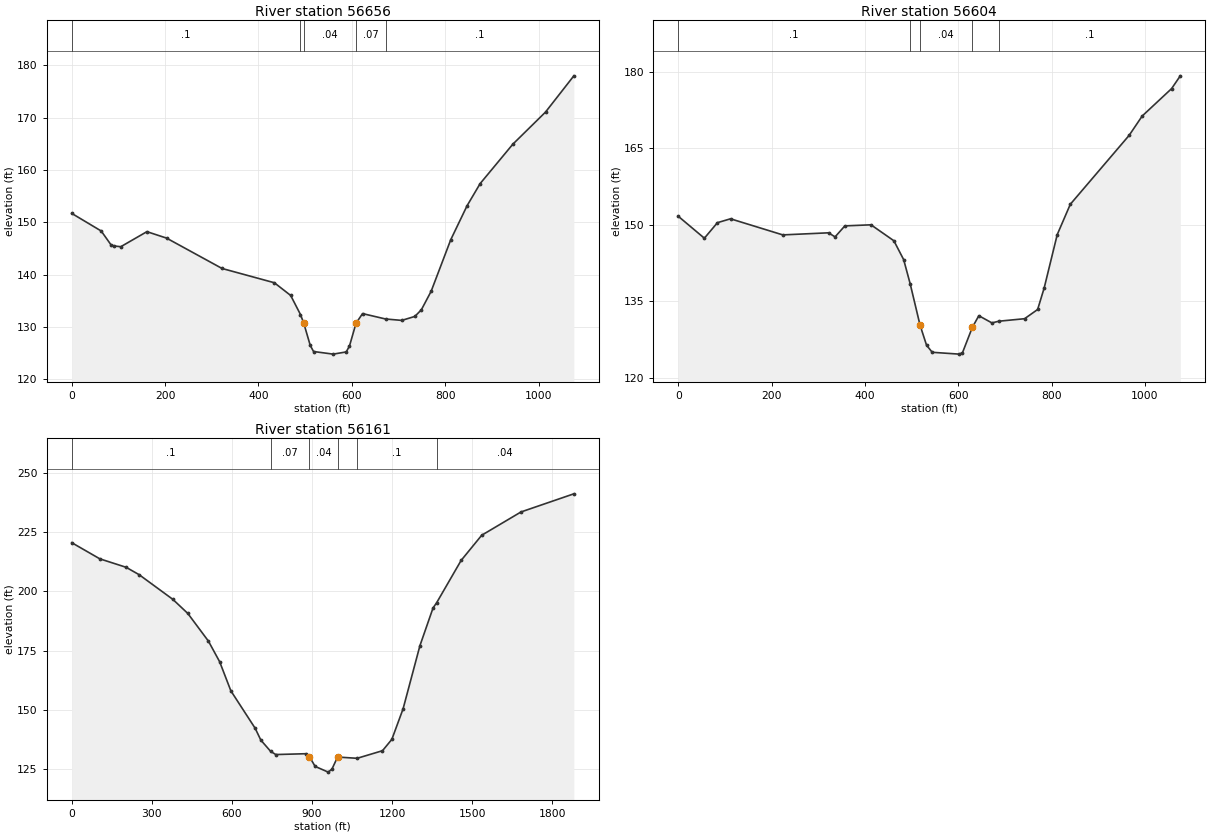
Type RM Length L Ch R = 1 ,56656   ,51.53,52.74,50.03
XS GIS Cut Line= 2
1643100.20505573740460.9834310561642024.52227914740458.549759611
#Sta/Elev= 30
       0   151.7      63  148.34      84   145.7      91  145.47     105  145.33
     161  148.21     203  146.98     322  141.17     434  138.44     469  136.01
     490  132.36     497  130.71     511  126.44     518  125.29     560  124.79
     588  125.21     595  126.35     609   130.7     623  132.54   672.3  131.51
     707  131.24     735     132     749  133.27     770  136.82     812  146.68
     847  153.18     875  157.41     945  164.94    1015  171.08 1075.68  178.01
#Mann= 5 ,-1 , 0
       0      .1       0     490     .07       0     497     .04       0
     609     .07       0   672.3      .1       0
#XS Ineff= 2 , 0
       0     470   131.2     631       0   131.2
Permanent Ineff=
       F       F
Bank Sta=497,609
XS Rating Curve= 0 ,0
Exp/Cntr=0.5,0.3

Type RM Length L Ch R = 1 ,56604   ,444.38,442.18,425.71
XS GIS Cut Line= 2
 1643100.3181776740410.9835590121642024.63540101740408.549887583
#Sta/Elev= 30
       0  151.69      56  147.38      84  150.43     112  151.19     224  148.03
     322  148.44     336  147.64     357   149.8     413  150.01     462  146.88
     483  143.17     497  138.41     518  130.34     532  126.38  544.19  124.99
     602  124.63     609  124.91     630  129.86     644  132.17     672  130.76
  686.93  131.09     742  131.58     770  133.39     784  137.61     812  148.09
     840  154.04     966  167.56     994  171.36    1057  176.74 1075.68  179.25
#Mann= 5 ,-1 , 0
       0      .1       0     497     .07       0     518     .04       0
     630     .07       0  686.93      .1       0
Bank Sta=518,630
XS Rating Curve= 0 ,0
Exp/Cntr=0.3,0.1

Type RM Length L Ch R = 1 ,56161   ,646.45,661.78,636.4
XS GIS Cut Line= 2
1643378.01146261739919.6864254181641500.45614035740037.367955595
#Sta/Elev= 30
       0  220.49  105.21  213.68   203.4  210.13  252.49     207  378.74   196.6
  434.85  190.66     512     179  554.08  170.31  596.17  158.03  687.35  142.22
  708.39  137.27  745.35   132.5   764.5  131.18  876.72  131.53  890.74  130.25
  911.79  126.19  960.88  123.77  974.91  125.05  995.95  130.13  1069.3   129.6
 1164.28   132.8 1199.35  137.59 1241.43  150.46 1304.56  177.09 1353.65  192.97
 1366.91  195.13 1458.86  213.01 1536.01  223.63  1683.3  233.45 1881.25  241.09
#Mann= 6 ,-1 , 0
       0      .1       0  745.35     .07       0  890.74     .04       0
  995.95     .07       0  1069.3      .1       0 1366.91     .04       0
Bank Sta=890.74,995.95
XS Rating Curve= 0 ,0
Exp/Cntr=0.3,0.1