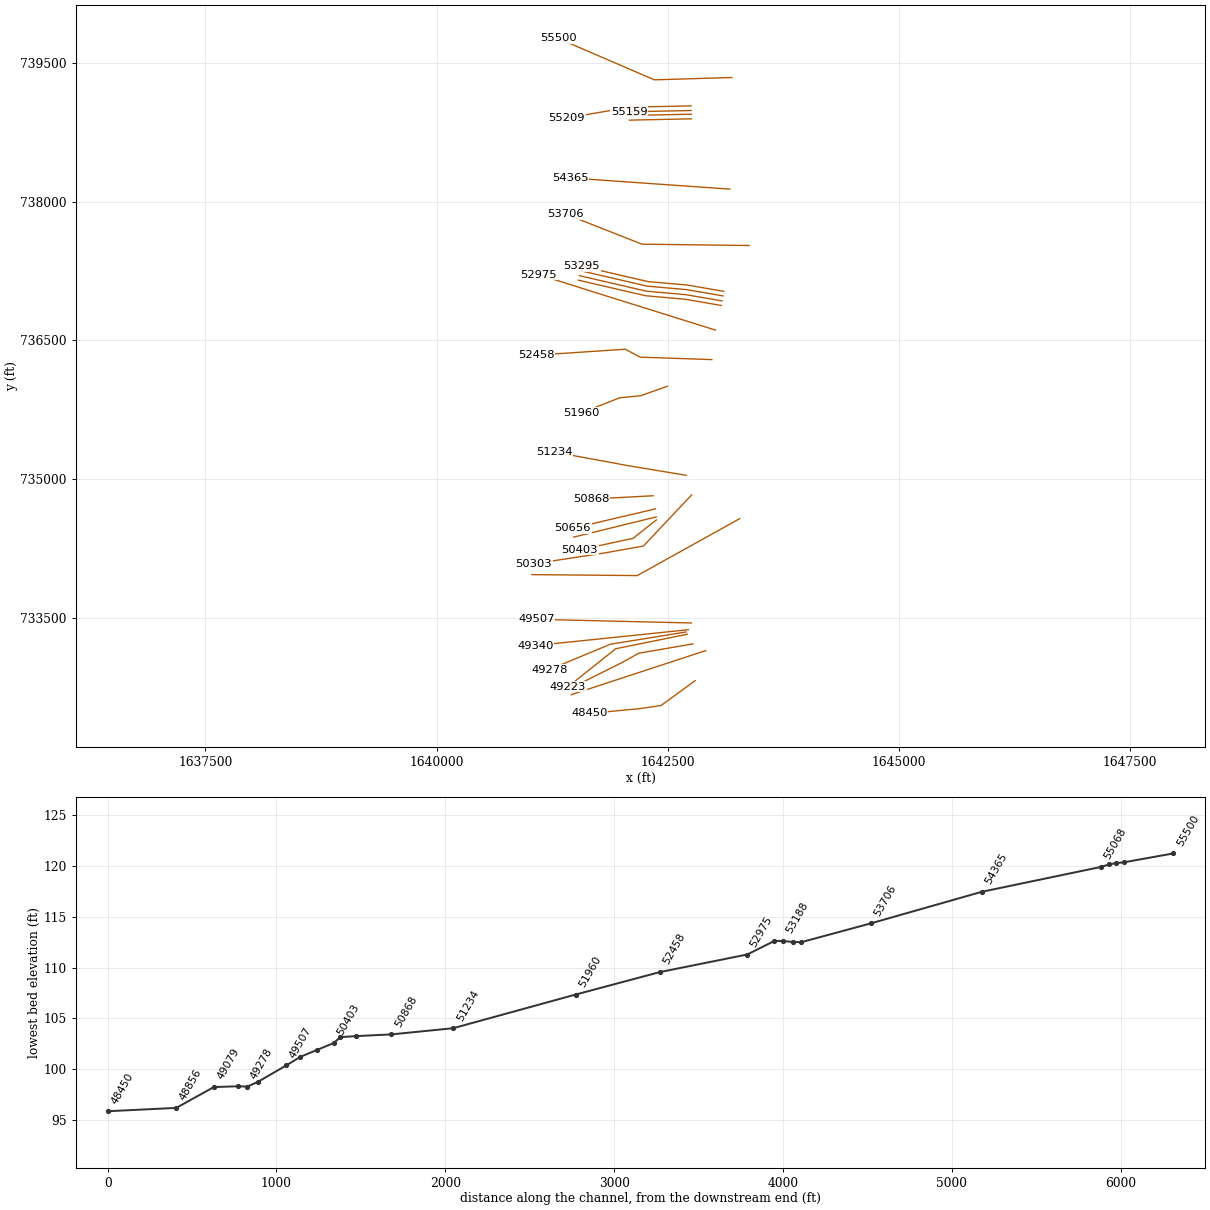
HEC-RAS study bigelkcreek.prj: Big Elk Creek

--- bigelkcreek.g23 (geometry) --- (continued)

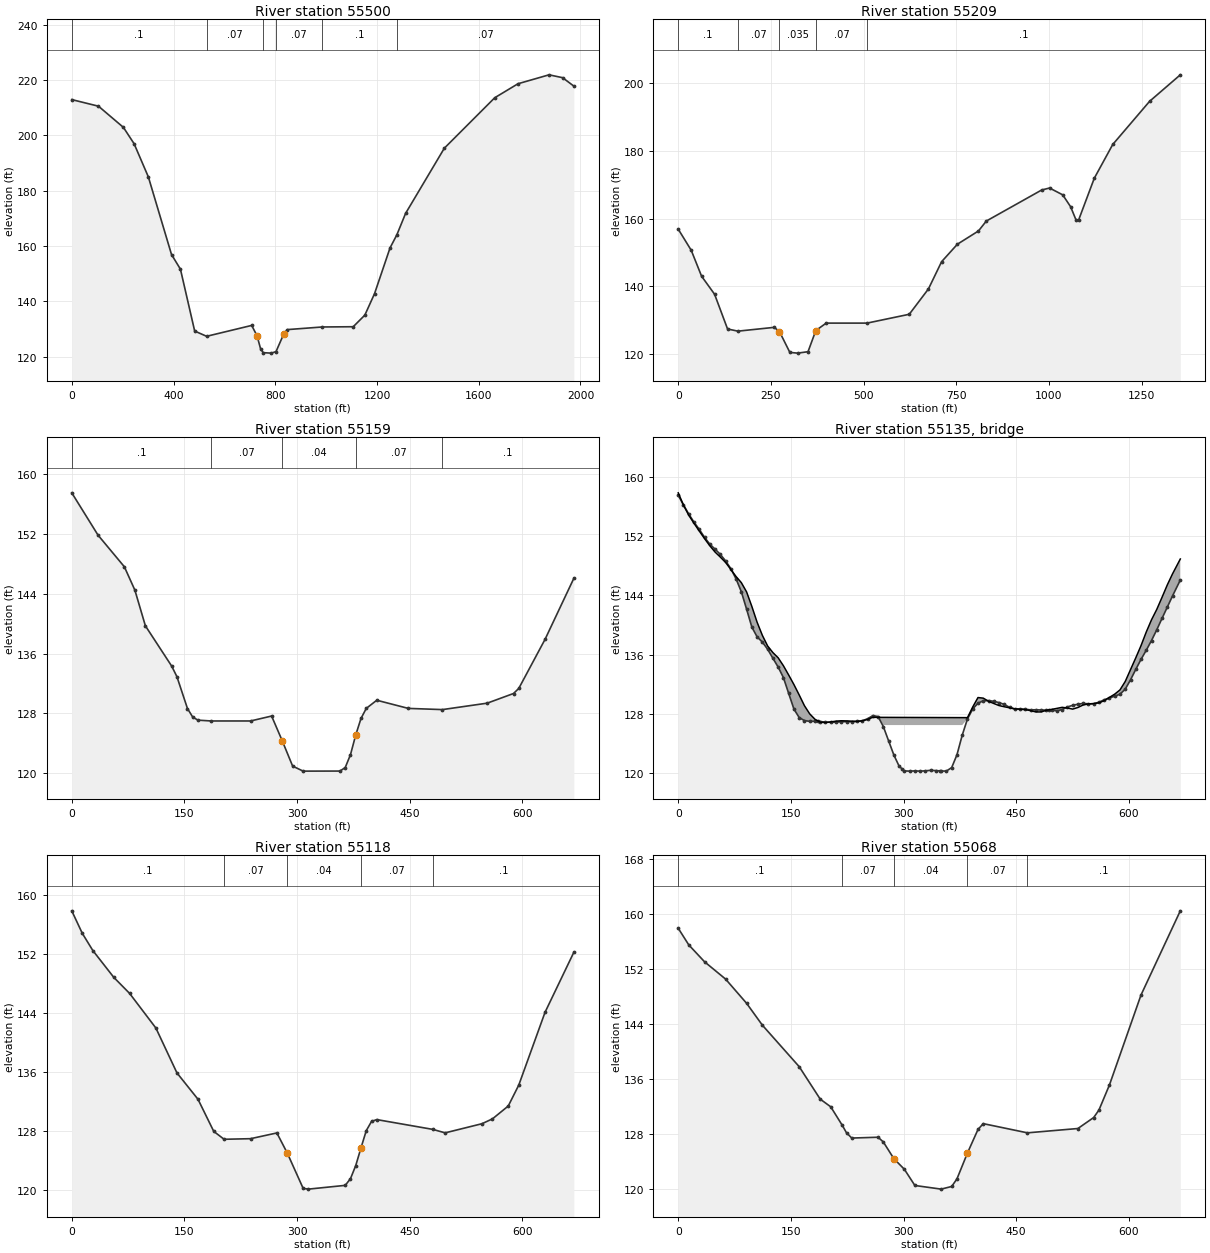
Type RM Length L Ch R = 1 ,55500   ,293.15,290.97,323.24
XS GIS Cut Line= 3
1643194.11779568739345.1732286361642354.74834344739320.241462737
1641313.15456776739769.013249055
#Sta/Elev= 30
       0  212.87  105.05  210.48  203.09  202.82  245.11  196.91  301.13  184.92
  392.17  156.87  427.19  151.59  483.21  129.23  530.19  127.33  707.31  131.26
  728.32  127.53  742.33  122.82  752.84  121.41  784.35  121.25  802.98   121.8
  833.37  128.16  847.36  129.75  984.98   130.7 1106.51  130.79 1152.25  134.99
 1190.36  142.75 1251.33  159.29  1278.1  164.01 1312.31  171.73 1464.75  195.31
 1662.92  213.54 1754.39   218.6 1876.34  221.82  1929.7  220.79  1973.9  217.74
#Mann= 6 ,-1 , 0
       0      .1       0  530.19     .07       0  752.84    .035       0
  802.98     .07       0  984.98      .1       0  1278.1     .07       0
Bank Sta=728.32,833.37
XS Rating Curve= 0 ,0
Exp/Cntr=0.3,0.1

Type RM Length L Ch R = 1 ,55209   ,51.3,50.04,50.01
XS GIS Cut Line= 3
1642751.23936932739038.2453541311642090.75324473739024.142447561
1641407.09174921738907.181229949
#Sta/Elev= 30
       0  156.88   35.01  150.67   63.01  143.02   98.02  137.72  133.03  127.49
  161.02  126.85  259.06  127.97  273.06  126.72  301.07  120.59  322.07  120.38
  350.08   120.8  371.08  127.03  399.09  129.22  509.33  129.22  623.14  131.82
  674.84  139.28  710.35   147.3  752.96  152.45  809.77  156.35  831.08  159.28
  980.21  168.41 1001.52     169 1037.03  166.99 1058.33  163.49 1072.53  159.71
 1079.64  159.49 1122.25  171.89 1171.96  181.82 1271.38  194.53 1354.23  202.33
#Mann= 5 ,-1 , 0
       0      .1       0  161.02     .07       0  273.06    .035       0
  371.08     .07       0  509.33      .1       0
Bank Sta=273.06,371.08
XS Rating Curve= 0 ,0
Exp/Cntr=0.5,0.3

Type RM Length L Ch R = 1 ,55159   ,41.04,40.21,40.01
XS GIS Cut Line= 2
1642752.30674165738988.2567482741642083.99903138738973.986832738
#Sta/Elev= 30
       0  157.47   35.01  151.81   70.02  147.59   84.02  144.47   98.02   139.7
  133.03  134.32  140.03   132.9  154.04  128.65  161.04  127.51  168.04   127.1
  185.63  126.99  238.05  126.99  266.06  127.65  280.06  124.38  294.07  120.96
  308.07  120.29  357.08   120.3  364.08  120.77  371.08  122.49  378.09  125.13
  385.09  127.33  392.09  128.67  406.09  129.76   448.1  128.67  493.46  128.51
  553.13  129.37  588.13  130.66  595.14  131.34  630.14   137.9  668.46  146.05
#Mann= 5 ,-1 , 0
       0      .1       0  185.63     .07       0  280.06     .04       0
  378.09     .07       0  493.46      .1       0
#XS Ineff= 2 , 0
       0     248  126.95     400       0   127.5
Permanent Ineff=
       F       F
Bank Sta=280.06,378.09
XS Rating Curve= 0 ,0
Exp/Cntr=0.5,0.3

Type RM Length L Ch R = 3 ,55135   ,,,
BEGIN DESCRIPTION:
Ped Bridge - No survey info.  Assumed elevation based on lidar bank elevation.  Assumed 1' deck thickness.
END DESCRIPTION:
Bridge Culvert--1,0,-1,-1, 0
Deck Dist Width WeirC Skew NumUp NumDn MinLoCord MaxHiCord MaxSubmerge Is_Ogee
20,8,2.6,0, 80, 80, , , 0.95, 0, 0,0,,
       0       7      14      21   28.01   35.01   42.01   49.01   56.01   63.01
   70.02   77.02   84.02   91.02   98.02  105.02  112.03  119.03  126.03  133.03
  140.03  147.03  154.04  161.04  168.04  175.04  182.04  189.04  196.04  203.05
  210.05  217.05  224.05  231.05  238.05  245.06  252.06  259.06  266.06  385.09
  392.09  399.09  406.09  413.09   420.1   427.1   434.1   441.1   448.1   455.1
  462.11  469.11  476.11  483.11  490.11  497.11  504.11  511.12  518.12  525.12
  532.12  539.12  546.12  553.13  560.13  567.13  574.13  581.13  588.13  595.14
  602.14  609.14  616.14  623.14  630.14  637.14  644.15  651.15  658.15  668.46
  157.81  156.14  154.79   153.7  152.66  151.64  150.68  149.83  149.15  148.43
  147.48  146.52   145.7  144.45  142.49  140.36  138.59  137.16  136.27  135.57
   134.5  133.25  131.96  130.56  129.11  128.01  127.28  126.89  126.84  126.92
  127.03  127.08  127.06  127.02     127  127.07  127.26  127.55  127.54   127.5
  128.94  130.21  130.13  129.71  129.41  129.13  128.97  128.83  128.68  128.64
  128.58  128.45  128.27  128.27  128.49  128.61  128.75  128.89   128.8  128.65
  128.87  129.21  129.35   129.4   129.5  129.79  130.23  130.67  131.24  132.38
  133.97  135.56  137.21  139.05   140.7   142.1  143.73   145.4   146.9  148.89
                                                                                
                                                                                
                                                                                
                                                                   126.5   126.5
                                                                                
                                                                                
                                                                                
                                                                                
       0       7      14      21   28.01   35.01   42.01   49.01   56.01   63.01
   70.02   77.02   84.02   91.02   98.02  105.02  112.03  119.03  126.03  133.03
  140.03  147.03  154.04  161.04  168.04  175.04  182.04  189.04  196.04  203.05
  210.05  217.05  224.05  231.05  238.05  245.06  252.06  259.06  266.06  385.09
  392.09  399.09  406.09  413.09   420.1   427.1   434.1   441.1   448.1   455.1
  462.11  469.11  476.11  483.11  490.11  497.11  504.11  511.12  518.12  525.12
  532.12  539.12  546.12  553.13  560.13  567.13  574.13  581.13  588.13  595.14
  602.14  609.14  616.14  623.14  630.14  637.14  644.15  651.15  658.15  668.46
  157.81  156.14  154.79   153.7  152.66  151.64  150.68  149.83  149.15  148.43
  147.48  146.52   145.7  144.45  142.49  140.36  138.59  137.16  136.27  135.57
   134.5  133.25  131.96  130.56  129.11  128.01  127.28  126.89  126.84  126.92
  127.03  127.08  127.06  127.02     127  127.07  127.26  127.55  127.54   127.5
  128.94  130.21  130.13  129.71  129.41  129.13  128.97  128.83  128.68  128.64
  128.58  128.45  128.27  128.27  128.49  128.61  128.75  128.89   128.8  128.65
  128.87  129.21  129.35   129.4   129.5  129.79  130.23  130.67  131.24  132.38
  133.97  135.56  137.21  139.05   140.7   142.1  143.73   145.4   146.9  148.89
                                                                                
                                                                                
                                                                                
                                                                   126.5   126.5
                                                                                
                                                                                
                                                                                
                                                                                
BR Coef=-1 , 0 , 0 ,, 0 ,,,0.8,0,,0,
WSPro=,,,, 1 ,,,, 0 ,,,, 0 ,,,,-1 ,-1 ,-1 , 0 , 0 , 0 , 0 , 0
BR U #Sta/Elev= 100
       0  157.47       7  156.18      14  154.95      21  153.85   28.01  152.88
   35.01  151.81   42.01  150.89   49.01  150.22   56.01  149.51   63.01  148.64
   70.02  147.59   77.02   146.2   84.02  144.47   91.02  142.12   98.02   139.7
  105.02  138.39  112.03  137.68  119.03  136.72  126.03   135.5  133.03  134.32
  140.03   132.9  147.03  130.77  154.04  128.65  161.04  127.51  168.04   127.1
  175.04     127  182.04  127.01  185.63  126.99  189.04  126.97  196.04   126.9
  203.05  126.88  210.05  126.89  217.05  126.95  224.05  126.96  231.05  126.95
  238.05  126.99  245.06  127.08  252.06  127.35  259.06  127.77  266.06  127.65
  273.06   126.3  280.06  124.38  287.07  122.47  294.07  120.96  298.27  120.57
  301.07  120.32  308.07  120.29  315.07  120.32  322.07  120.29  329.08  120.33
  336.08   120.4  343.08  120.36  348.53  120.32  350.08   120.3  357.08   120.3
  364.08  120.77  371.08  122.49  378.09  125.13  385.09  127.33  392.09  128.67
  399.09  129.45  406.09  129.76  413.09   129.8   420.1   129.7   427.1  129.53
   434.1  129.28   441.1  128.89   448.1  128.67   455.1  128.67  462.11  128.63
  469.11  128.55  476.11  128.56  483.11  128.53  490.11  128.51  493.46  128.51
  497.11   128.5  504.11  128.42  511.12  128.59  518.12  128.94  525.12  129.16
  532.12  129.31  539.12  129.42  546.12  129.36  553.13  129.37  560.13  129.58
  567.13   129.9  574.13  130.16  581.13  130.39  588.13  130.66  595.14  131.34
  602.14  132.59  609.14     134  616.14  135.35  623.14  136.59  630.14   137.9
  637.14  139.35  644.15  140.89  651.15   142.4  658.15  143.92  668.46  146.05
BR U #Mann= 5
       0      .1  185.63     .07  298.27    .035  348.53     .07  493.46      .1
BR D #Sta/Elev= 100
       0   157.9       7  156.29      14  154.85      21  153.64   28.01  152.52
   35.01   151.6   42.01  150.72   49.01  149.79   56.01  148.87   63.01  148.18
   70.02  147.53   77.02   146.7   84.02  145.72   91.02  144.65   98.02  143.78
  105.02  142.95  112.03     142  119.03  140.69  126.03  139.02  133.03   137.2
  140.03  135.92  147.03  134.91  154.04  133.98  161.04  133.26  168.04  132.35
  175.04  130.97  182.04  129.32  189.04  127.99  196.04   127.2  202.81  126.92
  203.05  126.91  210.05  126.92  217.05  126.97  224.05  127.06  231.05  127.03
  238.05     127  245.06   127.1  252.06  127.32  259.06  127.55  266.06  127.91
  273.06  127.78  280.06  126.59  287.07  125.02  294.07  123.36  301.07  121.56
  302.41  121.31  308.07  120.26  315.07  120.16  322.07  120.29  329.08  120.35
  336.08  120.26  343.08  120.24  350.08  120.33  352.68  120.34  357.08  120.36
  364.08  120.67  371.08  121.58  378.09  123.36  385.09  125.76  392.09  128.09
  399.09  129.34  406.09  129.59  413.09  129.63   420.1  129.44   427.1  129.23
   434.1     129   441.1  128.69   448.1  128.55   455.1  128.55  462.11  128.51
  469.11  128.42  476.11  128.29  480.76  128.26  483.11  128.25  490.11  128.04
  497.11  127.79  504.11  127.91  511.12  128.31  518.12  128.57  525.12  128.66
  532.12  128.62  539.12  128.84  546.12  129.03  553.13  129.26  560.13  129.69
  567.13  130.26  574.13  130.71  581.13  131.43  588.13  132.68  595.14  134.27
  602.14  136.22  609.14  138.33  616.14  140.36  623.14  142.34  630.14  144.15
  637.14  145.66  644.15  146.98  651.15  148.42  658.15     150  668.46  152.28
BR D #Mann= 5
       0      .1  202.81     .07  302.41    .035  352.68     .07  480.76      .1
BC Design=,, 0 ,, 0 ,,,,,,
BC Use User HTab Curves=0
BC User HTab FreeFlow(D)= 0

Type RM Length L Ch R = 1 ,55118   ,51.3,50.26,50.01
XS GIS Cut Line= 2
1642753.16063957738948.2658635821642084.85292929738933.995948061
#Sta/Elev= 30
       0   157.9      14  154.85   28.01  152.52   56.01  148.87   77.02   146.7
  112.03     142  140.03  135.92  168.04  132.35  189.04  127.99  202.81  126.92
  238.05     127  273.06  127.78  287.07  125.02  308.07  120.26  315.07  120.16
  364.08  120.67  371.08  121.58  378.09  123.36  385.09  125.76  392.09  128.09
  399.09  129.34  406.09  129.59  480.76  128.26  497.11  127.79  546.12  129.03
  560.13  129.69  581.13  131.43  595.14  134.27  630.14  144.15  668.46  152.28
#Mann= 5 ,-1 , 0
       0      .1       0  202.81     .07       0  287.07     .04       0
  385.09     .07       0  480.76      .1       0
#XS Ineff= 2 , 0
       0     260   126.5     405       0   126.5
Permanent Ineff=
       F       F
Bank Sta=287.07,385.09
XS Rating Curve= 0 ,0
Exp/Cntr=0.5,0.3

Type RM Length L Ch R = 1 ,55068   ,715.58,703.15,690.34
XS GIS Cut Line= 2
1642754.22801191738898.2772577261642085.92030163738884.007342204
#Sta/Elev= 30
       0  157.91      14  155.49   35.01  153.03   63.01  150.51   91.02  146.98
  112.03  143.79  161.04  137.75  189.04  133.02  203.05   131.9  218.25  129.23
  224.05  128.11  231.05  127.35  266.06  127.47  273.06  126.78  287.07  124.35
  301.07   122.8  315.07  120.44  350.08  119.91  364.08   120.3  371.08   121.4
  385.09  125.18  399.09   128.6  406.09  129.45  464.91  128.11  532.12  128.74
  553.13  130.34  560.13  131.43  574.13  135.09  616.14  148.19  668.46  160.45
#Mann= 5 ,-1 , 0
       0      .1       0  218.25     .07       0  287.07     .04       0
  385.09     .07       0  464.91      .1       0
Bank Sta=287.07,385.09
XS Rating Curve= 0 ,0
Exp/Cntr=0.3,0.1

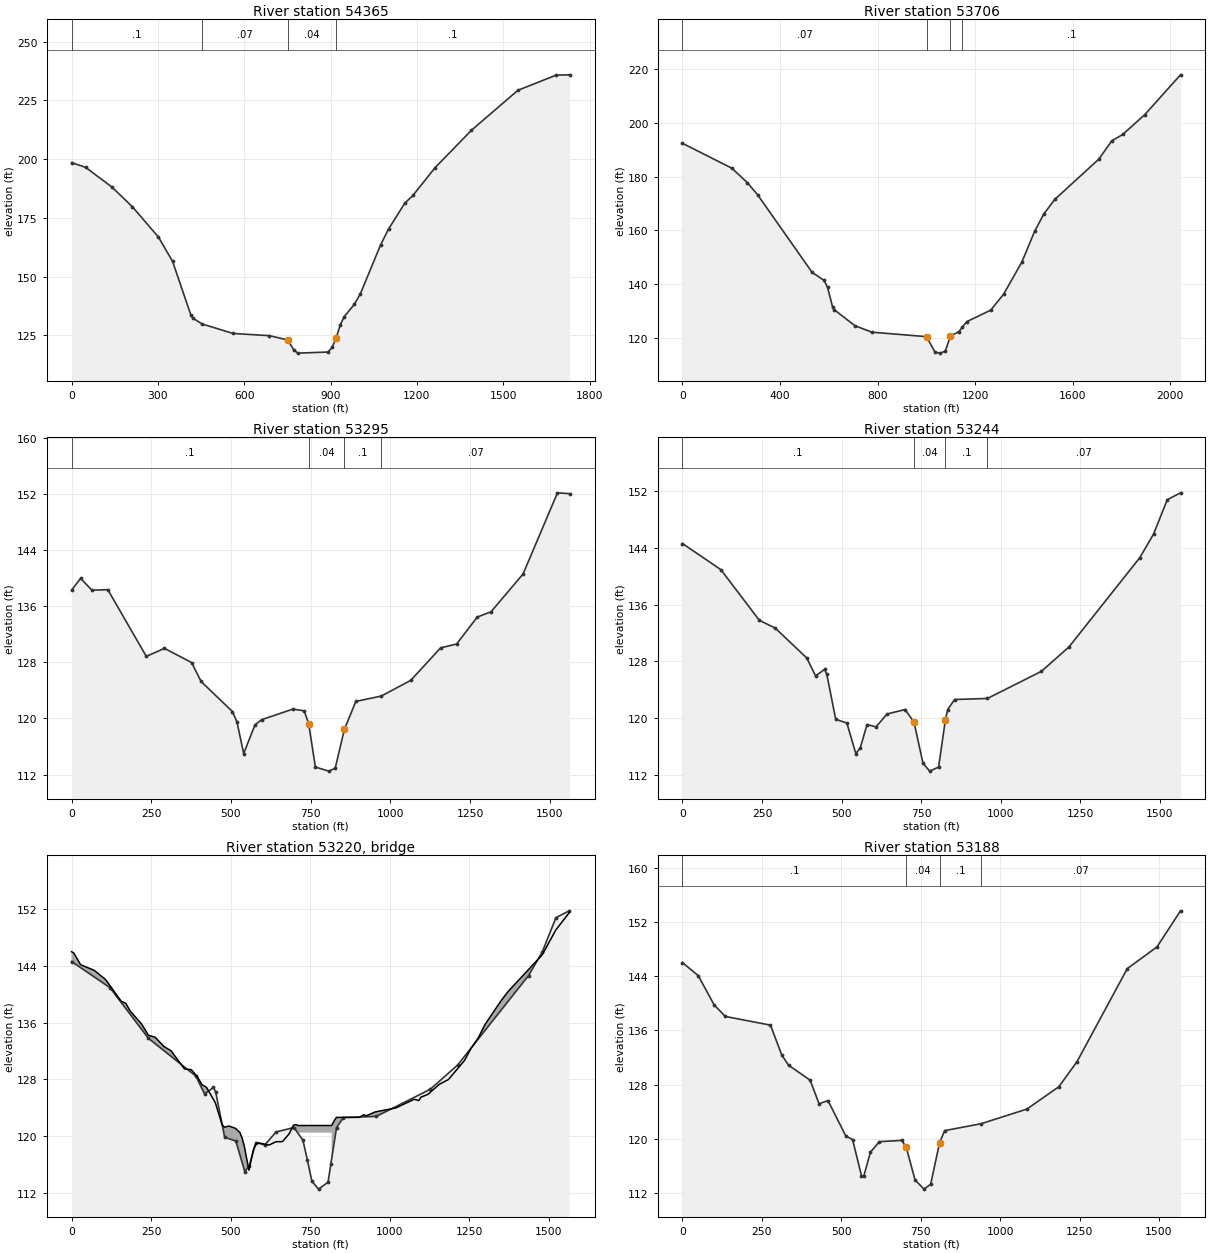
Type RM Length L Ch R = 1 ,54365   ,646.92,659.18,660.09
XS GIS Cut Line= 2
1643171.68868551738137.5357363081641445.52511394738258.670022026
#Sta/Elev= 30
       0  198.52   49.12  196.51  140.34  188.13  210.52  179.86  301.74  166.88
  350.86  156.52  414.02  133.87  421.03  132.41  453.02  129.89  561.38  125.83
  687.69   124.9  750.84  123.07  771.89  118.87  785.93  117.47  891.19  117.93
  905.22  119.89  919.25   123.9  933.29  129.42  947.32     133  982.41  138.22
 1003.46  142.73 1073.63  163.51  1101.7  170.35 1157.84  181.28 1185.91  184.57
  1263.1  196.41 1389.41  212.31  1550.8  229.32 1684.13  235.79 1730.41   235.9
#Mann= 4 ,-1 , 0
       0      .1       0  453.02     .07       0  750.84     .04       0
  919.25      .1       0
Bank Sta=750.84,919.25
XS Rating Curve= 0 ,0
Exp/Cntr=0.3,0.1

Type RM Length L Ch R = 1 ,53706   ,418.08,411.09,383.29
XS GIS Cut Line= 3
1643380.30010542737527.4851064981642221.45784029737541.910528898
1641398.82209159737865.608807921
#Sta/Elev= 30
       0  192.39  203.02  183.11  266.02  177.77  308.02  173.27  532.04  144.35
  581.05  141.41  595.05   138.8  616.05  131.48  623.05  130.47  707.06  124.56
  777.06  122.14 1001.08  120.48 1036.08  114.66 1057.08  114.35 1078.08  115.08
 1099.09  120.66 1134.09  122.36 1148.09     124 1166.45  126.06 1264.25  130.34
  1316.9  136.21 1392.13   148.2 1444.79  159.69  1482.4  166.13 1527.53  171.55
 1708.07  186.51 1760.73  193.28 1805.86  195.68 1896.13  203.03 2042.97  217.86
#Mann= 4 ,-1 , 0
       0     .07       0 1001.08     .04       0 1099.09     .07       0
 1148.09      .1       0
Bank Sta=1001.08,1099.09
XS Rating Curve= 0 ,0
Exp/Cntr=0.3,0.1

Type RM Length L Ch R = 1 ,53295   ,50,50.92,50.47
XS GIS Cut Line= 4
1643104.33785355737031.5249218341642710.94741066737099.474180132
1642285.00151688737137.2539809051641568.86698139737303.245429531
#Sta/Elev= 30
       0  138.29   28.41  139.96   63.93  138.28  113.66  138.35  234.42  128.85
  291.25  129.99  376.49  127.97  406.24  125.27  504.63  120.98  518.68  119.52
  539.77     115   574.9  119.06  595.98  119.83  694.37  121.34  729.51  121.09
  743.56  119.27  764.64  113.08  806.81   112.5  826.83  112.92  855.58  118.44
   891.5  122.43  971.53   123.2 1063.96  125.44 1157.37  130.06 1207.67  130.61
 1272.34  134.45 1315.45   135.2 1416.05  140.59 1523.83  152.15 1561.95  152.03
#Mann= 4 ,-1 , 0
       0      .1       0  743.56     .04       0  855.58      .1       0
  971.53     .07       0
Bank Sta=743.56,855.58
XS Rating Curve= 0 ,0
Exp/Cntr=0.5,0.3

Type RM Length L Ch R = 1 ,53244   ,55.08,56.01,55.52
XS GIS Cut Line= 4
1643095.82750873736982.2545044271642704.47247197737049.852192581
1642277.10951415737087.7576815931641557.57689373737254.536765799
#Sta/Elev= 30
       0  144.63  120.76  140.94  241.52   133.8  291.25  132.71   390.7  128.48
  418.23  125.95  446.34  126.88  453.37   126.2  481.48  119.84  516.62  119.31
  544.73  114.99  558.78  115.84  579.86   119.1  607.97  118.77  643.11  120.59
  699.33  121.22  727.44  119.44  755.55  113.67  776.63  112.53  804.74   113.1
  826.19  119.79  833.38  121.22  854.93  122.63  958.13  122.78 1127.98  126.61
 1214.21  130.04 1436.96  142.64 1480.08  145.96 1523.19  150.81  1564.8  151.78
#Mann= 4 ,-1 , 0
       0      .1       0  727.44     .04       0  826.19      .1       0
  958.13     .07       0
#XS Ineff= 2 , 0
       0                     840       0   121.5
Permanent Ineff=
       F       F
Bank Sta=727.44,826.19
XS Rating Curve= 0 ,0
Exp/Cntr=0.5,0.3

Type RM Length L Ch R = 3 ,53220   ,,,
BEGIN DESCRIPTION:
Ped Bridge - No survey info.  Assumed elevation based on lidar bank elevation.  Assumed 1' deck thickness.
END DESCRIPTION:
Bridge Culvert--1,0,-1,-1, 0
Deck Dist Width WeirC Skew NumUp NumDn MinLoCord MaxHiCord MaxSubmerge Is_Ogee
20,8,2.6,0, 60, 60, , , 0.95, 0, 0,0,,
       0     7.1   28.41   71.04  106.55  156.28  170.49  184.69  220.21  241.52
  262.84  291.25  312.56  355.18  376.49  396.12  410.17  424.23  452.34  473.42
  480.45   494.5  515.58  529.64  536.67  543.69  557.75   571.8  578.83  585.86
     621  642.08  663.16  684.24   698.3  705.33  712.35  817.77  825.87  833.05
  904.91  919.28  926.47  955.21 1019.88 1077.36 1091.74 1098.92 1120.48 1156.41
 1185.15 1235.45    1257 1278.56 1300.12 1350.42 1371.97 1479.76 1522.87 1566.22
  146.02  145.82  144.18  143.39  142.11  139.02  138.74  137.62  135.82  134.23
  133.95  132.62  132.05  129.48  129.38  128.34  127.25   126.9  124.69  121.61
  121.27  121.43   121.1  120.49   119.7  118.47   115.2  118.12   118.8  119.07
  118.74  119.21  119.23  120.33  121.57  121.62   121.5   121.5  122.17  122.65
  122.65  123.02  122.87  123.42  123.98   125.2  125.02   125.5  125.89  127.31
  127.99  130.66  132.44  133.83  135.74  139.08  140.36  145.56  149.08  151.59
                                                                                
                                                                                
                                                                                
                                                   120.5   120.5
                                                                                
                                                                                
       0     7.1   28.41   71.04  106.55  156.28  170.49  184.69  220.21  241.52
  262.84  291.25  312.56  355.18  376.49  396.12  410.17  424.23  452.34  473.42
  480.45   494.5  515.58  529.64  536.67  543.69  557.75   571.8  578.83  585.86
     621  642.08  663.16  684.24   698.3  705.33  712.35  817.77  825.87  833.05
  904.91  919.28  926.47  955.21 1019.88 1077.36 1091.74 1098.92 1120.48 1156.41
 1185.15 1235.45    1257 1278.56 1300.12 1350.42 1371.97 1479.76 1522.87 1566.22
  146.02  145.82  144.18  143.39  142.11  139.02  138.74  137.62  135.82  134.23
  133.95  132.62  132.05  129.48  129.38  128.34  127.25   126.9  124.69  121.61
  121.27  121.43   121.1  120.49   119.7  118.47   115.2  118.12   118.8  119.07
  118.74  119.21  119.23  120.33  121.57  121.62   121.5   121.5  122.17  122.65
  122.65  123.02  122.87  123.42  123.98   125.2  125.02   125.5  125.89  127.31
  127.99  130.66  132.44  133.83  135.74  139.08  140.36  145.56  149.08  151.59
                                                                                
                                                                                
                                                                                
                                                   120.5   120.5
                                                                                
                                                                                
BR Coef=-1 , 0 , 0 ,, 0 ,,,0.8,0,,0,
WSPro=,,,, 1 ,,,, 0 ,,,, 0 ,,,,-1 ,-1 ,-1 , 0 , 0 , 0 , 0 , 0
BR U #Sta/Elev= 30
       0  144.63  120.76  140.94  241.52   133.8   390.7  128.48  418.23  125.95
  446.34  126.88  453.37   126.2  481.48  119.84  516.62  119.31  544.73  114.99
  558.78  115.84  579.86   119.1  607.97  118.77  643.11  120.59  699.33  121.22
  727.44  119.44  741.87  116.58  755.64  113.66  776.63  112.53   806.5   113.5
  815.26  116.02  833.38  121.22  854.93  122.63  958.13  122.78 1127.98  126.61
 1214.21  130.04 1436.96  142.64 1480.08  145.96 1523.19  150.81  1564.8  151.78
BR U #Mann= 6
       0      .1  741.87     .07  755.64    .035   806.5     .07  815.26      .1
  958.13     .07
BR D #Sta/Elev= 30
       0  145.99   49.73  144.07   99.45  139.78  134.97  138.06  277.04  136.78
  312.56  132.38  333.87  130.88  401.91  128.67  430.02  125.19  458.13  125.67
  514.35  120.44  535.43  119.93  563.54   114.6  570.56   114.5  591.65  118.05
  619.76  119.61  690.03   119.8  704.09  118.83   732.2  113.98  760.31  112.62
  781.39  113.35   809.5  119.47  825.48  121.24  940.44  122.26 1084.16  124.41
 1184.76   127.7 1242.25  131.41 1400.33  145.11 1493.74   148.3 1567.93  153.62
BR D #Mann= 4
       0      .1  704.09    .035   809.5      .1  940.44     .07
BC Design=,, 0 ,, 0 ,,,,,,
BC Use User HTab Curves=0
BC User HTab FreeFlow(D)= 0

Type RM Length L Ch R = 1 ,53188   ,50.45,51.4,50.47
XS GIS Cut Line= 4
1643086.46612942736928.0570452811642697.35003942 736995.26800628
1642268.42831117737033.3117523491641545.15779737737200.957235709
#Sta/Elev= 30
       0  145.99   49.73  144.07   99.45  139.78  134.97  138.06  277.04  136.78
  312.56  132.38  333.87  130.88  401.91  128.67  430.02  125.19  458.13  125.67
  514.35  120.44  535.43  119.93  563.54   114.6  570.56   114.5  591.65  118.05
  619.76  119.61  690.03   119.8  704.09  118.83   732.2  113.98  760.31  112.62
  781.39  113.35   809.5  119.47  825.48  121.24  940.44  122.26 1084.16  124.41
 1184.76   127.7 1242.25  131.41 1400.33  145.11 1493.74   148.3 1567.93  153.62
#Mann= 4 ,-1 , 0
       0      .1       0  704.09     .04       0   809.5      .1       0
  940.44     .07       0
#XS Ineff= 2 , 0
       0                     837       0   120.5
Permanent Ineff=
       F       F
Bank Sta=704.09,809.5
XS Rating Curve= 0 ,0
Exp/Cntr=0.5,0.3

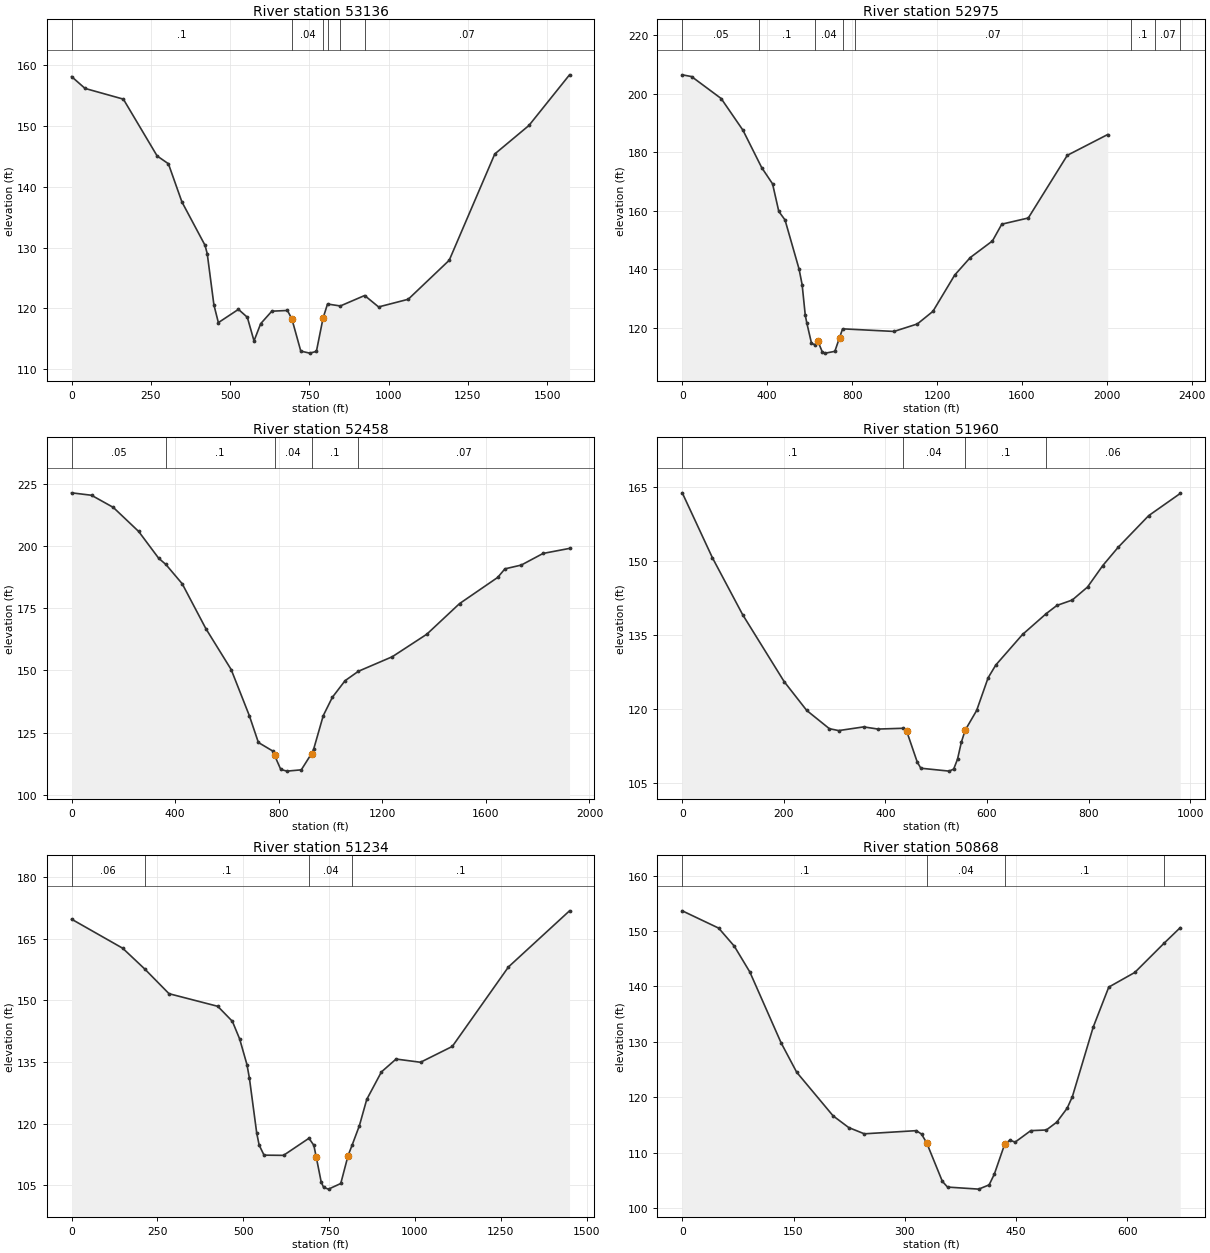
Type RM Length L Ch R = 1 ,53136   ,167.97,161.14,124.18
XS GIS Cut Line= 4
1643077.95578462736878.7866278741642690.87510075736945.646018744
1642260.53630845736983.8154530531641533.86770977737152.248572007
#Sta/Elev= 30
       0  158.13   42.62  156.18  163.38  154.42  269.94  145.07  305.46  143.79
  348.08  137.51  420.92  130.38  427.95     129  449.03  120.56  463.09  117.65
  526.33  119.83  554.44  118.53  575.53  114.64  596.61  117.48  631.75  119.53
  680.94  119.65  694.99  118.25   723.1  112.96  751.21  112.63   772.3  112.91
  793.38   118.4  807.38  120.71  847.75  120.39  924.56  122.11  968.55  120.23
 1061.96  121.49  1191.3  127.91 1335.02   145.4  1442.8  150.09 1570.77  158.42
#Mann= 6 ,-1 , 0
       0      .1       0  694.99     .04       0  793.38      .1       0
  807.38     .07       0  847.75      .1       0  924.56     .07       0
Bank Sta=694.99,793.38
XS Rating Curve= 0 ,0
Exp/Cntr=0.3,0.1

Type RM Length L Ch R = 1 ,52975   ,523.12,516.98,502.07
XS GIS Cut Line= 3
1643016.48538196 736612.00082545 1641649.9392211737039.756271914
1641104.40045545737213.112823233
#Sta/Elev= 30
       0  206.48   44.01  205.88  183.37  198.37  286.06  187.52  374.08  174.77
  425.43  169.19  454.77  159.77  484.11  156.84  550.12   140.1  564.79  134.69
  579.46  124.27  586.79   121.6   608.8  114.68  623.47  114.13  638.14  115.51
  660.14  111.62  674.81  111.29  718.82   111.9  740.83  116.56   755.5   119.6
  997.55  118.71 1107.57  121.27 1180.92  125.58 1283.61     138 1356.96  143.99
 1461.31  149.66 1505.38   155.4 1630.24  157.51 1813.87  178.94 2004.35  186.06
#Mann= 8 ,-1 , 0
       0     .05       0  363.73      .1       0  623.47     .04       0
   755.5      .1       0  815.27     .07       0 2113.56      .1       0
 2228.61     .07       0 2346.02      .1       0
Bank Sta=638.14,740.83
XS Rating Curve= 0 ,0
Exp/Cntr=0.3,0.1

Type RM Length L Ch R = 1 ,52458   ,430.67,498.15,545.74
XS GIS Cut Line= 4
1642976.82442795736292.955632031 1642201.1961609736319.701434359
1642040.72134706736405.2880017461641077.87246387736341.098076195
#Sta/Elev= 30
       0  221.29   77.05  220.31   161.1  215.44  259.15  205.78   336.2  195.05
  364.21  192.53  427.25  184.78  518.31  166.82  616.37  150.34  686.41  131.85
  721.43  121.06  776.09  117.68  784.02  115.88  807.82  110.23  831.62  109.56
  887.16  110.08  926.82  116.62  934.76  118.33  971.99  131.85 1007.07   139.2
 1056.18  145.87 1107.81  149.66 1238.58  155.49 1371.88  164.53 1498.15  176.81
 1645.48  187.32 1673.54  190.77 1736.68  192.29 1820.87  196.96 1922.94  198.98
#Mann= 5 ,-1 , 0
       0     .05       0  364.21      .1       0  784.02     .04       0
  926.82      .1       0 1107.81     .07       0
Bank Sta=784.02,926.82
XS Rating Curve= 0 ,0
Exp/Cntr=0.3,0.1

Type RM Length L Ch R = 1 ,51960   ,758.59,725.93,687.14
XS GIS Cut Line= 4
1642495.54086566736004.400926128 1642205.2292401735901.619791612
1641979.83201534735879.9816580271641565.10112172735715.892478362
#Sta/Elev= 30
       0  163.85   59.41  150.66  118.81  139.13   200.5  125.54  245.05  119.67
   289.6  115.97  307.97  115.58  357.19  116.33  385.32  115.89  434.55  116.05
  441.58  115.54  462.68  109.18  469.71  107.94   525.6  107.35   534.4  107.77
  541.93  109.77  549.46  113.21  556.99  115.65  579.57  119.66  602.15  126.29
  617.21  128.88  669.91  135.09  716.88  139.35  737.66  140.99  767.77  142.08
  797.88  144.72  827.99  149.09   858.1  152.78  918.33  159.22  980.41  163.72
#Mann= 4 ,-1 , 0
       0      .1       0  434.55     .04       0  556.99      .1       0
  716.88     .06       0
Bank Sta=441.58,556.99
XS Rating Curve= 0 ,0
Exp/Cntr=0.3,0.1

Type RM Length L Ch R = 1 ,51234   ,334.42,366.1,385.09
XS GIS Cut Line= 4
1642698.66808391735041.2520838681642044.74641606735149.694649681
1641893.27948101735178.5454944521641270.44224051735292.662625611
#Sta/Elev= 30
       0  169.74  149.01  162.66  212.75  157.64  283.82   151.6  425.74  148.53
  468.31  144.88   489.6  140.57  510.88  134.32  517.98  131.03  539.27  117.67
  546.36  114.74  560.55   112.3  617.32  112.25  691.36  116.41  705.61   114.7
  712.73  111.79  726.99  105.78  734.11  104.44  748.36  104.03  783.99   105.4
  805.37  112.21  817.04  114.73  838.39  119.51  859.74  125.88  902.44  132.56
  945.14  135.69 1016.31  134.91 1108.82  138.76  1272.5  158.12 1450.25  171.77
#Mann= 4 ,-1 , 0
       0     .06       0  212.75      .1       0  691.36     .04       0
  817.04      .1       0
Bank Sta=712.73,805.37
XS Rating Curve= 0 ,0
Exp/Cntr=0.3,0.1

Type RM Length L Ch R = 1 ,50868   ,191.04,211.83,229.06
XS GIS Cut Line= 2
1642341.75851277734819.9685224891641671.59857459734783.915614411
#Sta/Elev= 30
       0  153.63   49.07  150.51    70.1  147.26   91.13  142.58  133.19  129.82
  154.22  124.51  203.29  116.64  224.32  114.53  245.35   113.4  315.46  113.97
  322.47  113.35  329.48  111.75  350.51  104.83  357.52  103.79  399.58  103.42
   413.6  104.19  420.61  106.13  434.63  111.56  441.64  112.25  448.65   111.9
  469.68  113.97  490.71  114.09  504.73   115.5  518.75  118.02  525.76   120.1
   553.8  132.63  574.83  139.87  609.88  142.51  649.32  147.78  671.13  150.59
#Mann= 4 ,-1 , 0
       0      .1       0  329.48     .04       0  434.63      .1       0
  649.32     .07       0
Bank Sta=329.48,434.63
XS Rating Curve= 0 ,0
Exp/Cntr=0.3,0.1

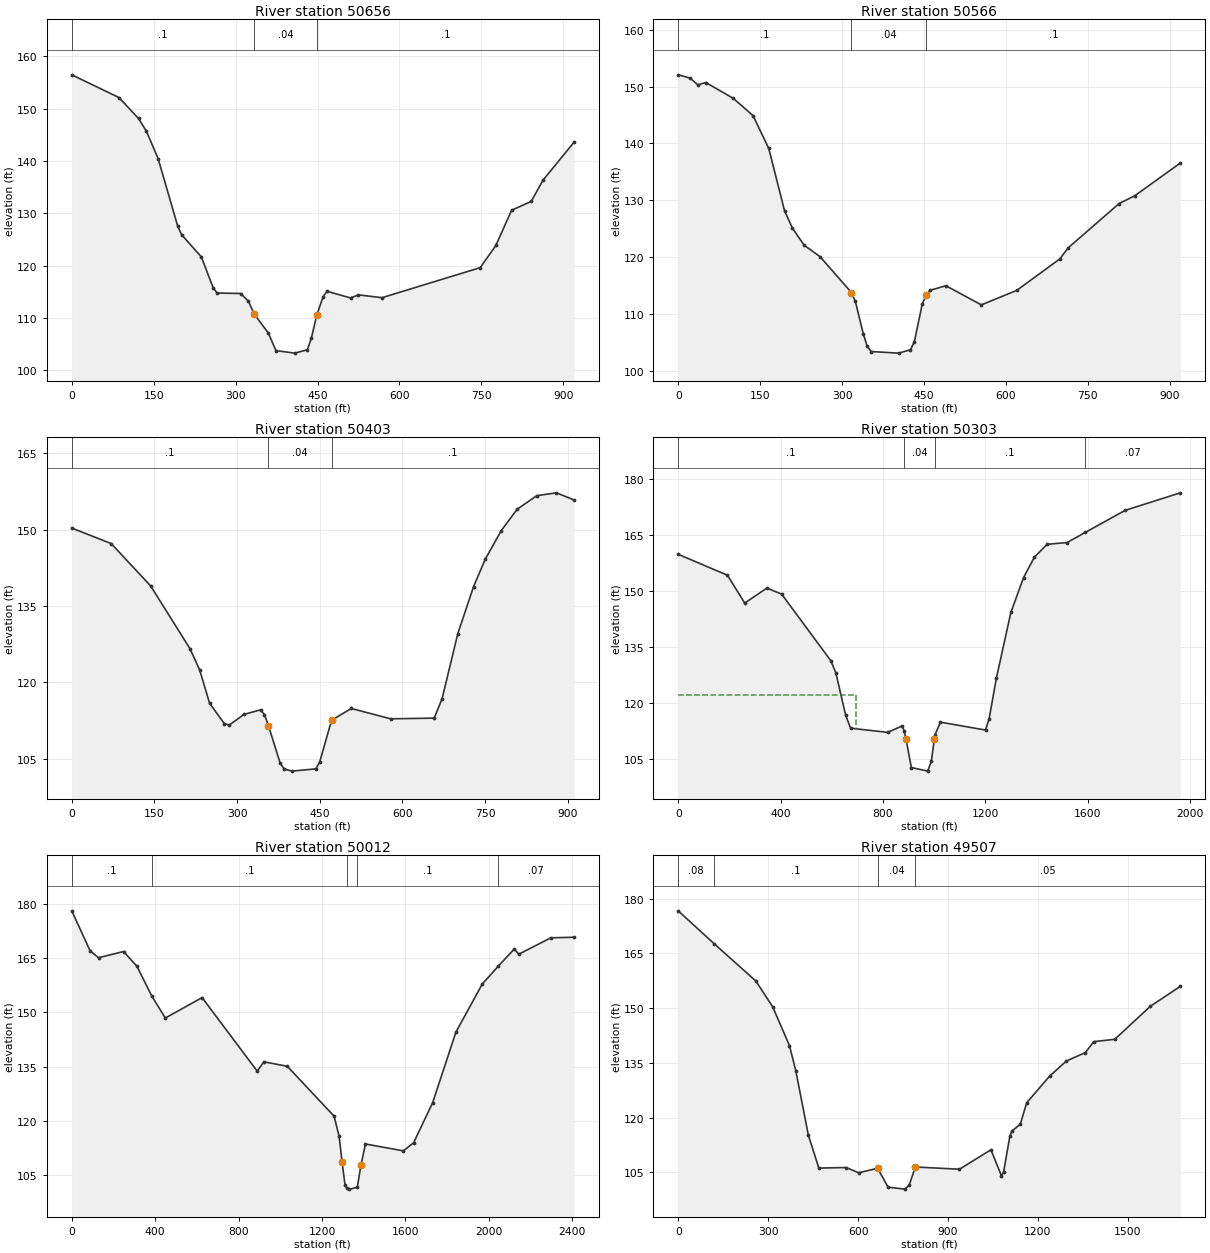
Type RM Length L Ch R = 1 ,50656   ,89.06,90.29,93.18
XS GIS Cut Line= 2
1642367.20762433734677.8776495161641472.24720061734467.922479019
#Sta/Elev= 30
       0  156.46   86.28  152.12  122.23  148.11  136.61  145.69  158.18  140.42
  194.13  127.47  201.32  125.87  237.27  121.64  258.84  115.77  266.03  114.74
  309.17  114.65  323.55  113.16  333.91  110.73   359.5  107.16  373.88  103.73
  408.43  103.25   431.4   103.9  438.59  106.08   448.4  110.45  460.16  114.03
  467.35  115.07  510.49   113.8  524.87  114.39  568.01  113.85  747.76  119.59
  776.53  123.85  805.29  130.57  841.24  132.26  862.81  136.32  919.26  143.53
#Mann= 3 , 0 , 0
       0      .1       0  333.91     .04       0   448.4      .1       0
Bank Sta=333.91,448.4
XS Rating Curve= 0 ,0
Exp/Cntr=0.3,0.1

Type RM Length L Ch R = 1 ,50566   ,37.13,40.85,40.69
XS GIS Cut Line= 2
1642375.69066153734590.9265182911641482.85099709734372.488310605
#Sta/Elev= 30
       0  152.06   21.62  151.49   36.03   150.3   50.45  150.71  100.89  147.92
  136.92  144.89  165.75  139.12  194.57  128.19  208.99  125.12  230.61  122.11
  259.43  120.12  317.08   113.8  324.29  112.24   338.7  106.56  345.91  104.37
  353.12  103.43  403.56  103.15  425.18  103.74  432.39  105.19   446.8  111.82
  454.01  113.33  461.21  114.19  490.04     115   554.9  111.63  619.76  114.18
  699.03  119.74  713.44  121.62  807.12  129.44  835.95  130.82  919.17  136.56
#Mann= 3 , 0 , 0
       0      .1       0  317.08     .04       0  454.01      .1       0
Bank Sta=317.08,454.01
XS Rating Curve= 0 ,0
Exp/Cntr=0.3,0.1

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
Type RM Length L Ch R = 1 ,50403   ,121.54,99.06,94.46
XS GIS Cut Line= 3
1642376.07483128734558.2827715721642124.44001961734358.910574645
1641547.61560518  734235.0288212
#Sta/Elev= 30
       0  150.29   71.45  147.25  142.89  138.96  214.34  126.63   232.2  122.41
  250.06  115.89  276.86  111.89  285.79  111.61  312.58   113.7  342.52   114.6
  349.68  113.65  356.84  111.49  378.32  104.07  385.48  102.97   399.8  102.56
  442.76  103.01  449.92  104.37   471.4  112.55  507.19  114.86  578.79  112.83
  657.55  112.97  671.86  116.75   700.5  129.57  729.14  138.81  750.62  144.26
  779.26  149.78   807.9  153.96   843.7  156.65  879.49  157.21  911.02  155.83
#Mann= 3 , 0 , 0
       0      .1       0  356.84     .04       0   471.4      .1       0
Bank Sta=356.84,471.4
XS Rating Curve= 0 ,0
Exp/Cntr=0.3,0.1

Type RM Length L Ch R = 1 ,50303   ,95.66,97.14,85.93
XS GIS Cut Line= 4
1642758.40662128734829.2771300971642235.88326271734275.153417438
1641817.54601347734201.2231276931641051.12666155734083.752361134
#Sta/Elev= 30
       0  159.94  192.43  154.33  259.78  146.87  346.37   150.9   404.1  149.27
  596.52  131.42  615.77  128.23  654.25  116.84   673.5  113.37   818.5  112.26
  875.37     114  882.48  112.72  889.58  110.59  910.91  102.85  974.89  101.88
   989.1  104.56 1000.89  110.56 1003.32  111.61 1024.64  114.99 1200.62  112.88
 1214.78  115.89 1243.11  126.78 1299.76  144.38 1349.33   153.7 1391.82  159.19
  1441.4  162.62  1519.3  163.09 1590.45165.7947 1745.91   171.7 1961.83   176.4
#Mann= 4 ,-1 , 0
       0      .1       0  882.48     .04       0 1003.32      .1       0
 1590.45     .07       0
#XS Ineff= 2 , 0
          694.77  122.36
Permanent Ineff=
       F       F
Bank Sta=889.58,1000.89
XS Rating Curve= 0 ,0
Exp/Cntr=0.3,0.1

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
Type RM Length L Ch R = 1 ,50012   ,88.98,84.14,82.53
XS GIS Cut Line= 3
 1643277.9162311734572.4714299891642169.83774634733956.102772847
1641030.59455416733966.491008639
#Sta/Elev= 30
       0  177.99   88.11  166.94  128.16  165.05  248.31  166.76  312.39  162.69
  383.96  154.45  448.56  148.42  624.79  154.05  889.12  133.76  921.16  136.34
  1033.3   135.1 1257.58  121.35 1281.97  115.77 1295.97  108.72 1309.97  102.44
 1318.45  101.42 1330.97  101.21 1368.76   101.7 1386.98  107.95 1407.98  113.66
 1589.98  111.77 1638.98  114.01 1729.99  125.02 1841.99  144.56    1968  157.77
 2044.24  162.68    2122  167.48    2143  166.02 2297.01  170.55 2407.25   170.7
#Mann= 5 ,-1 , 0
       0      .1       0  383.96      .1       0 1318.45     .04       0
 1368.76      .1       0 2044.24     .07       0
Bank Sta=1295.97,1386.98
XS Rating Curve= 0 ,0
Exp/Cntr=0.3,0.1

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
Type RM Length L Ch R = 1 ,49507   ,146.8,166.81,179.35
XS GIS Cut Line= 2
 1642753.8802615733443.3883926721641079.24556604733482.755935237
#Sta/Elev= 30
       0  176.67  119.94  167.64  259.07  157.42  315.09  150.36   371.1  139.71
  392.11  132.88  434.12  115.17  469.13  106.13  560.15  106.28  602.17  104.84
  665.18  106.08  700.19  100.89  756.21  100.36  770.21   101.4  791.22  106.43
  938.26  105.82 1043.29  111.15  1078.3  104.02  1085.3  104.93 1106.31  114.85
 1113.31  116.28 1141.32  118.18 1162.32  124.01 1239.34  131.38 1295.36  135.51
 1358.38   137.8 1386.38   140.8  1456.4  141.44 1575.44  150.52  1675.1  155.96
#Mann= 4 ,-1 , 0
       0     .08       0  119.94      .1       0  665.18     .04       0
  791.22     .05       0
Bank Sta=665.18,791.22
XS Rating Curve= 0 ,0
Exp/Cntr=0.3,0.1

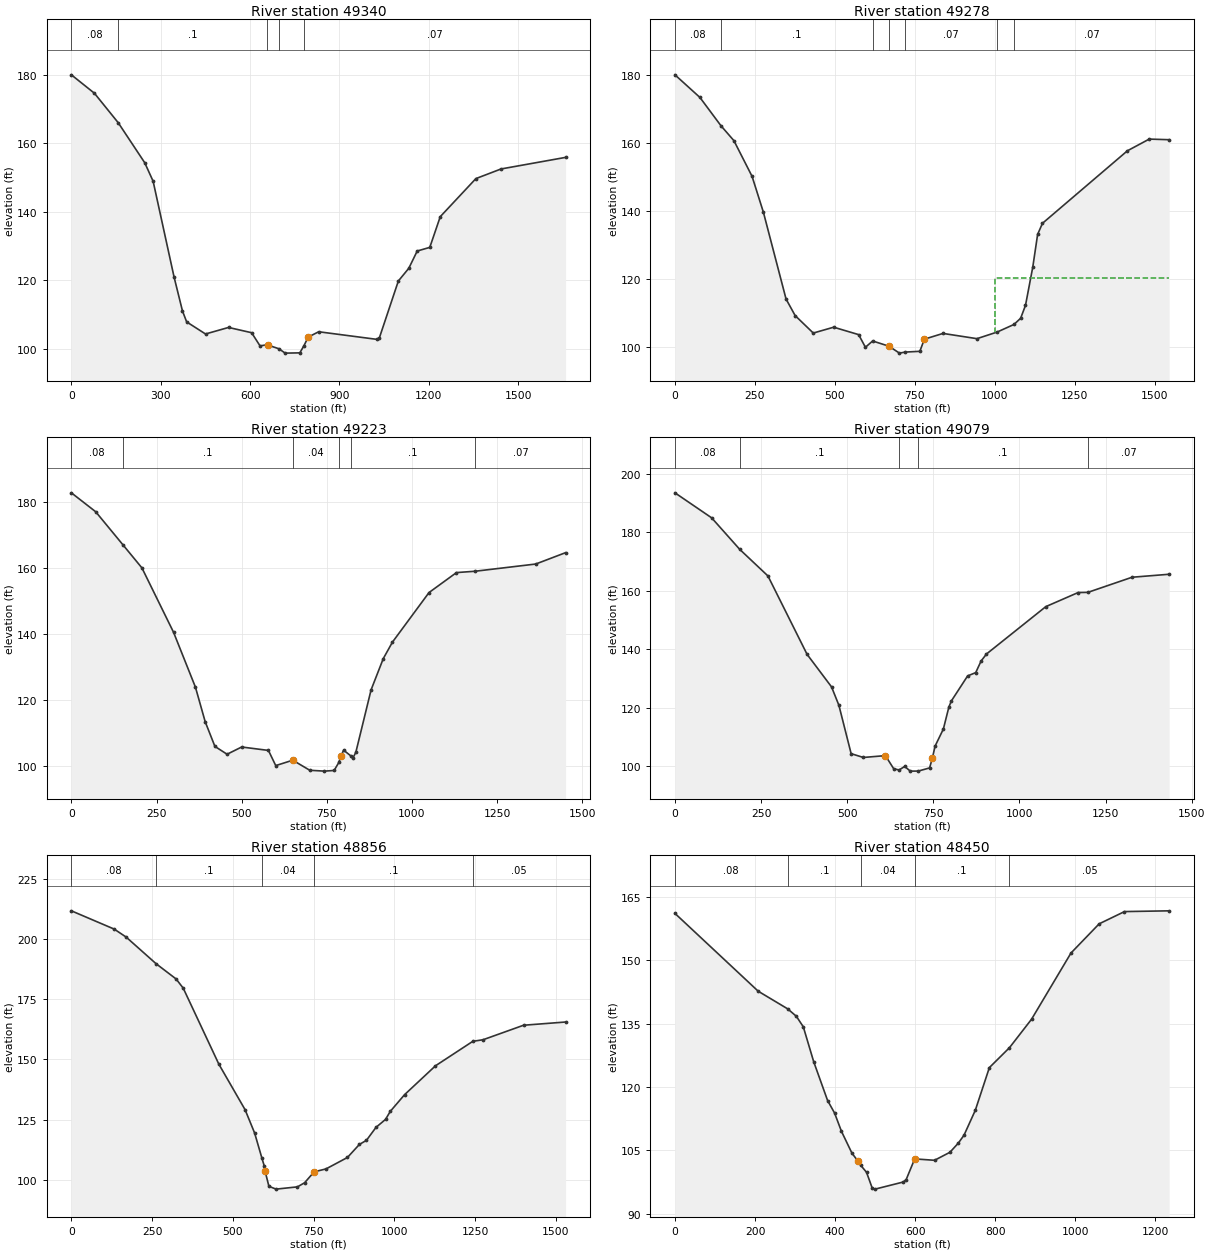
Type RM Length L Ch R = 1 ,49340   ,53.1,62.65,67.81
XS GIS Cut Line= 2
1642722.26820637733370.4066822531641071.76111963 733199.42391853
#Sta/Elev= 30
       0  180.02   77.41  174.64  157.31  166.03  246.31  154.35  274.46  148.95
  344.84  120.96  372.99  111.07  387.06  107.87   450.4  104.34  527.81  106.25
  605.22  104.71  633.37  100.87  655.77  101.17  661.52  101.05  696.71  100.03
  717.82   98.75  767.08   98.83  781.16  100.96  795.23  103.44  830.42  104.99
 1027.47  102.75 1034.51  103.31 1097.85  119.81 1133.03  123.54 1161.18  128.57
 1203.41  129.63  1238.6   138.6 1358.23  149.72 1442.68  152.53 1659.34  155.91
#Mann= 5 ,-1 , 0
       0     .08       0  157.31      .1       0  655.77     .07       0
  696.71     .04       0  781.16     .07       0
Bank Sta=661.52,795.23
XS Rating Curve= 0 ,0
Exp/Cntr=0.3,0.1

Type RM Length L Ch R = 1 ,49278   ,50.63,54.55,65.39
XS GIS Cut Line= 3
1642697.84209722733345.9805731481641877.82272014733213.381695151
1641218.31777428732937.715606675
#Sta/Elev= 30
       0  180.08      78  173.44  143.88  165.11  184.36  160.73  241.09  150.25
  276.55   139.7  347.46  114.17  375.82  109.32  432.55  104.18  496.36   105.9
  574.36  103.72  595.64     100  618.19  101.85  669.34  100.31     702   98.28
  719.88   98.59  765.82   98.81     780  102.38  838.26  104.07  944.47  102.53
 1007.49104.4731 1060.04   106.7 1081.04  108.53 1096.21  112.32 1118.97  123.56
 1134.15  133.18 1149.32  136.44 1414.86  157.75 1483.15  161.19 1545.47  161.01
#Mann= 7 ,-1 , 0
       0     .08       0  143.88      .1       0  618.19     .07       0
  669.34     .04       0  719.88     .07       0 1007.49      .1       0
 1060.04     .07       0
#XS Ineff= 2 , 0
                         1001.23          120.42
Permanent Ineff=
       F       F
Bank Sta=669.34,780
XS Rating Curve= 0 ,0
Exp/Cntr=0.3,0.1

Type RM Length L Ch R = 1 ,49223   ,105.22,144.54,161.17
BEGIN DESCRIPTION:
Narrowing of river valley.  Aprroximate reach.  No underwater geometry available.
END DESCRIPTION:
XS GIS Cut Line= 3
1642711.79987389733321.5544640421641937.14327081733164.529476926
1641420.70553541732752.775066286
#Sta/Elev= 30
       0  182.86   71.42  177.11   152.2  166.96  207.13  160.05  299.98  140.49
  364.26  123.81  392.83  113.33   421.4  105.82  457.11  103.44  499.97  105.64
  578.53   104.6  599.96   99.99  649.95  101.63  699.95   98.57   742.8   98.31
  771.37   98.51  785.66  101.03  790.41  102.78  799.36  104.67  821.35  102.86
  826.22  102.22  835.17  104.04  879.94  123.01  915.75  132.51   942.6   137.5
 1050.03  152.57 1130.61  158.63 1185.24159.0349 1363.37  161.23  1450.9  164.68
#Mann= 6 ,-1 , 0
       0     .08       0   152.2      .1       0  649.95     .04       0
  785.66     .07       0  821.35      .1       0 1185.24     .07       0
Bank Sta=649.95,790.41
XS Rating Curve= 0 ,0
Exp/Cntr=0.3,0.1

Type RM Length L Ch R = 1 ,49079   ,200.36,222.29,165.93
XS GIS Cut Line= 4
1642771.12042454733216.8711393031642184.89380601733115.677258715
1642003.44270982733014.483378157 1641438.1527562732731.838401347
#Sta/Elev= 30
       0  193.55  106.55  184.98  188.09  174.18  269.93  165.08  383.59  138.22
  454.63  127.07  475.94  120.77  511.45  104.21  546.97  102.91  610.93  103.54
  634.97   99.06  650.48   98.62  667.03   99.84  683.06   98.23  706.43   98.25
  739.17   99.33  747.18  102.62   755.2  106.82  779.24  112.66  795.27  120.22
  802.66  122.31  849.62  130.84  873.09  131.97  888.75  135.95   904.4  138.35
 1076.58  154.57 1170.49   159.4 1198.53  159.45 1327.02  164.64 1434.67  165.66
#Mann= 5 ,-1 , 0
       0     .08       0  188.09      .1       0  650.48     .04       0
  706.43      .1       0 1198.53     .07       0
Bank Sta=610.93,747.18
XS Rating Curve= 0 ,0
Exp/Cntr=0.3,0.1

Type RM Length L Ch R = 1 ,48856   ,414.73,406.6,384.85
XS GIS Cut Line= 2
1642910.49288194733144.5318966211641456.88145322732667.565646589
#Sta/Elev= 30
       0  211.62  132.61  204.04  169.45  200.74  262.07   189.7  324.16  183.36
  346.26  179.54  456.77  147.95  537.81  129.11  567.27  119.45  589.38  109.24
  596.74  105.96  599.45  103.75  611.48   97.35  633.58   96.18  699.88   97.12
  721.98   98.82  751.45  103.34  788.29  104.57  854.59  109.31  891.43   114.7
  913.53  116.43     943   121.8  972.47   125.1   987.2  128.43 1031.41  135.35
 1127.18  147.34 1242.71  157.49 1274.52  158.15 1399.77  164.16 1529.86   165.5
#Mann= 5 ,-1 , 0
       0     .08       0  262.07      .1       0  589.38     .04       0
  751.45      .1       0 1242.71     .05       0
Bank Sta=599.45,751.45
XS Rating Curve= 0 ,0
Exp/Cntr=0.3,0.1

Type RM Length L Ch R = 1 ,48450   ,594.64,562.19,510.75
XS GIS Cut Line= 4
1642796.27607659732819.5642565641642426.82683094732550.048003614
1642199.70639305732516.7370060531641654.61734208732465.256373465
#Sta/Elev= 30
       0  161.15  207.95  142.72  281.44  138.55  303.26  136.78  320.59  134.28
  346.59  126.01  381.25  116.83  398.58  113.89  415.91  109.53   441.9   104.4
  457.31  102.44  464.38  101.45  478.53   99.83  492.68    96.1  499.76   95.85
  570.51   97.54  577.58   98.13  598.81  103.01  648.33  102.68  686.86  104.58
  707.95  106.77  722.02  108.63  750.14  114.51   785.3  124.63  835.55  129.35
  890.76   136.1   989.2  151.77 1059.51  158.68 1122.79  161.58 1234.37  161.76
#Mann= 5 ,-1 , 0
       0     .08       0  281.44      .1       0  464.38     .04       0
  598.81      .1       0  835.55     .05       0
Bank Sta=457.31,598.81
XS Rating Curve= 0 ,0
Exp/Cntr=0.3,0.1