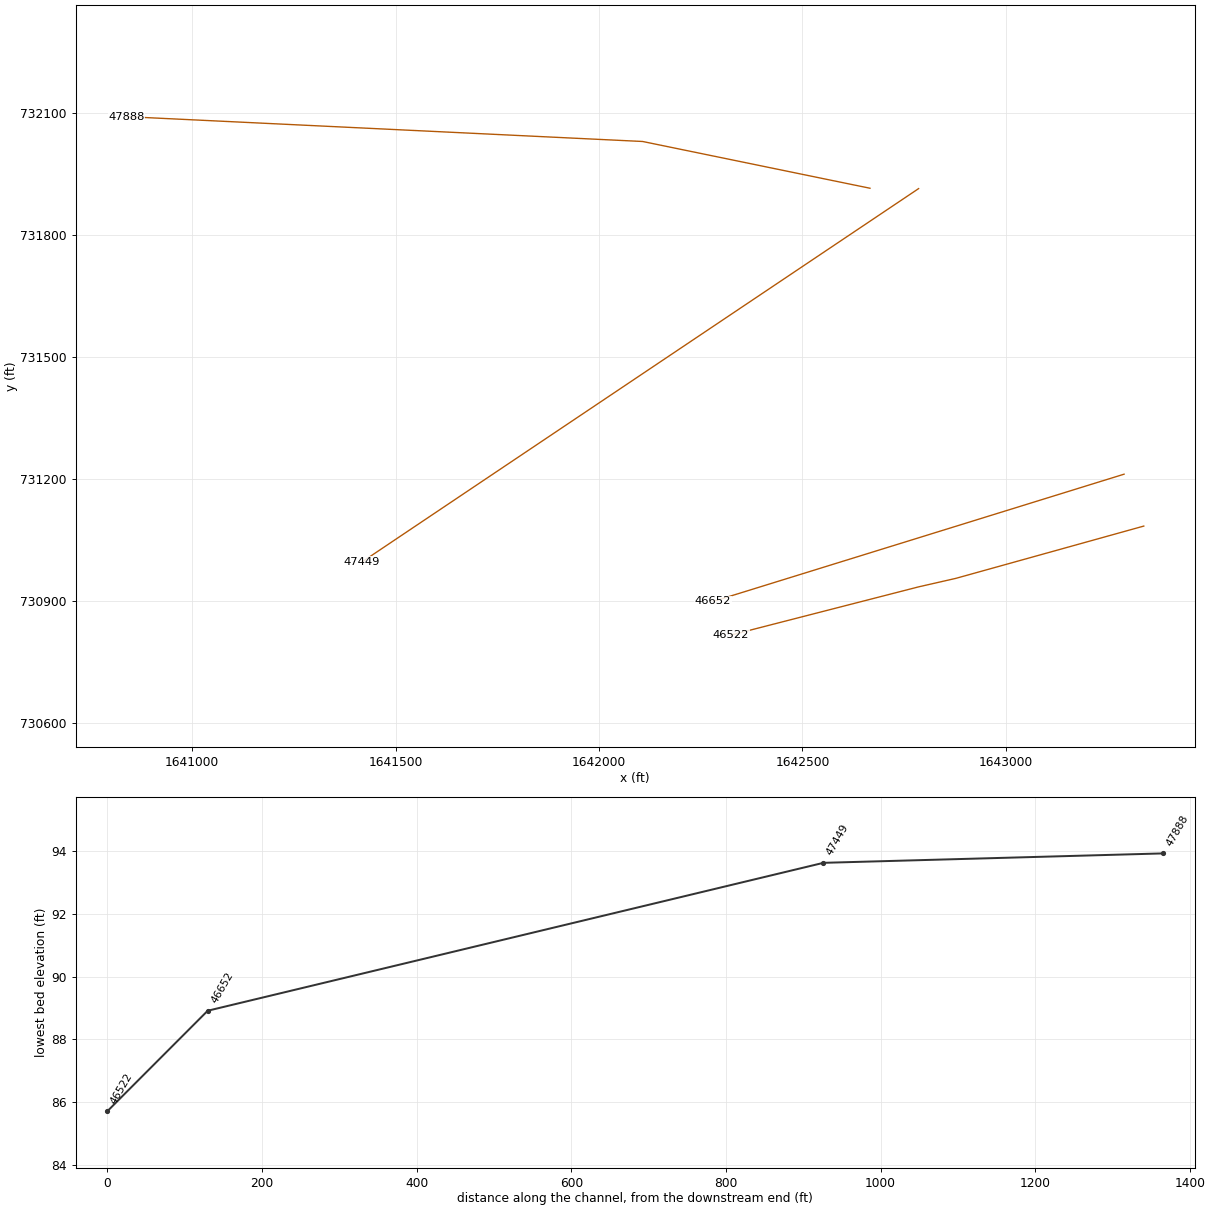
HEC-RAS study bigelkcreek.prj: Big Elk Creek

--- bigelkcreek.g23 (geometry) --- (continued)

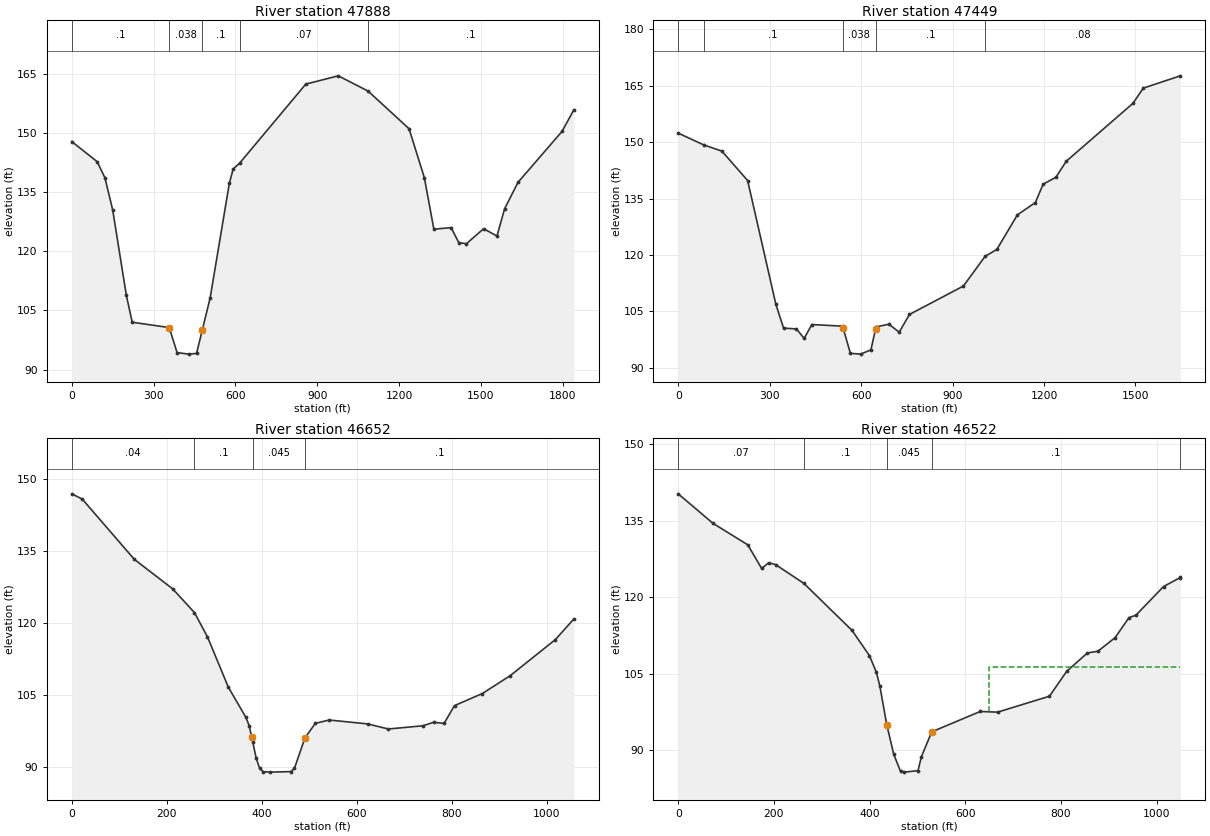
Type RM Length L Ch R = 1 ,47888   ,334.71,439.1,496.12
XS GIS Cut Line= 3
1642666.06035884731914.1107774671642107.23608075732029.122783944
1640838.75513276732090.217280358
#Sta/Elev= 30
       0  147.77   92.91   142.7  121.49   138.6  150.08  130.43  200.11   108.8
  221.55     102  357.34  100.65  385.92   94.31   428.8   93.92  457.39    94.1
  478.83  100.12  507.42  108.22  577.55  137.16  591.56  140.82  615.09  142.28
  857.87  162.33  977.01  164.43 1086.25  160.56 1236.31  151.03 1292.37  138.66
 1327.41  125.57 1390.48  125.97 1418.52   122.2 1446.55  121.88 1509.62  125.69
 1558.68  123.85 1586.71  130.75 1635.77  137.44 1796.95  150.34 1840.48   155.8
#Mann= 5 ,-1 , 0
       0      .1       0  357.34    .038       0  478.83      .1       0
  615.09     .07       0 1086.25      .1       0
Bank Sta=357.34,478.83
XS Rating Curve= 0 ,0
Exp/Cntr=0.3,0.1

Type RM Length L Ch R = 1 ,47449   ,798.37,796.3,698.32
XS GIS Cut Line= 2
1642785.49029928731913.1932631281641417.65010022730995.162052587
#Sta/Elev= 30
       0   152.4   83.85  149.26  143.32  147.61  227.62   139.8  320.36  106.86
  345.65  100.54   387.8  100.32  413.09    97.8  438.38  101.49  539.55  101.06
  541.13  100.51  564.84   93.83  598.56   93.62  632.28   94.77   647.5  100.34
  649.14  100.88  691.29  101.57  725.02   99.46  758.74  104.17  935.78  111.74
 1006.86  119.63 1045.37  121.46 1112.82  130.66 1171.83  133.94 1197.12   138.8
 1239.27  140.67 1272.99  144.91 1492.18  160.34 1525.91  164.37 1647.35  167.64
#Mann= 5 ,-1 , 0
       0     .04       0   83.85      .1       0  539.55    .038       0
  649.14      .1       0 1006.86     .08       0
Bank Sta=541.13,647.5
XS Rating Curve= 0 ,0
Exp/Cntr=0.3,0.1

Type RM Length L Ch R = 1 ,46652   ,128.38,129.77,110.84
XS GIS Cut Line= 2
1643290.53898819731210.8599301431642280.44161038730897.834961489
#Sta/Elev= 30
       0  146.91   21.99  145.82  131.91  133.24  212.52  127.11  258.34  122.17
  285.81  117.11  329.78  106.61  366.42  100.38  373.75   98.59  378.63   96.32
  381.08   95.26  388.41   91.81  395.73   89.69  403.06   88.99  417.72   88.91
  461.69   89.02  469.02   89.71     491   96.01  512.99   99.08   542.3   99.77
  622.92   98.96  666.89    97.9  740.17   98.58  762.16   99.31  784.14   99.06
  806.13  102.77  864.75  105.29  923.38  109.01 1018.65  116.54 1057.49  120.83
#Mann= 4 ,-1 , 0
       0     .04       0  258.34      .1       0  381.08    .045       0
     491      .1       0
Bank Sta=378.63,491
XS Rating Curve= 0 ,0
Exp/Cntr=0.5,0.3

Type RM Length L Ch R = 1 ,46522   ,93.42,92.18,90.41
BEGIN DESCRIPTION:
Modified under water portion by 2 feet as per "flow depth" in bridge inspection notes.
END DESCRIPTION:
XS GIS Cut Line= 4
1643338.97023286731083.2311460381642877.02400906730954.621117845
1642785.39323339730933.6769405451642324.47446395730815.154971257
#Sta/Elev= 30
       0  140.29   72.66   134.5  145.32  130.29  174.39  125.65  188.92  126.77
  203.45  126.41  262.46  122.74  363.31   113.5  399.64  108.56  414.18  105.27
  421.44  102.57  435.97   94.94  450.51   89.19  464.68   85.85  472.31   85.71
  501.06   85.99  508.24   88.71  529.78   93.61  631.33   97.61  667.47   97.47
  775.89   100.6  812.02  105.49  855.39  109.09  877.07  109.41  913.21  112.09
  942.12  116.01  956.58  116.48  1014.4  122.11 1047.85   123.8 1049.42  123.89
#Mann= 5 ,-1 , 0
       0     .07       0  262.46      .1       0  435.97    .045       0
  529.78      .1       0 1047.85     .08       0
#XS Ineff= 2 ,-1
       0     380   106.4     650 1049.42   106.3
Permanent Ineff=
       F       F
Bank Sta=435.97,529.78
XS Rating Curve= 0 ,0
Exp/Cntr=0.5,0.3