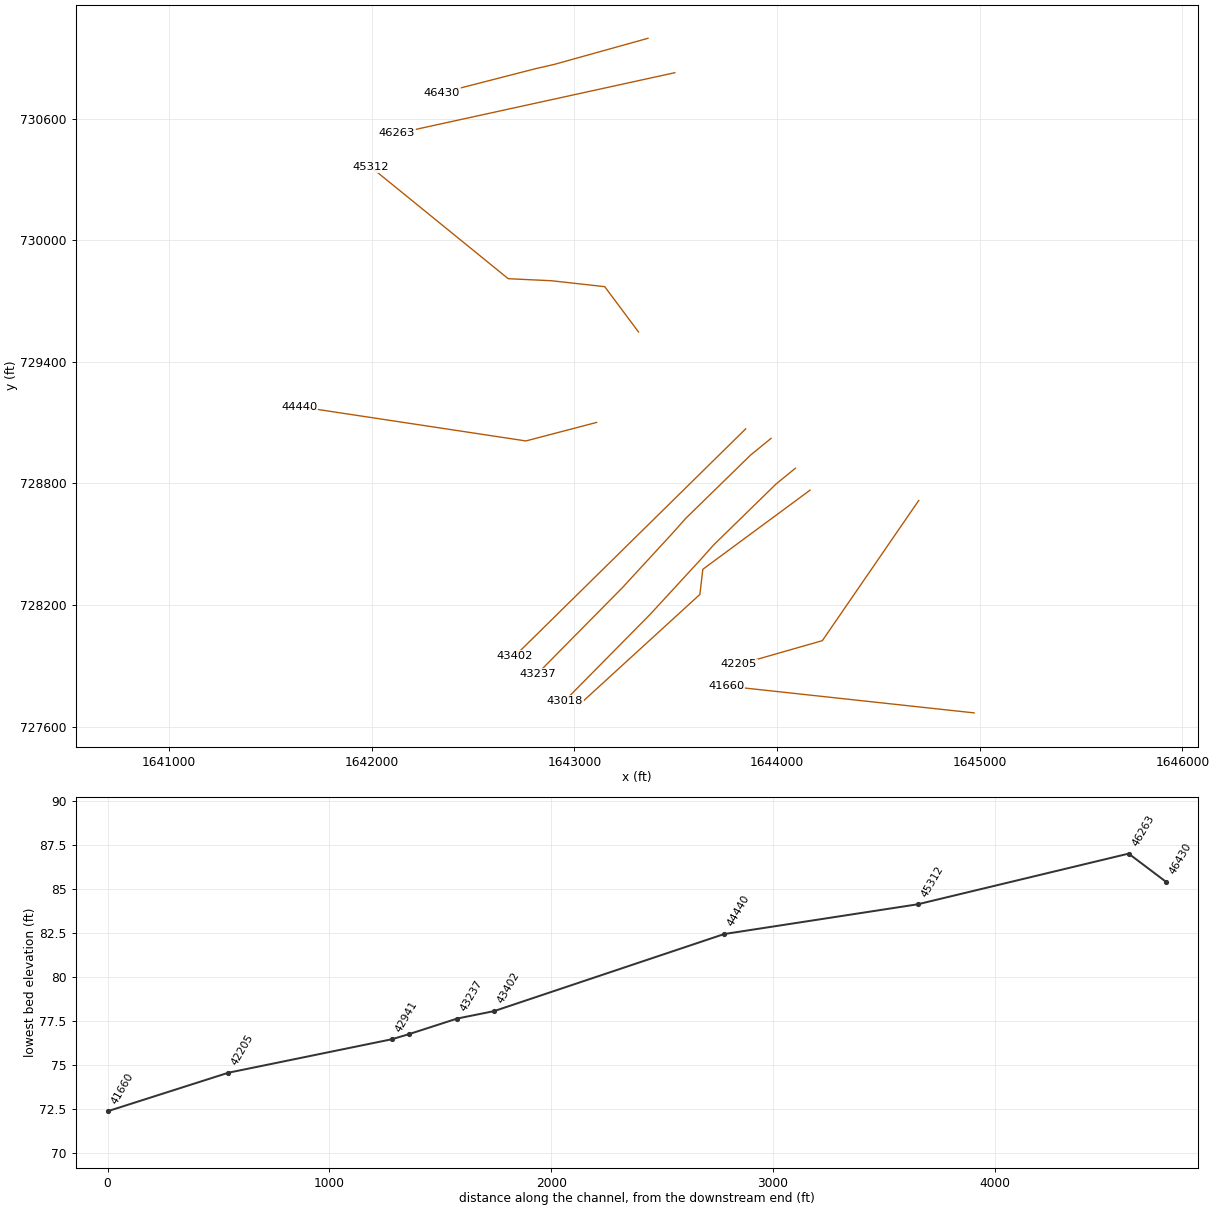
HEC-RAS study bigelkcreek.prj: Big Elk Creek

--- bigelkcreek.g23 (geometry) --- (continued)

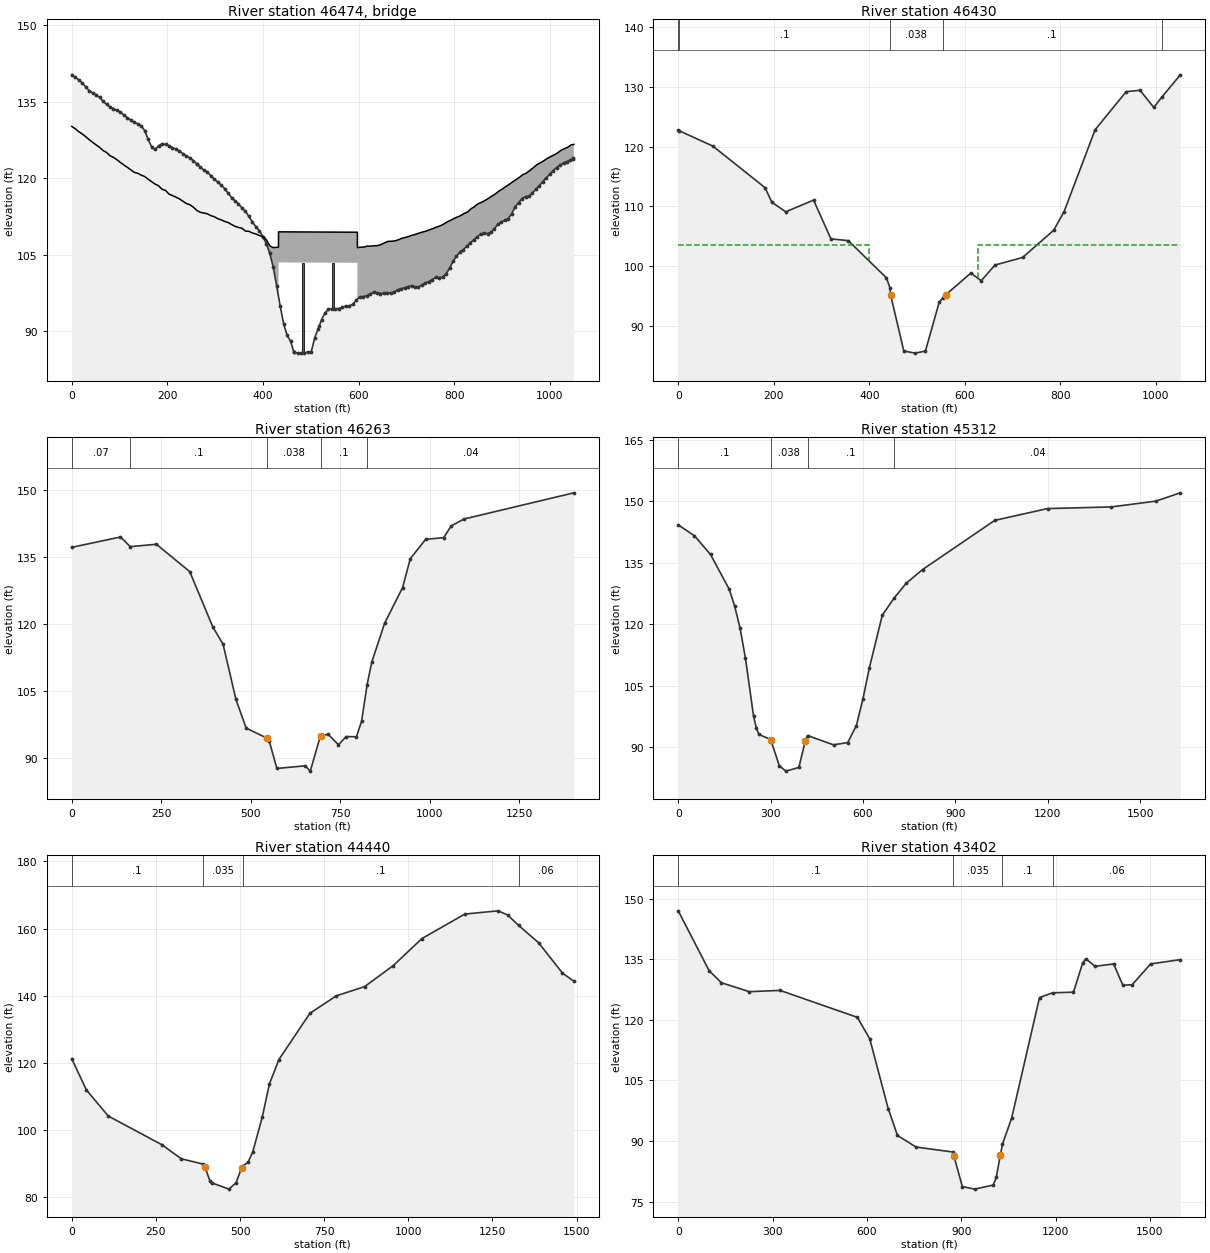
Type RM Length L Ch R = 3 ,46474   ,,,
BEGIN DESCRIPTION:
Brewster Bridge  CE050407PF-5  Aprroximate Reach
Top of road from LIDAR.
END DESCRIPTION:
Bridge Culvert--1,0,-1,-1, 0
Deck Dist Width WeirC Skew NumUp NumDn MinLoCord MaxHiCord MaxSubmerge Is_Ogee
30,37,2.6,0, 126, 126, , , 0.95, 0, 0,0,,
       0    7.27   14.53    21.8   29.06   36.33    43.6   50.86   58.13    65.4
   72.66   79.93   87.19   94.46  101.73  108.99  116.26  123.53  130.79  138.06
  145.32  152.59  159.86  167.12  174.39  181.66  188.92  196.19  203.45  210.72
  217.99  225.25  232.52  239.79  247.05  254.32  261.58  268.85  276.12  283.38
  290.65  297.92  305.18  312.45  319.71  326.98  334.25  341.51  348.78  356.05
  363.31  370.58  377.84  385.11  392.38  399.64  406.91  414.18  421.44   432.5
 432.501   597.5  597.51  603.92  611.15  618.38   625.6  632.83  640.06  647.29
  654.51  661.74  668.97   676.2  683.43  690.65  697.88  705.11  712.34  719.56
  726.79  734.02  741.25  748.48   755.7  762.93  770.16  777.39  784.61  791.84
  799.07   806.3  813.52  820.75  827.98  835.21  842.44  849.66  856.89  864.12
  871.35  878.57   885.8  893.03  900.26  907.49  914.71  921.94  929.17   936.4
  943.62  950.85  958.08  965.31  972.53  979.76  986.99  994.22 1001.45 1008.67
  1015.9 1023.13 1030.36 1037.58 1044.81 1050.32
  130.17  129.72  129.15   128.7  128.17  127.58  127.06  126.54  126.07  125.45
  125.07  124.43   124.1  123.64  123.11  122.61  122.15  121.65  121.17  120.97
  120.62  120.34  119.82  119.33  118.86  118.53  117.84  117.62  116.89  116.61
   116.3  115.96   115.5  115.04  114.81  114.34  113.69  113.33  113.19  113.04
  112.68  112.47  112.09  111.85  111.54  111.33  110.93  110.58  110.36   110.2
  109.65   109.6  109.27  109.08  108.77  108.57  107.97  106.76   106.4   106.5
   109.5  109.42   106.4  106.49   106.5  106.71  106.68  106.78   106.8  107.02
  107.36  107.63  107.65  107.73  107.94  108.24  108.39   108.6  108.84  109.03
  109.26  109.46  109.63  109.91  110.13  110.44  110.65  110.98  111.41  111.73
  112.09   112.4  112.68  113.09  113.38  114.02  114.43  114.99  115.27  115.62
  116.04  116.51  116.91  117.46  117.87  118.34  118.78  119.28  119.74  120.18
  120.72  121.01  121.53  122.05  122.64  123.01  123.41  123.88  124.23  124.58
  124.95  125.47   125.8  126.09  126.56  126.65
                                                                                
                                                                                
                                                                                
                                                                                
                                                                                
                                                                                
   103.5  103.42
                                                                                
                                                                                
                                                                                
                                                                                
                                                                                
                                                
       0    7.27   14.53    21.8   29.06   36.33    43.6   50.86   58.13    65.4
   72.66   79.93   87.19   94.46  101.73  108.99  116.26  123.53  130.79  138.06
  145.32  152.59  159.86  167.12  174.39  181.66  188.92  196.19  203.45  210.72
  217.99  225.25  232.52  239.79  247.05  254.32  261.58  268.85  276.12  283.38
  290.65  297.92  305.18  312.45  319.71  326.98  334.25  341.51  348.78  356.05
  363.31  370.58  377.84  385.11  392.38  399.64  406.91  414.18  421.44   432.5
 432.501   597.5  597.51  603.92  611.15  618.38   625.6  632.83  640.06  647.29
  654.51  661.74  668.97   676.2  683.43  690.65  697.88  705.11  712.34  719.56
  726.79  734.02  741.25  748.48   755.7  762.93  770.16  777.39  784.61  791.84
  799.07   806.3  813.52  820.75  827.98  835.21  842.44  849.66  856.89  864.12
  871.35  878.57   885.8  893.03  900.26  907.49  914.71  921.94  929.17   936.4
  943.62  950.85  958.08  965.31  972.53  979.76  986.99  994.22 1001.45 1008.67
  1015.9 1023.13 1030.36 1037.58 1044.81 1050.32
  130.17  129.72  129.15   128.7  128.17  127.58  127.06  126.54  126.07  125.45
  125.07  124.43   124.1  123.64  123.11  122.61  122.15  121.65  121.17  120.97
  120.62  120.34  119.82  119.33  118.86  118.53  117.84  117.62  116.89  116.61
   116.3  115.96   115.5  115.04  114.81  114.34  113.69  113.33  113.19  113.04
  112.68  112.47  112.09  111.85  111.54  111.33  110.93  110.58  110.36   110.2
  109.65   109.6  109.27  109.08  108.77  108.57  107.97  106.76   106.4   106.5
   109.5  109.42   106.4  106.49   106.5  106.71  106.68  106.78   106.8  107.02
  107.36  107.63  107.65  107.73  107.94  108.24  108.39   108.6  108.84  109.03
  109.26  109.46  109.63  109.91  110.13  110.44  110.65  110.98  111.41  111.73
  112.09   112.4  112.68  113.09  113.38  114.02  114.43  114.99  115.27  115.62
  116.04  116.51  116.91  117.46  117.87  118.34  118.78  119.28  119.74  120.18
  120.72  121.01  121.53  122.05  122.64  123.01  123.41  123.88  124.23  124.58
  124.95  125.47   125.8  126.09  126.56  126.65
                                                                                
                                                                                
                                                                                
                                                                                
                                                                                
                                                                                
   103.5  103.42
                                                                                
                                                                                
                                                                                
                                                                                
                                                                                
                                                
Pier Skew, UpSta & Num, DnSta & Num=  ,483.75, 2 ,483.75, 2 , 0 , 0 , 0 ,,
     2.5     2.5
       0     105
     2.5     2.5
       0     105
Pier Skew, UpSta & Num, DnSta & Num=  ,546.25, 2 ,546.25, 2 , 0 , 0 , 0 ,,
       3       3
       0     105
       3       3
       0     105
BR Coef=-1 , 1 , 0 ,, 0 ,,,0.8,0,0.5,0,
WSPro=,,,, 1 ,,,, 0 ,,,, 0 ,,,,-1 ,-1 ,-1 , 0 , 0 , 0 , 0 , 0
BR U #Sta/Elev= 150
       0  140.29    7.27  139.78   14.53  139.34    21.8  138.68   29.06  137.95
   36.33  137.18    43.6  136.75   50.86  136.37   58.13  135.87    65.4  135.13
   72.66   134.5   79.93     134   87.19  133.64   94.46   133.3  101.73  132.99
  108.99   132.4  116.26  131.89  123.53   131.4  130.79  130.95  138.06   130.7
  145.32  130.29  152.59  129.35  159.86  127.62  167.12  126.14  174.39  125.65
  181.66  126.39  188.92  126.77  196.19  126.63  203.45  126.41  210.72  126.02
  217.99  125.72  225.25  125.35  232.52  124.81  239.79  124.35  247.05  124.03
  254.32  123.46  261.58  122.81  262.46  122.74  268.85  122.18  276.12  121.62
  283.38  121.26  290.65  120.54  297.92  119.86  305.18  119.29  312.45  118.68
  319.71  117.99  326.98  117.11  334.25  116.21  341.51  115.57  348.78  114.95
  356.05   114.2  363.31   113.5  370.58  112.51  377.84  111.42  385.11  110.52
  392.38  109.71  399.64  108.56  406.91  107.19  414.18  105.27  421.44  102.57
  428.71   98.85  435.97   94.94  443.24   91.44  450.51   89.19  457.77   88.06
  464.68   85.85  465.04   85.84  472.31   85.71  479.52   85.77   486.7   85.78
  493.88   85.92  501.06   85.99  508.24   88.71  515.42   90.45  517.89   91.09
   522.6   92.29  529.78   93.61  536.96   94.28  544.14   94.44  551.32   94.41
   558.5   94.46  565.68   94.66  573.51   94.97  580.74   94.97  587.97   95.31
  595.19   96.07  602.42   96.75  609.65   96.79  616.88   96.95   624.1   97.27
  631.33   97.61  638.56    97.5  645.79    97.4  653.01   97.43  660.24   97.52
  667.47   97.47   674.7    97.7  681.93   98.13  689.15   98.35  696.38   98.51
  703.61   98.75  710.84   98.93  718.06   98.62  725.29   98.69  732.52   99.03
  739.75   99.48  746.97   99.72   754.2  100.13  761.43  100.55  768.66  100.52
  775.89   100.6  783.11  101.25  790.34  102.35  797.57  103.68   804.8  104.72
  812.02  105.49  819.25  106.01  826.48  106.66  833.71  107.34  840.94   107.9
  848.16  108.53  855.39  109.09  862.62  109.22  869.85  109.16  877.07  109.41
   884.3  110.12  891.53  110.99  898.76  111.45  905.98  111.75  913.21  112.09
  920.44  113.06  927.67   114.4   934.9  115.25  942.12  116.01  949.35  116.41
  956.58  116.48  963.81  117.11  971.03  117.86  978.26  118.54  985.49  119.36
  992.72  120.08  999.95  120.78 1007.17  121.52  1014.4  122.11 1021.63  122.54
 1028.86  123.01 1036.08  123.28 1043.31  123.55 1047.85   123.8 1049.42  123.89
BR U #Mann= 5
       0     .07  262.46      .1  435.97     .04  529.78      .1 1047.85     .08
BR D #Sta/Elev= 151
       0  122.77    1.68   122.7    7.27  122.46   14.53  122.09    21.8  121.64
   29.06  121.28   36.33  120.89    43.6  120.87   50.86  121.04   58.13  120.94
    65.4  120.53   72.66  120.11   79.93   119.6   87.19  118.75   94.46  118.52
  101.73  118.14  108.99  117.53  116.26  116.59  123.53     116  130.79  115.83
  138.06  115.75  145.32  115.53  152.59  114.95  159.86  113.97  167.12  113.54
  174.39  113.63  181.66  113.16  188.92  112.12  196.19  110.69  203.45  110.22
  210.72  109.91  217.99  109.48  225.25  109.11  232.52  109.07  239.79  109.11
  247.05  109.41  254.32  110.08  261.58  110.64  268.85     111  276.12  111.31
  283.38  111.07  290.65  109.62  297.92  108.07  305.18  107.02  312.45  105.75
  319.71  104.57  326.98  104.47  334.25  104.53  341.51  104.79  348.78  104.69
  356.05  104.28  363.31  103.41  370.58  102.93  377.84  102.54  385.11  102.17
  392.38  101.66  399.64  100.53  406.91  100.36  414.18   99.73  421.44   99.22
  428.71   98.62  435.97   98.04  443.24   96.38  444.76   95.14  450.51    93.4
  457.77   90.64  465.04   88.56  472.31   85.79  481.62   85.67  487.97   85.57
   488.8   85.55  495.98   85.43  503.16   85.51  510.35   85.55  517.53   85.78
  524.71   88.32  531.89   89.68   537.9   91.74  539.07   92.14  546.25   93.92
  553.43   94.63  560.61   95.24  567.79   95.67  576.51   96.24  583.74   96.97
  590.97   97.81  598.19   98.23  605.42   98.46  612.65   98.84  619.88   98.56
   627.1   97.84  634.33   97.57  641.56    97.8  648.79   98.59  656.02   99.56
  663.24  100.19  670.47  100.24   677.7  100.47  684.93  100.44  692.15  100.23
  699.38  100.48  706.61  100.96  713.84  101.22  721.06  101.46  728.29  102.07
  735.52  102.43  742.75  102.64  749.98  103.22   757.2  103.84  764.43  104.35
  771.66   104.9  778.89  105.49  786.11  106.02  793.34  106.86  800.57   107.9
   807.8  109.13  815.03  110.97  822.25  112.55  829.48  113.89  836.71  115.42
  843.94  116.93  851.16  118.73  858.39  120.23  865.62  121.57  872.85  122.86
  880.07  123.96   887.3  124.84  894.53   125.6  901.76  126.32  908.99  127.01
  916.21  127.52  923.44  128.15  930.67  128.62   937.9  129.24  945.12  129.35
  952.35   129.3  959.58  129.51  966.81  129.47  974.03  128.58  981.26  127.42
  988.49  126.71  995.72   126.6 1002.95  127.29 1010.17  128.12 1012.42  128.32
  1017.4  128.75 1024.63   129.4 1031.86  130.11 1039.08  130.77 1046.31  131.76
 1051.21  132.06
BR D #Mann= 5
       0     .07    1.68      .1  443.24    .035  553.43      .1 1012.42     .04
BC Design=,, 0 ,, 0 ,,,,,,
BC Use User HTab Curves=0
BC User HTab FreeFlow(D)= 0

Type RM Length L Ch R = 1 ,46430   ,174.81,167.36,164.87
BEGIN DESCRIPTION:
Modified under water portion by 2 feet as per "flow depth" in bridge inspection notes.
END DESCRIPTION:
XS GIS Cut Line= 4
1643363.10899192730996.5286644551642899.13261941730867.353424415
1642806.63106059730846.2102109491642346.88815755730727.990607336
#Sta/Elev= 30
       0  122.77    1.68   122.7   72.66  120.11  181.66  113.16  196.19  110.69
  225.25  109.11  283.38  111.07  319.71  104.57  356.05  104.28  435.97   98.04
  443.24   96.38  444.76   95.14  472.31   85.79  495.98   85.43  517.53   85.78
  546.25   93.92  553.43   94.63  560.61   95.24  612.65   98.84  634.33   97.57
  663.24  100.19  721.06  101.46  786.11  106.02   807.8  109.13  872.85  122.86
   937.9  129.24  966.81  129.47  995.72   126.6 1012.42  128.32 1051.21  132.06
#Mann= 5 ,-1 , 0
       0     .07       0    1.68      .1       0  443.24    .038       0
  553.43      .1       0 1012.42     .04       0
#XS Ineff= 2 ,-1
       0     400   103.5     627 1051.21   103.5
Permanent Ineff=
       F       F
Bank Sta=444.76,560.61
XS Rating Curve= 0 ,0
Exp/Cntr=0.5,0.3

Type RM Length L Ch R = 1 ,46263   ,977.99,951.28,898.72
XS GIS Cut Line= 2
1643495.71501805730826.8124896141642125.24435705730526.939830601
#Sta/Elev= 30
       0  137.14  136.15  139.46  163.44   137.3  236.47  137.83  329.62  131.71
  394.11  119.31  422.77  115.45   458.6   103.1  487.26   96.66  544.59   94.44
  551.75   93.77  573.25   87.62  652.07   88.21   666.4   87.02  695.06   94.98
  716.56   95.26  745.22   92.92  766.72   94.76  795.38   94.72  809.71   98.14
  825.32  106.41  838.38  111.47   874.2  120.15  924.36  128.13  945.86   134.6
  988.85  138.93 1039.01  139.31 1060.51  141.96 1096.34  143.49  1402.9  149.35
#Mann= 5 ,-1 , 0
       0     .07       0  163.44      .1       0  544.59    .038       0
  695.06      .1       0  825.32     .04       0
Bank Sta=544.59,695.06
XS Rating Curve= 0 ,0
Exp/Cntr=0.3,0.1

Type RM Length L Ch R = 1 ,45312   ,844.56,871.96,858.09
XS GIS Cut Line= 5
1643316.63083868729547.436584964 1643149.9236427729771.024750933
1642887.02921477729800.2352429031642673.66562115729810.395414039
1641996.06661172730360.933332503
#Sta/Elev= 30
       0  144.18   52.39  141.54  104.78  136.97   165.9  128.44  183.36  124.32
  200.83  118.97  218.29  111.64  244.48   97.58  253.22   94.74  261.95   93.08
  300.03   91.85   328.2   85.45  349.33   84.14  391.59   85.03  412.71   91.58
  419.76   92.82  504.27   90.55  550.42   91.11  578.45   95.26  599.47  101.68
   620.5  109.32  662.54  122.17  701.75  126.42  739.63   129.9  793.09  133.29
 1027.59  145.28 1198.96  148.16  1406.4  148.56  1550.7  149.98 1630.07     152
#Mann= 4 ,-1 , 0
       0      .1       0  300.03    .038       0  419.76      .1       0
  701.75     .04       0
Bank Sta=300.03,412.71
XS Rating Curve= 0 ,0
Exp/Cntr=0.3,0.1

Type RM Length L Ch R = 1 ,44440   ,843,1037.49,1091.14
XS GIS Cut Line= 3
1643109.59194809729101.0671785471642760.68641628729009.776483849
1641642.21376638729178.991869703
#Sta/Elev= 30
       0  121.27   43.41  111.98  108.53  104.21  267.72   95.67   325.6   91.47
  388.97   89.94  396.05   88.94  410.21   84.97  417.29   84.29  466.85   82.45
  488.08   84.34  504.74   88.79  509.32   89.42  523.48    90.4  537.64   93.48
  565.96  103.87   587.2  113.74  615.52  121.03  707.55  134.79  785.43  139.97
  870.39  142.76  955.34  149.01  1040.3  157.05 1167.73  164.34 1266.85  165.31
 1295.17  164.06 1327.75  160.97  1387.2   155.8    1458  146.78 1491.85  144.35
#Mann= 4 ,-1 , 0
       0      .1       0  388.97    .035       0  509.32      .1       0
 1327.75     .06       0
Bank Sta=396.05,504.74
XS Rating Curve= 0 ,0
Exp/Cntr=0.3,0.1

Type RM Length L Ch R = 1 ,43402   ,132.93,165.49,175.68
XS GIS Cut Line= 2
1643845.58612295729069.5528453741642707.42026992727949.626829728
#Sta/Elev= 30
       0  147.06    98.2  132.22  137.49  129.23  225.87  127.02  324.08  127.33
  569.59  120.66  608.87  115.39  667.79   98.03  697.26   91.37  756.18   88.51
  874.02   87.26  876.46   86.36  903.49   78.71  942.77   78.07 1001.69   79.08
 1011.51      81  1024.4   86.49 1031.15   89.19 1060.61   95.75    1149  125.57
 1190.55  126.74 1257.02   126.9 1286.48  134.21  1296.3  135.17 1325.77  133.31
 1384.69  133.89 1414.15   128.6 1443.61  128.75 1502.53  133.91 1596.76  134.96
#Mann= 4 ,-1 , 0
       0      .1       0  874.02    .035       0 1031.15      .1       0
 1190.55     .06       0
Bank Sta=876.46,1024.4
XS Rating Curve= 0 ,0
Exp/Cntr=0.5,0.3

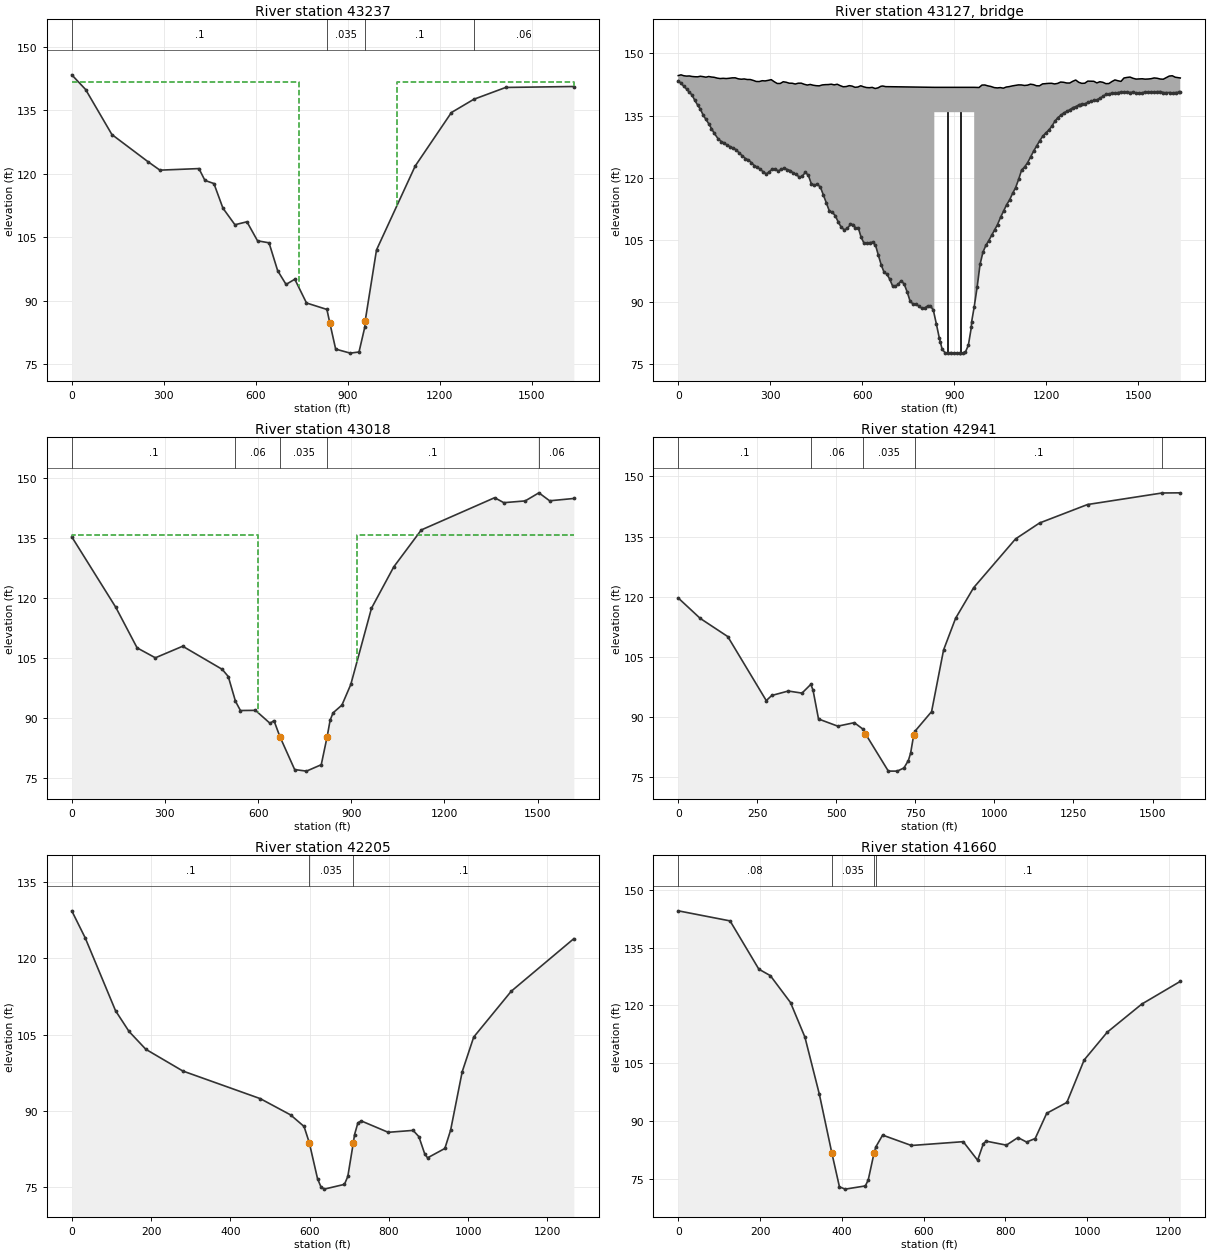
Type RM Length L Ch R = 1 ,43237   ,234.17,218.46,217.03
XS GIS Cut Line= 6
1643970.64432852729022.3608273421643869.18824179  728939.6929048
1643549.63594373 728627.644406811643481.58174554728551.423704863
 1643236.8616028728285.5355421161642818.05383325727861.458059132
#Sta/Elev= 30
       0   143.4   45.15  139.93  130.87  129.29  248.28  122.89  287.41  120.88
  414.61  121.25  434.17  118.46  463.53  117.71  492.88   111.9  532.01  107.98
  571.15  108.68  605.66  104.19   643.2  103.71  671.35   97.12  698.72   93.88
  727.26   95.11  765.32    89.5  831.91   87.97  841.42   84.78  860.45    78.6
  908.02   77.65  936.56   77.92  955.59   83.84  956.64   85.21  993.64  102.03
 1119.76  121.85 1237.82  134.49 1310.81  137.62 1414.91  140.42 1637.08  140.64
#Mann= 4 ,-1 , 0
       0      .1       0  831.91    .035       0  955.59      .1       0
 1310.81     .06       0
#XS Ineff= 2 ,-1
       0     740   141.8    1060 1637.08  141.66
Permanent Ineff=
       F       F
Bank Sta=841.42,956.64
XS Rating Curve= 0 ,0
Exp/Cntr=0.5,0.3

Type RM Length L Ch R = 3 ,43127   ,,,
BEGIN DESCRIPTION:
Chessie System RR.  CE050807FS-6  Inaccessible. Approximate Reach.   No Survey  Top of road from LIDAR.
Span estimated as 130' from aerial photograph.  Span is approx 130'  Added 2 - 3' piers as per study guidance.
END DESCRIPTION:
Bridge Culvert--1,0,-1,-1, 0
Deck Dist Width WeirC Skew NumUp NumDn MinLoCord MaxHiCord MaxSubmerge Is_Ogee
95,30,2.6,0, 143, 143, , , 0.95, 0, 0,0,,
       0    9.03   18.06   27.09   36.12   45.15   54.18   63.21   72.24   81.27
    90.3   99.32  108.35  117.38  127.05  136.84  146.62   156.4  166.19  175.97
  185.76  195.54  205.32  215.11  224.89  234.68  244.46  254.24  264.03  273.81
   283.6  293.38  303.16  312.95  322.73  332.52   342.3  352.08  361.87  371.65
  381.43  391.22     401  410.79  420.57  430.35  440.14  449.92  459.71  469.49
  479.27  489.06  498.84  508.63  518.41  528.19  537.98  547.76  557.55  566.96
  576.35  585.73  595.12   604.5  613.89  623.27  632.65  642.04  651.42  660.81
  666.88  676.39  834.99     835     965  965.01  980.83  990.34  999.85 1009.37
 1018.88 1030.38 1040.22 1050.06  1059.9 1069.73 1079.57 1089.41 1099.25 1109.09
 1118.92 1128.76  1138.6 1148.44 1158.28 1168.11 1177.95 1187.79 1197.63 1207.47
 1217.31 1227.14 1236.98 1246.82 1256.66  1266.5 1276.33 1286.17 1296.01 1305.85
 1315.69 1325.53 1335.36  1345.2 1355.04 1364.88 1374.72 1384.55 1394.39 1404.23
 1414.07 1423.91 1433.74 1443.58 1453.42 1463.26  1473.1 1482.94 1492.77 1502.61
 1512.45 1522.29 1532.13 1541.96  1551.8 1561.64 1571.48 1581.32 1591.15 1600.99
 1610.83 1620.67 1637.08
  144.64  144.82   144.6  144.51  144.55  144.42  144.36  144.34  144.48  144.38
  144.25  144.42  144.29  144.22  144.03  143.92  143.98  143.92  143.99  144.09
   144.1  143.86  143.76  143.83  143.69  143.69  143.48  143.22   143.2   143.4
  143.35  143.49  143.66  143.16  142.73  142.73  143.15  143.03   142.8  142.79
   142.6   142.8  142.81  142.54  142.35   142.5  142.31   142.2  142.16  142.38
  142.45  142.47  142.56   142.4  142.55  142.21  141.94  141.99  142.21   142.1
  141.81  141.88  142.18  141.93  141.75  141.71  141.79  141.52  141.68  142.06
  142.12  141.97   141.8   141.8   141.8   141.8  141.76  142.35  142.37  142.16
  142.02  141.74  141.66  141.74   141.6  141.88  141.98  142.15  142.27  142.39
  142.38  142.25  142.32  142.56  142.45  142.18  142.17  142.63   142.7  142.76
  142.78  142.62  142.75  143.08  143.02  142.85  142.84  143.25  143.57  143.02
  142.76   142.8   143.3  143.29  143.26  142.87  143.15  143.02  142.69  142.72
   143.2  143.59  143.39  143.23  144.06  144.19  144.28  143.99  143.79  143.83
  143.87  143.78  143.81  143.89  144.07  143.99  143.81  143.76  144.14  144.52
   144.6  144.24  144.06
                                                                                
                                                                                
                                                                                
                                                                                
                                                                                
                                                                                
                                                                                
                           135.8   135.8
                                                                                
                                                                                
                                                                                
                                                                                
                                                                                
                                                                                
                        
       0    9.03   18.06   27.09   36.12   45.15   54.18   63.21   72.24   81.27
    90.3   99.32  108.35  117.38  127.05  136.84  146.62   156.4  166.19  175.97
  185.76  195.54  205.32  215.11  224.89  234.68  244.46  254.24  264.03  273.81
   283.6  293.38  303.16  312.95  322.73  332.52   342.3  352.08  361.87  371.65
  381.43  391.22     401  410.79  420.57  430.35  440.14  449.92  459.71  469.49
  479.27  489.06  498.84  508.63  518.41  528.19  537.98  547.76  557.55  566.96
  576.35  585.73  595.12   604.5  613.89  623.27  632.65  642.04  651.42  660.81
  666.88  676.39     693 693.001     823   823.1  980.83  990.34  999.85 1009.37
 1018.88 1030.38 1040.22 1050.06  1059.9 1069.73 1079.57 1089.41 1099.25 1109.09
 1118.92 1128.76  1138.6 1148.44 1158.28 1168.11 1177.95 1187.79 1197.63 1207.47
 1217.31 1227.14 1236.98 1246.82 1256.66  1266.5 1276.33 1286.17 1296.01 1305.85
 1315.69 1325.53 1335.36  1345.2 1355.04 1364.88 1374.72 1384.55 1394.39 1404.23
 1414.07 1423.91 1433.74 1443.58 1453.42 1463.26  1473.1 1482.94 1492.77 1502.61
 1512.45 1522.29 1532.13 1541.96  1551.8 1561.64 1571.48 1581.32 1591.15 1600.99
 1610.83 1620.67  1627.9
  144.64  144.82   144.6  144.51  144.55  144.42  144.36  144.34  144.48  144.38
  144.25  144.42  144.29  144.22  144.03  143.92  143.98  143.92  143.99  144.09
   144.1  143.86  143.76  143.83  143.69  143.69  143.48  143.22   143.2   143.4
  143.35  143.49  143.66  143.16  142.73  142.73  143.15  143.03   142.8  142.79
   142.6   142.8  142.81  142.54  142.35   142.5  142.31   142.2  142.16  142.38
  142.45  142.47  142.56   142.4  142.55  142.21  141.94  141.99  142.21   142.1
  141.81  141.88  142.18  141.93  141.75  141.71  141.79  141.52  141.68  142.06
  142.12  141.97   141.8   141.8   141.8   141.8  141.76  142.35  142.37  142.16
  142.02  141.74  141.66  141.74   141.6  141.88  141.98  142.15  142.27  142.39
  142.38  142.25  142.32  142.56  142.45  142.18  142.17  142.63   142.7  142.76
  142.78  142.62  142.75  143.08  143.02  142.85  142.84  143.25  143.57  143.02
  142.76   142.8   143.3  143.29  143.26  142.87  143.15  143.02  142.69  142.72
   143.2  143.59  143.39  143.23  144.06  144.19  144.28  143.99  143.79  143.83
  143.87  143.78  143.81  143.89  144.07  143.99  143.81  143.76  144.14  144.52
   144.6  144.24  144.06
                                                                                
                                                                                
                                                                                
                                                                                
                                                                                
                                                                                
                                                                                
                           135.8   135.8
                                                                                
                                                                                
                                                                                
                                                                                
                                                                                
                                                                                
                        
Pier Skew, UpSta & Num, DnSta & Num=  ,878, 2 ,736, 2 , 0 , 0 , 0 ,,
       3       3
       0     137
       3       3
       0     137
Pier Skew, UpSta & Num, DnSta & Num=  ,921, 2 ,779, 2 , 0 , 0 , 0 ,,
       3       3
       0     137
       3       3
       0     137
BR Coef=-1 , 1 , 0 ,, 0 ,,,0.8,-1,0.5,0,
WSPro=,,,, 1 ,,,, 0 ,,,, 0 ,,,,-1 ,-1 ,-1 , 0 , 0 , 0 , 0 , 0
BR U #Sta/Elev= 175
       0   143.4    9.03  142.75   18.06  142.09   27.09   141.4   36.12  140.63
   45.15  139.93   54.18  138.63   63.21  137.53   72.24  136.53   81.27  135.09
    90.3  134.08   99.32  133.03  108.35  131.85  117.38   130.7  130.87  129.29
  140.66  128.71  150.44  128.33  160.22  127.77  170.01  127.46  179.79  127.07
  189.58  126.71  199.36  125.88  209.14  125.26  218.93  124.62  228.71  124.28
  238.49  123.61  248.28  122.89  258.06   122.5  267.85  121.98  277.63  121.38
  287.41  120.88   297.2  121.46  306.98  122.02  316.77     122  326.55   121.6
  336.33  122.03  346.12  122.27   355.9  121.95  365.69  121.69  375.47  121.06
  385.25  120.79  395.04  120.06  404.82  120.41  414.61  121.25  424.39  120.55
  434.17  118.46  443.96  118.25  453.74  118.37  463.53  117.71  473.31   115.8
  483.09  113.87  492.88   111.9  502.66  111.66  512.45  110.75  522.23  109.21
  532.01  107.98   541.8  107.38  551.58  107.73  561.37   108.7  571.15  108.68
  577.51  107.88   586.9  107.92  596.28  105.63  605.66  104.19  615.05  104.15
  624.43  104.31  633.82  104.41   643.2  103.71  652.59  101.25  661.97   98.92
  671.35   97.12  679.69   96.75  689.21   95.55  698.72   93.88  708.23   93.74
  717.75   94.32  727.26   95.11  736.77   94.29  746.29   92.46   755.8   90.24
  765.32    89.5  774.83    89.5  784.34      89  793.86   88.51  803.37   88.52
  812.88   89.02   822.4   89.06  831.91   87.97  841.42   84.78  850.94    81.4
  854.39   80.38  860.45    78.6  869.97   77.75  879.48   77.71  888.99   77.77
  898.51   77.67  908.02   77.65  917.53   77.71  917.91   77.71  927.05   77.67
  936.56   77.92  946.07   79.59  955.59   83.84  956.64   85.21   965.1   88.84
  974.62   93.57  984.13   99.07  993.64  102.03 1003.16  103.65 1012.67  104.82
 1022.18  106.12  1031.7  107.37 1041.06  108.67  1050.9   110.4 1060.73  111.94
 1070.57  113.43 1080.41  114.63 1090.25  116.18 1100.09   117.6 1109.93  119.59
 1119.76  121.85  1129.6   122.6 1139.44  123.65 1149.28  125.06 1159.12  126.44
 1168.95  127.69 1178.79  128.92 1188.63     130 1198.47  130.78 1208.31  131.48
 1218.14  132.41 1227.98  133.58 1237.82  134.49 1247.66  135.05  1257.5  135.66
 1267.34  135.98 1277.17  136.41 1287.01   136.9 1296.85  137.17 1306.69  137.58
 1310.81  137.62 1316.53  137.67 1326.36  137.82  1336.2  138.18 1346.04  138.41
 1355.88  138.67 1365.72  138.81 1375.55   139.2 1385.39  139.63 1395.23  140.13
 1405.07   140.2 1414.91  140.42 1424.75  140.34 1434.58  140.55 1444.42  140.67
 1454.26  140.69  1464.1  140.68 1473.94  140.53 1483.77  140.66 1493.61  140.44
 1503.45  140.33 1513.29  140.47 1523.13  140.71 1532.97  140.68  1542.8  140.71
 1552.64  140.62 1562.48  140.75 1572.32  140.78 1582.16  140.53 1591.99  140.51
 1601.83  140.55 1611.67  140.44 1621.51  140.54 1631.35  140.58 1637.08  140.64
BR U #Mann= 4
       0      .1  831.91    .032  955.59      .1 1310.81     .06
BR D #Sta/Elev= 173
       0  135.29    9.03  134.38   18.06  133.12   27.09  131.91   36.12  130.54
   45.15  129.41   54.18  128.62   63.21  127.63   72.24   126.4   81.27  125.21
    90.3  124.02   99.32  122.94  108.35  121.88  117.38  120.64  122.33  119.98
  132.12  118.93   141.9  117.66  151.69  116.09  161.47  114.33  171.25  112.67
  181.04  111.11  190.82  109.76  200.61  108.44  210.39  107.55  220.17  106.96
  229.96  106.51  239.74  106.18  249.53  105.39  259.31  105.11  269.09  105.07
  278.88  105.37  288.66  106.15  298.45  106.88  308.23  107.28  318.01  107.59
   327.8  107.71  337.58  107.75  347.36  107.96  357.15  107.96  366.93  107.28
  376.72  107.13   386.5  106.55  396.28  105.82  406.07  105.64  415.85   104.8
  425.64  104.28  435.42  103.79   445.2  103.44  454.99  103.25  464.77  103.02
  474.56  102.54  484.34  102.19  494.12  101.23  503.91  100.39  513.69    98.5
  523.48   95.19     527   94.23  533.26   92.51  543.04    91.9  553.93   92.61
  563.32   91.68   572.7   91.46  582.09   91.46  591.47   91.94  600.86   91.33
  610.24   91.18  619.62   90.45  629.01   89.22  638.39    88.7  651.05   89.38
  660.56    87.6  670.08   85.38  679.59   84.16   689.1   82.91  696.25   81.35
  698.62   80.83  708.13    78.6  717.64   77.15   718.4   77.13  727.16   76.86
  736.67   76.92  746.18   76.78   755.7   76.76  765.21   76.99  774.73   76.99
  781.28   77.04  784.24   77.06  793.75   77.41  803.27   78.36  812.78   81.49
  822.29   85.38  831.81   89.48  841.32   91.32  850.83   91.63  860.35   92.13
  869.86   93.26  879.37   94.75  888.89    96.6   898.4   98.41  907.92  100.72
  917.43  103.27  926.94  105.85  936.46  109.12  945.97  111.99  955.48  115.07
     965  117.45  974.51  119.03  984.02  120.15  993.54  121.39 1003.05  122.96
 1017.19  124.88 1027.03  126.12 1036.87   127.8 1046.71  128.99 1056.54     130
 1066.38  130.94 1076.22   132.1 1086.06  133.32  1095.9   134.2 1105.73  135.16
 1115.57  135.98 1125.41  137.01 1135.25  137.86 1145.09  138.19 1154.93  138.33
 1164.76  138.46  1174.6  139.09 1184.44  139.37 1194.28  139.57 1204.12  139.86
 1213.95  139.92 1223.79  140.31 1233.63   140.8 1243.47  141.26 1253.31  141.43
 1263.14  141.15 1272.98  141.63 1282.82  142.27 1292.66  142.72  1302.5  143.01
 1312.34  143.32 1322.17  143.53 1332.01  143.83 1341.85  143.89 1351.69  143.73
 1361.53  145.06 1371.36  145.19  1381.2  144.07 1391.04  143.82 1400.88  143.95
 1410.72  144.08 1420.55  144.64 1430.39  145.07 1440.23  144.59 1450.07  144.29
 1459.91  144.26 1469.75  144.44 1479.58  144.75 1489.42  144.86 1499.26   146.1
 1504.04  146.28  1509.1  146.47 1518.94  145.62 1528.77  144.64 1538.61  144.29
 1548.45   144.4 1558.29  144.41 1568.13  144.43 1577.97  144.56  1587.8  144.74
 1597.64  144.48 1607.48  144.76 1616.55  144.87
BR D #Mann= 5
       0      .1     527     .06  670.08    .032  822.29      .1 1504.04     .06
BC Design=,, 0 ,, 0 ,,,,,,
BC Use User HTab Curves=0
BC User HTab FreeFlow(D)= 0

Type RM Length L Ch R = 1 ,43018   ,86.47,77.57,136.58
XS GIS Cut Line= 6
1644090.66218925 728875.066180141643995.82472983728797.791213155
1643687.03315328728496.2507509291643622.35380723728423.809883326
1643374.39790533728154.4060718721642953.24143675727727.950337097
#Sta/Elev= 30
       0  135.29   141.9  117.66  210.39  107.55  269.09  105.07  357.15  107.96
  484.34  102.19  503.91  100.39     527   94.23  543.04    91.9  591.47   91.94
  638.39    88.7  651.05   89.38  670.08   85.38  717.64   77.15   755.7   76.76
  803.27   78.36  822.29   85.38  831.81   89.48  841.32   91.32  869.86   93.26
   898.4   98.41     965  117.45 1036.87   127.8 1125.41  137.01 1361.53  145.06
 1391.04  143.82 1459.91  144.26 1504.04  146.28 1538.61  144.29 1616.55  144.87
#Mann= 5 ,-1 , 0
       0      .1       0     527     .06       0  670.08    .035       0
  822.29      .1       0 1504.04     .06       0
#XS Ineff= 2 , 0
       0     600   135.8     918       0   135.8
Permanent Ineff=
       F       F
Bank Sta=670.08,822.29
XS Rating Curve= 0 ,0
Exp/Cntr=0.5,0.3

Type RM Length L Ch R = 1 ,42941   ,703.46,736.02,672.53
XS GIS Cut Line= 4
1644162.95929351 728766.771544741643634.00400925728376.439024597
1643619.41213933728252.4081303781643024.79344048727708.860976204
#Sta/Elev= 30
       0  119.68    69.6  114.58  156.59  110.05  278.39   94.07  295.79   95.35
  347.98   96.46  391.48   95.94  419.36   98.13  426.28   96.69  443.68   89.48
  504.58   87.69  556.77   88.56  582.87   87.03  591.57   85.85  664.43   76.48
  692.63   76.47  713.77   77.26  727.87   79.12  734.92   80.95  744.68   85.46
  749.01   86.45  801.24   91.32  839.17  106.71  877.11   114.6  934.01  122.22
 1066.79  134.42 1142.66  138.39  1294.4     143 1530.24  145.88 1587.88  145.92
#Mann= 5 ,-1 , 0
       0      .1       0  419.36     .06       0  582.87    .035       0
  749.01      .1       0 1530.24     .06       0
Bank Sta=591.57,744.68
XS Rating Curve= 0 ,0
Exp/Cntr=0.3,0.1

Type RM Length L Ch R = 1 ,42205   ,631.03,544.53,309.9
XS GIS Cut Line= 3
1644699.37944548728716.138245806 1644223.7234019 728024.35667111
1643812.82051973727906.671400592
#Sta/Elev= 30
       0  129.38   33.98  124.04  110.44  109.71  144.42  105.63  186.89  102.11
  280.34   97.83  475.72   92.39  552.18   89.19  586.16   86.91  599.38   83.71
  620.14   76.64  628.63   75.04  637.13   74.57   688.1   75.51  696.59   77.08
  710.33   83.61  713.58   85.31  722.08   87.63  730.57      88  798.53   85.76
  861.37   86.14  875.94    84.9   890.5   81.55  897.78   80.73  941.47   82.58
  956.03   86.19  985.16   97.67 1014.28  104.52 1108.94  113.54 1266.96   123.9
#Mann= 3 , 0 , 0
       0      .1       0  599.38    .035       0  710.33      .1       0
Bank Sta=599.38,710.33
XS Rating Curve= 0 ,0
Exp/Cntr=0.3,0.1

Type RM Length L Ch R = 1 ,41660   ,576.98,540.4,327.22
XS GIS Cut Line= 2
1644972.54583722727667.8637386261643751.70306414727800.192850396
#Sta/Elev= 30
       0  144.51  126.74   141.9  197.15  129.39  225.31  127.71   274.6  120.74
   309.8  111.79  345.01   97.04  375.69   81.74   394.3   72.97  408.38   72.38
  457.67   73.21  464.71   74.77  478.79   81.65  483.22   83.31  499.91   86.38
  570.32   83.69  697.06   84.68  732.27   79.87  746.35   84.18  753.39   84.81
  802.68   83.78  830.84   85.75  851.96   84.58  873.09    85.5  901.25   92.04
  950.54   94.85  992.78  105.85 1049.11  113.04  1133.6  120.33    1228  126.23
#Mann= 4 ,-1 , 0
       0     .08       0  375.69    .035       0  478.79     .08       0
  483.22      .1       0
Bank Sta=375.69,478.79
XS Rating Curve= 0 ,0
Exp/Cntr=0.3,0.1