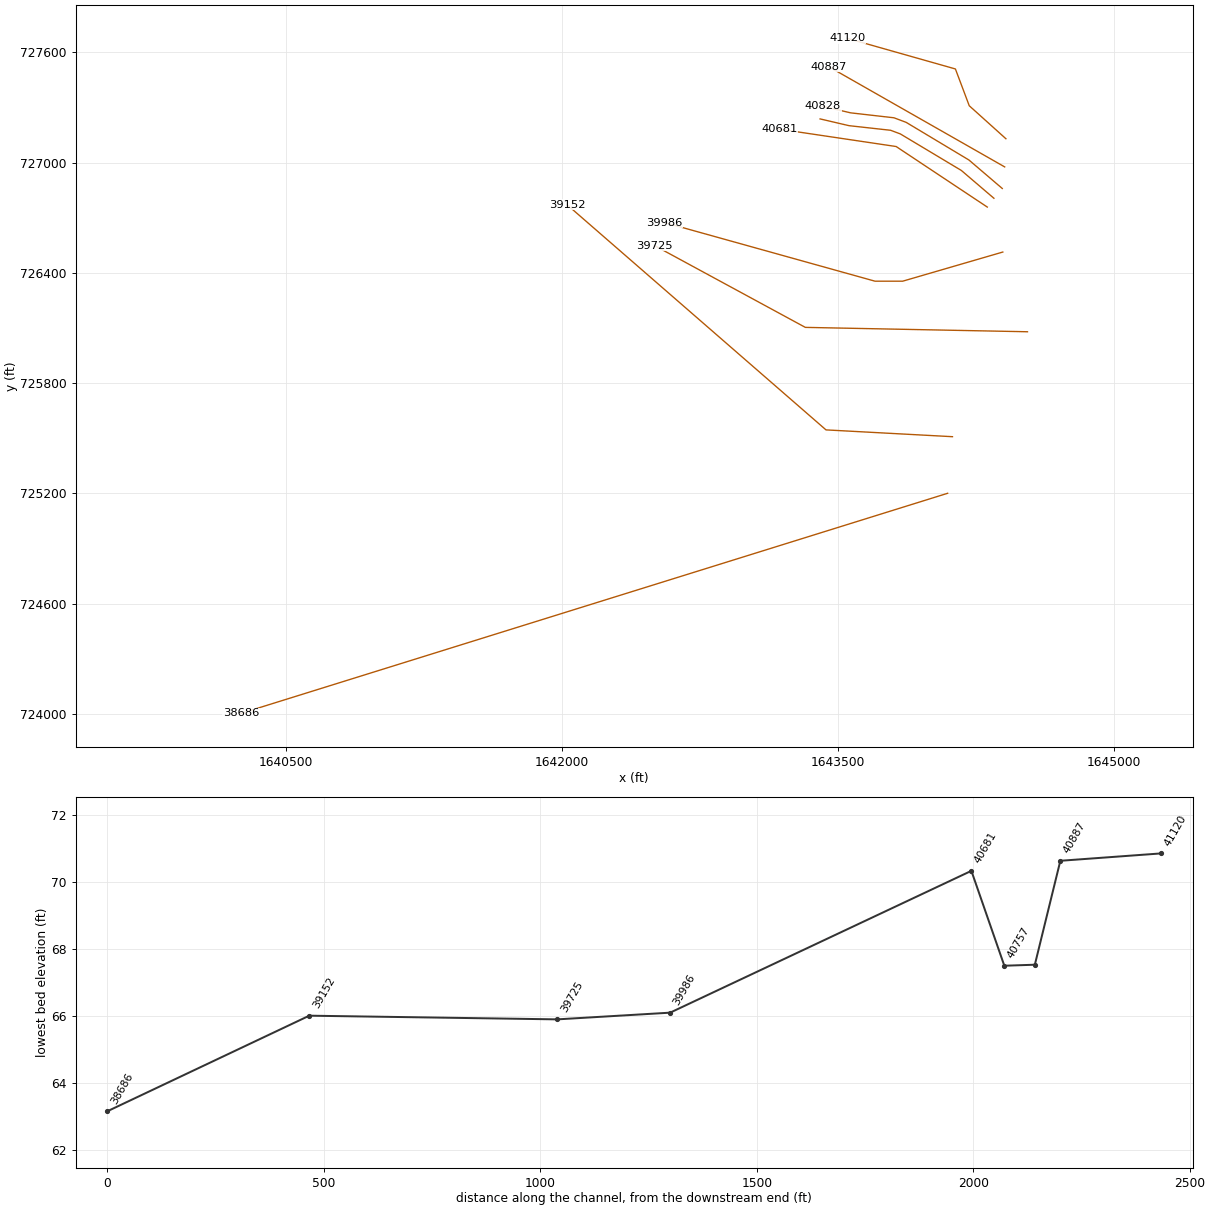
HEC-RAS study bigelkcreek.prj: Big Elk Creek

--- bigelkcreek.g23 (geometry) --- (continued)

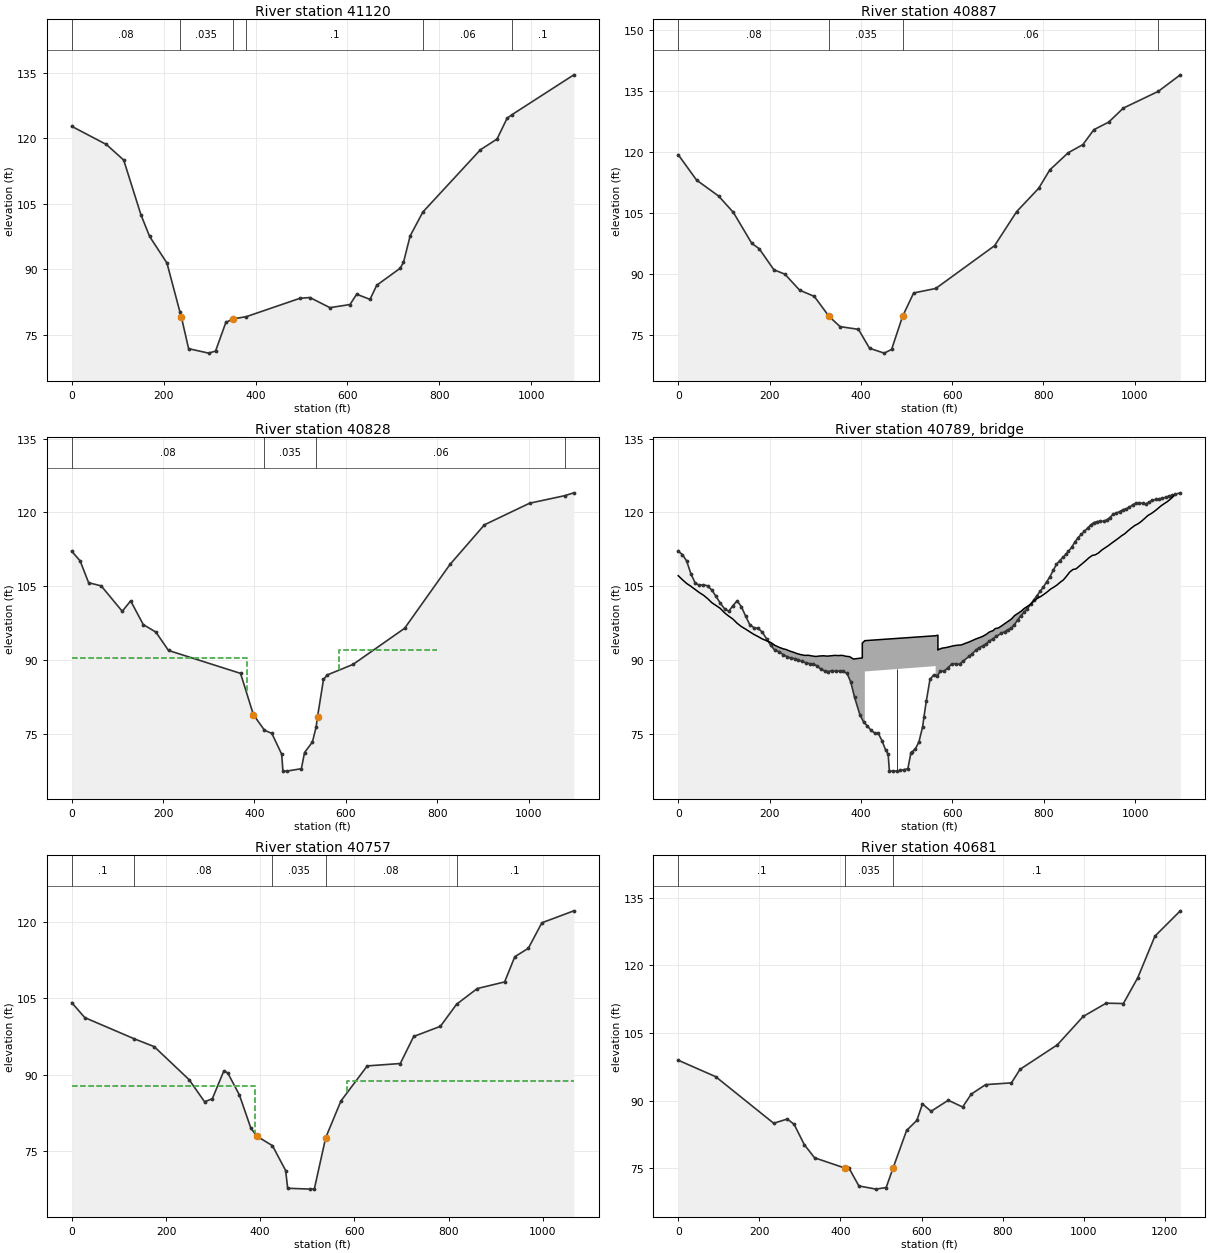
Type RM Length L Ch R = 1 ,41120   ,197.08,232.85,299.78
XS GIS Cut Line= 4
1644414.95601167727129.3685921281644215.71858825 727308.72633177
1644140.47334008727508.8466727441643552.63474807727675.395159096
#Sta/Elev= 30
       0  122.71   75.35  118.56  113.02     115   150.7  102.45  169.53   97.52
  207.21   91.44  235.46   80.25  238.69   79.06   254.3   71.87  297.99   70.85
  312.95   71.32  335.38   77.87  350.34   78.66  380.25    79.2  496.43   83.38
  518.25   83.57  561.91   81.25  605.56   81.96  620.11   84.32  649.21   83.14
  663.76   86.37  714.69   90.25  721.97   91.58  736.52   97.65  764.23  103.12
   889.3  117.34  925.68  119.81  947.51  124.56  958.65  125.41 1092.85  134.49
#Mann= 6 ,-1 , 0
       0     .08       0  235.46    .035       0  350.34     .08       0
  380.25      .1       0  764.23     .06       0  958.65      .1       0
Bank Sta=238.69,350.34
XS Rating Curve= 0 ,0
Exp/Cntr=0.3,0.1

Type RM Length L Ch R = 1 ,40887   ,61.69,58.9,58.19
XS GIS Cut Line= 2
1644408.43435028726976.1095487921643453.01095246727520.668277219
#Sta/Elev= 30
       0  119.37   40.29  113.12   88.63   109.2  120.86  105.18  161.14   97.59
  177.26   96.29  209.49   91.11  233.66   90.02  265.89    86.1  298.12   84.56
  330.34   79.65  354.52   77.14   394.8   76.47  418.97   71.83   451.2   70.63
  467.32   71.54  491.49    79.7  515.66   85.41     564   86.51  692.92   97.02
  741.26  105.39   789.6  111.13  813.78  115.63  854.06  119.84  886.29  121.85
  910.46  125.52  942.69  127.36  974.92  130.82 1051.33  134.92 1099.72  138.99
#Mann= 4 ,-1 , 0
       0     .08       0  330.34    .035       0  491.49     .06       0
 1051.33      .1       0
Bank Sta=330.34,491.49
XS Rating Curve= 0 ,0
Exp/Cntr=0.5,0.3

Type RM Length L Ch R = 1 ,40828   ,71.35,70.49,70
BEGIN DESCRIPTION:
Modified under water portion by 3 feet as per "flow depth" in bridge inspection notes.   Blocked obstruction is a rock wall on left bank - upstream side of the bridge.  Bridge inspection notes indicate that the wall is 23 feet high, 60 feet in length.
END DESCRIPTION:
XS GIS Cut Line= 6
1644395.31561302726858.7007716891644214.14646088727013.518047139
1643872.84125219727218.3571908771643806.41428645727243.282616228
1643571.13118143727270.1134215741643420.71751793727305.316619396
#Sta/Elev= 30
       0  112.14   18.42  110.16   36.83  105.76   64.45  105.11  110.49   99.96
  128.91  102.07  156.53   97.26  184.15   95.73  211.78   92.01  369.49   87.36
  397.69   78.96   421.9   75.83  438.05   75.18  459.54   70.96  462.27   67.54
  470.34   67.53  502.63   68.02  509.55    71.3  526.85   73.44  534.92   76.49
     538   78.56  551.07   86.12  559.14   87.04  615.75   89.18  728.67   96.51
  827.96  109.46  903.34   117.5 1002.15  121.88    1079  123.41 1099.12  123.99
#Mann= 4 ,-1 , 0
       0     .08       0   421.9    .035       0  534.92     .06       0
    1079     .06       0
#XS Ineff= 3 ,-1
                               0     383    90.5     585     800   92.11
Permanent Ineff=
       F       F       F
Bank Sta=397.69,538
XS Rating Curve= 0 ,0
Exp/Cntr=0.5,0.3

Type RM Length L Ch R = 3 ,40789   ,,,
BEGIN DESCRIPTION:
Elk Mills Rd. CE050207PF-8.  Approximate Reach.  Rectangular opening as shown in pictures.  Top of road assumed from lidar bridge approaches.  Railing 3 ft high.  Assumed low chord 3ft below road surface.  Modified under water portion by 3 feet as per "flow depth" in bridge inspection notes. Top of road from LIDAR.
Ineffective flow limits placed for rock wall on upstr side along left bank (23 ft high, 60 ft long).  Rock wall does not appear in LIDAR data.
END DESCRIPTION:
Bridge Culvert--1,0,-1,-1, 0
Deck Dist Width WeirC Skew NumUp NumDn MinLoCord MaxHiCord MaxSubmerge Is_Ogee
22,33,2.6,0, 125, 125, , , 0.95, 0, 0,0,,
       0    9.21   18.42   27.62   36.83   46.04   55.25   64.45   73.66   82.87
   92.08  101.28  110.49   119.7  128.91  138.12  147.32  156.53  165.74  174.95
  184.15  193.36  202.57  211.78  220.99  230.19  235.91  244.11  252.31  260.51
   268.7   276.9   285.1   293.3   301.5   309.7   317.9  326.09  334.29  342.49
  350.69  358.89  367.09  375.29  383.49  402.99     403   408.4   408.5   563.5
  563.51   568.5  568.51  569.24  577.59  585.94  594.29  602.64  610.99  619.34
  629.24  636.71  644.19  651.67  659.14  666.62   674.1  681.57  689.05  693.94
  701.03  708.12  715.21   722.3   729.4  736.49  743.58  750.67  757.76  764.86
  771.95  779.04  786.13  793.23  800.32  807.41   814.5  821.59  828.69     836
     843  850.01  857.01  864.02  871.02  878.02  885.03  892.03  899.04  906.04
  913.05  920.05  927.36  934.55  941.74  948.93  956.12   963.3  970.49  977.68
  984.87  992.06  999.25 1006.44 1013.63 1020.82 1028.01  1035.2 1042.39 1049.57
 1056.76 1063.95 1071.14 1078.33 1084.76
  107.18  106.36   105.6  105.03   104.4  103.76  103.22  102.52  101.69  101.12
  100.54   99.66   98.98   98.38   97.53   96.86   96.35    95.8   95.26   94.82
   94.33   93.99   93.63   93.04   92.65   92.33   92.21   91.89   91.65   91.36
   91.16   91.01   91.03   90.89   90.79   90.89   90.93   90.86   90.93   91.01
   90.97   91.02   90.83   90.75   90.27    90.5    93.5      94      94      95
      95   95.11   92.11   92.16   92.48   92.59   92.77   92.96   93.08   93.12
   93.48   93.73   94.04   94.35    94.6   94.88   95.27   95.78   96.02   96.45
   96.58   97.01   97.48   97.93   98.39   99.11   99.53   99.98  100.56  100.98
  101.43  102.11  102.58  102.94  103.38  103.86  104.42  104.82  105.25  105.83
  106.31  107.07  107.92  108.43  108.57  109.13  109.66  110.22   110.8  111.27
  111.42  111.79  112.39  112.84  113.28  113.79  114.27  114.75  115.27   115.7
   116.3  116.85  117.35   117.7  118.18  118.77  119.38  119.77  120.23  120.77
  121.34   121.8  122.23  122.79  123.39
                                                                                
                                                                                
                                                                                
                                                                                
                                                                   87.75   88.84
       0
                                                                                
                                                                                
                                                                                
                                                                                
                                                                                
                                                                                
                                        
       0    9.21   18.42   27.62   36.83   46.04   55.25   64.45   73.66   82.87
   92.08  101.28  110.49   119.7  128.91  138.12  147.32  156.53  165.74  174.95
  184.15  193.36  202.57  211.78  220.99  230.19  235.91  244.11  252.31  260.51
   268.7   276.9   285.1   293.3   301.5   309.7   317.9  326.09  334.29  342.49
  350.69  358.89  367.09  375.29  383.49  402.99     403   408.4   408.5   563.5
  563.51   568.5  568.51  569.24  577.59  585.94  594.29  602.64  610.99  619.34
  629.24  636.71  644.19  651.67  659.14  666.62   674.1  681.57  689.05  693.94
  701.03  708.12  715.21   722.3   729.4  736.49  743.58  750.67  757.76  764.86
  771.95  779.04  786.13  793.23  800.32  807.41   814.5  821.59  828.69     836
     843  850.01  857.01  864.02  871.02  878.02  885.03  892.03  899.04  906.04
  913.05  920.05  927.36  934.55  941.74  948.93  956.12   963.3  970.49  977.68
  984.87  992.06  999.25 1006.44 1013.63 1020.82 1028.01  1035.2 1042.39 1049.57
 1056.76 1063.95 1071.14 1078.33 1084.76
  107.18  106.36   105.6  105.03   104.4  103.76  103.22  102.52  101.69  101.12
  100.54   99.66   98.98   98.38   97.53   96.86   96.35    95.8   95.26   94.82
   94.33   93.99   93.63   93.04   92.65   92.33   92.21   91.89   91.65   91.36
   91.16   91.01   91.03   90.89   90.79   90.89   90.93   90.86   90.93   91.01
   90.97   91.02   90.83   90.75   90.27    90.5    93.5      94      94      95
      95   95.11   92.11   92.16   92.48   92.59   92.77   92.96   93.08   93.12
   93.48   93.73   94.04   94.35    94.6   94.88   95.27   95.78   96.02   96.45
   96.58   97.01   97.48   97.93   98.39   99.11   99.53   99.98  100.56  100.98
  101.43  102.11  102.58  102.94  103.38  103.86  104.42  104.82  105.25  105.83
  106.31  107.07  107.92  108.43  108.57  109.13  109.66  110.22   110.8  111.27
  111.42  111.79  112.39  112.84  113.28  113.79  114.27  114.75  115.27   115.7
   116.3  116.85  117.35   117.7  118.18  118.77  119.38  119.77  120.23  120.77
  121.34   121.8  122.23  122.79  123.39
                                                                                
                                                                                
                                                                                
                                                                                
                                                                   87.75   88.84
       0
                                                                                
                                                                                
                                                                                
                                                                                
                                                                                
                                                                                
                                        
Pier Skew, UpSta & Num, DnSta & Num=  ,478.5, 2 ,478.5, 2 , 0 , 0 , 0 ,,
       1       1
       0      90
       1       1
       0      90
BR Coef=-1 , 1 , 0 ,, 0 ,,,0.8,-1,1.2,0,
WSPro=,,,, 1 ,,,, 0 ,,,, 0 ,,,,-1 ,-1 ,-1 , 0 , 0 , 0 , 0 , 0
BR U #Sta/Elev= 143
       0  112.14    9.21  111.46   18.42  110.16   27.62  107.59   36.83  105.76
   46.04  105.22   55.25  105.34   64.45  105.11   73.66  104.25   82.87  102.97
   92.08  101.61  101.28  100.48  110.49   99.96   119.7   101.1  128.91  102.07
  138.12  100.92  147.32   99.02  156.53   97.26  165.74   96.62  174.95   96.48
  184.15   95.73  193.36   94.35  202.57   93.05  211.78   92.01  220.99   91.74
  230.19   91.13  238.31   90.74  246.51   90.45  254.71   90.35   262.9   90.11
   271.1   89.78   279.3   89.51   287.5   89.32   295.7   89.28   303.9   88.88
   312.1   88.21  320.29   87.85  328.49    87.7  336.69   87.94  344.89   87.76
  353.09   87.85  361.29   87.75  369.49   87.36  377.69   85.61  385.88   82.54
  397.69   78.96  405.76   77.49  413.83   76.73   421.9   75.83  429.98   75.26
  438.05   75.18  446.12   73.69   454.2   71.77  459.54   70.96  462.27   67.54
  470.34   67.53  478.41   67.54  486.49   67.66  494.56   67.84  502.63   68.02
  509.55    71.3  510.71   71.35  518.78   71.98  526.85   73.44  534.92   76.49
     538   78.56     543   81.72  551.07   86.12  559.14   87.04  567.22    86.9
     574   87.78  582.35    87.8   590.7   88.52  599.05   89.28   607.4   89.31
  615.75   89.18   624.1   89.85  636.44    90.8  643.92   91.38  651.39   92.05
  658.87   92.56  666.35   92.92  673.82   93.32   681.3    93.9  688.78   94.38
  696.25   94.85  707.39   95.49  714.48    95.8  721.57   96.22  728.67   96.51
  735.76    97.2  742.85   98.18  749.94   99.04  757.03   99.72  764.13  100.45
  771.22  101.34  778.31  102.24   785.4  103.11   792.5  103.99  799.59  104.93
  806.68  105.93  813.77  106.97  820.86  108.27  827.96  109.46  835.05  110.24
  842.14  110.89  849.23  111.58  854.31  112.12  861.32  112.95  868.32     114
  875.33   114.9  882.33  115.55  889.33   116.2  896.34  116.88  903.34   117.5
  910.35  117.97  917.35  118.16  924.36  118.19  931.36  118.23  938.37  118.51
  944.64  118.96  951.83   119.6  959.02  119.89  966.21  120.18   973.4  120.56
  980.58  120.77  987.77  121.07  994.96  121.58 1002.15  121.88 1009.34  121.99
 1016.53  121.83 1023.72  121.74 1030.91  122.13  1038.1  122.47 1045.29  122.64
 1052.48  122.77 1059.67  122.86 1066.86   123.1 1074.04  123.28    1079  123.41
 1081.23  123.47 1088.42   123.7 1099.12  123.99
BR U #Mann= 4
       0     .08   421.9    .033  534.92     .06    1079     .06
BR D #Sta/Elev= 140
       0  104.14    9.21  103.17   18.42  102.04   27.62   101.2   36.83  100.78
   46.04  100.43   55.25  100.29   64.45    99.9   73.66   99.42   82.87    99.3
   92.08   98.67  101.28   98.29  110.49   97.75   119.7   97.58  128.91   97.13
  132.78   97.03  138.12    96.9  147.32   96.63  156.53   96.54  165.74   96.06
  174.95    95.5  184.15   94.64  193.36    93.5  202.57   92.27  211.78   91.34
  220.99   90.91  232.71   90.22  240.91    89.8  249.11      89  257.31   87.68
  265.51   86.04   273.7   85.15   281.9   84.66   290.1   84.59   298.3   85.26
   306.5   86.76   314.7   89.14   322.9   90.76   331.1   90.32  339.29    89.1
  347.49   87.62  355.69   86.02  363.89   83.54  372.09   81.16  380.29   79.43
  385.58   78.57  393.65   77.85  401.72    77.1   409.8   76.78  417.87   76.51
  425.94   76.04  434.02   74.95  442.09   73.16  450.16   71.57  453.95   71.15
  458.23   67.67  466.31   67.55  474.38   67.57  482.45   67.57  490.53   67.61
   498.6   67.54  504.14   67.51  506.67    67.5  514.74   67.51  522.82   71.57
  530.89   74.54  538.96   77.61  547.03   80.08  555.11   81.92  562.91   83.38
  571.26   84.82  579.61   85.87  587.96   86.38  596.31   86.92  604.66   88.04
  613.01   89.66  619.63   90.92  627.11   91.71  634.59   91.67  642.06   91.15
  649.54   91.51  657.01   91.96  664.49   92.05  671.97   91.98     676   92.02
  683.09   91.87  690.18   91.74  697.27   92.18  704.37   93.26  711.46   94.91
  718.55   96.66  725.64   97.49  732.73   97.67  739.83    97.9  746.92    98.2
  754.01   98.32   761.1   98.42   768.2   98.79  775.29   99.03  782.38   99.49
  789.47   100.4  796.56  101.61  803.66  102.81  811.58  103.66  816.79  103.83
  818.58  103.89  825.59  104.29  832.59  105.06  839.59  105.81   846.6  106.19
   853.6  106.38  860.61  106.91  867.61  107.13  874.62  106.83  881.62  106.62
  888.63  106.95  895.63  107.69  904.32   108.1  911.51  107.73   918.7  108.21
  925.89  109.96  933.07  111.91  940.26  113.16  947.45   114.1  954.64   114.5
  961.83  114.41  969.02  114.82  976.21  115.94   983.4  117.59  990.59  118.68
  997.78  119.83 1004.97   120.1 1012.16  119.85 1019.34  120.08 1026.53  120.82
 1033.72  121.44 1040.91  121.68  1048.1  121.72 1055.29  121.87 1065.61  122.18
BR D #Mann= 5
       0      .1  132.78     .08  425.94    .033  538.96     .08  816.79      .1
BC Design=,, 0 ,, 0 ,,,,,,
BC Use User HTab Curves=0
BC User HTab FreeFlow(D)= 0

Type RM Length L Ch R = 1 ,40757   ,84.09,76.09,72.13
BEGIN DESCRIPTION:
Modified under water portion by 3 feet as per "flow depth" in bridge inspection notes.  Assumed bridge inspection was taken during normal flow conditions.
END DESCRIPTION:
XS GIS Cut Line= 6
 1644349.8399501726805.4845703991644172.92554519726956.665970951
1643841.09067018 727155.505278141643788.31863594727175.306956366
1643561.81848845727200.4013891221643404.76560524727237.158446878
#Sta/Elev= 30
       0  104.14   27.62   101.2  132.78   97.03  174.95    95.5  249.11      89
   281.9   84.66   298.3   85.26   322.9   90.76   331.1   90.32  355.69   86.02
  380.29   79.43  393.65   77.85  425.94   76.04  453.95   71.15  458.23   67.67
  506.67    67.5  514.74   67.51  538.96   77.61  571.26   84.82  627.11   91.71
  697.27   92.18  725.64   97.49  782.38   99.49  816.79  103.83  860.61  106.91
   918.7  108.21  940.26  113.16  969.02  114.82  997.78  119.83 1065.61  122.18
#Mann= 5 ,-1 , 0
       0      .1       0  132.78     .08       0  425.94    .035       0
  538.96     .08       0  816.79      .1       0
#XS Ineff= 2 , 0
       0     388   87.75     585       0   88.84
Permanent Ineff=
       F       F
Bank Sta=393.65,538.96
XS Rating Curve= 0 ,0
Exp/Cntr=0.5,0.3

Type RM Length L Ch R = 1 ,40681   ,572.81,695.78,727.77
XS GIS Cut Line= 3
1644313.87025969726757.6338912551643818.22399186727086.977792889
1643182.36200359727181.541883454
#Sta/Elev= 30
       0   98.96   92.45    95.3  235.32   84.96  268.94    85.9  285.75   84.72
  310.96   80.19  336.18   77.29  411.82   74.98  420.22   75.13  445.44   71.04
  487.46   70.33  512.67   70.69  529.48   74.96   563.1   83.37  588.31   85.59
  602.17   89.25   623.4   87.62  665.86   90.07  701.24   88.57  722.48   91.43
  757.86   93.54  821.55   93.93  842.78   96.94  934.78  102.38  998.48  108.68
 1055.09  111.63 1097.56  111.55 1132.94  117.26  1175.4  126.52 1237.95  132.14
#Mann= 3 , 0 , 0
       0      .1       0  411.82    .035       0  529.48      .1       0
Bank Sta=411.82,529.48
XS Rating Curve= 0 ,0
Exp/Cntr=0.3,0.1

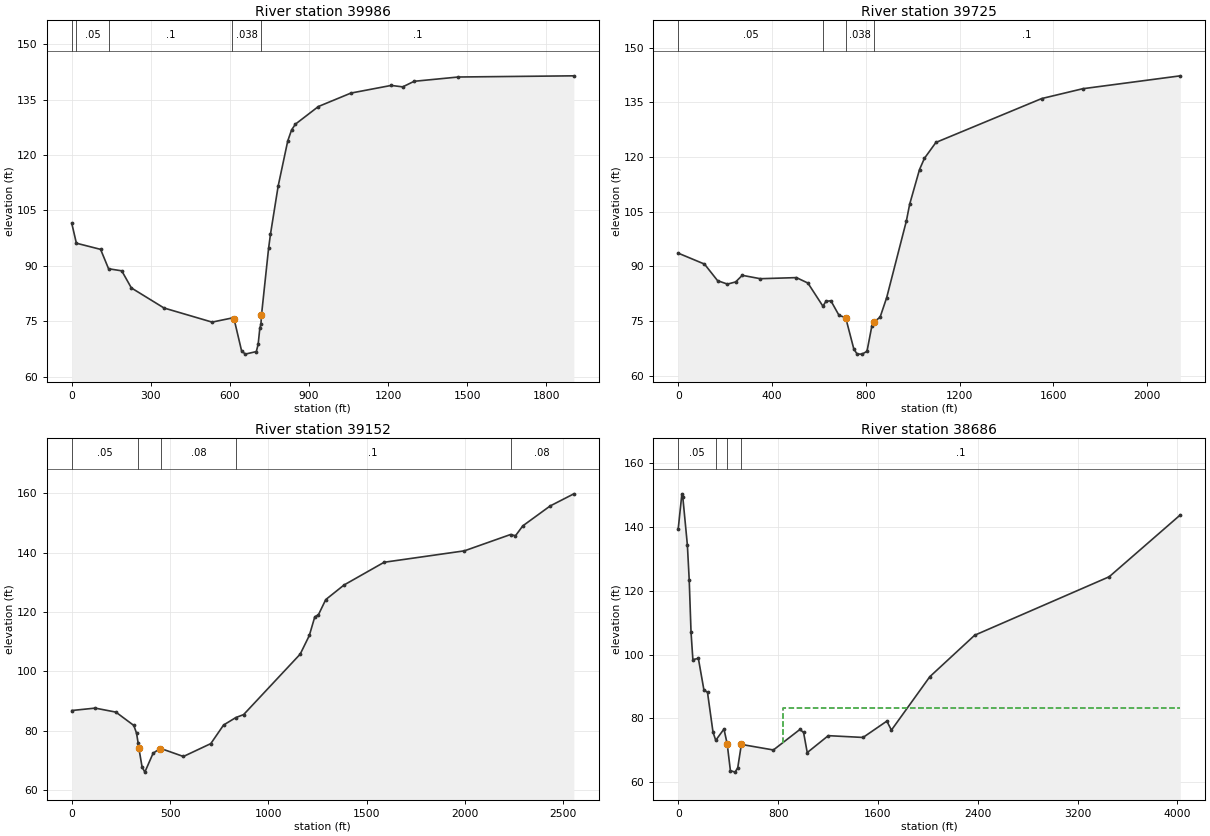
Type RM Length L Ch R = 1 ,39986   ,301.98,260.71,260.41
XS GIS Cut Line= 4
1644398.22833924726513.0478560331643853.90101175726354.552545965
1643703.41051535726354.5525459651642560.07421167726673.198112667
#Sta/Elev= 30
       0  101.52   17.52   96.14  109.36   94.47  139.59   89.22  189.56   88.66
  226.01   84.03  349.95   78.59  532.22   74.77  608.93    75.9  615.93   75.51
  643.93   67.04  657.93    66.1  699.93   66.79  706.93   68.76   713.4    73.2
  717.42   74.13   719.5   76.61  746.49   94.74  753.76   98.62  782.82  111.62
  819.16  123.83  833.69  126.81  848.23  128.38  935.43  133.16 1058.96   136.8
 1211.56  138.87 1255.16  138.48 1298.76  139.99  1465.9  141.15 1904.33  141.47
#Mann= 5 ,-1 , 0
       0      .1       0   17.52     .05       0  139.59      .1       0
  608.93    .038       0  717.42      .1       0
Bank Sta=615.93,719.5
XS Rating Curve= 0 ,0
Exp/Cntr=0.3,0.1

Type RM Length L Ch R = 1 ,39725   ,574.8,572.65,571.27
BEGIN DESCRIPTION:
no adjustment made to underwater portion from bigelk.dat hec2 model because section 19 was higher than lidar.    a quarry is located on the left side of the cross section.
END DESCRIPTION:
XS GIS Cut Line= 3
1644532.30977695726079.4929971551643324.61637248726103.289911523
1642503.79648179726548.628362879
#Sta/Elev= 30
       0   93.61  112.02   90.61  168.03   86.05  210.04   85.12  245.05   85.72
  273.05   87.53  350.07    86.6   504.1    86.9  553.11   85.41  617.04   79.07
  630.12   80.38  651.13   80.55  686.13   76.51  714.14   75.94  749.15   67.28
  763.15   65.92  784.15    65.9  805.16   66.67  826.16   73.69  833.16   74.62
  861.17   76.05  889.17   81.41  973.19  102.45  987.19  107.03  1029.2  116.55
  1050.2  119.64 1099.21     124 1550.37  136.04 1725.58  138.74 2141.77  142.28
#Mann= 4 ,-1 , 0
       0     .05       0  617.04      .1       0  714.14    .038       0
  833.16      .1       0
Bank Sta=714.14,833.16
XS Rating Curve= 0 ,0
Exp/Cntr=0.3,0.1

Type RM Length L Ch R = 1 ,39152   ,338.64,466.27,541.65
XS GIS Cut Line= 3
1644124.46738471725508.7656420021643436.99662735725545.726435393
1642030.06615828726769.563213274
#Sta/Elev= 30
       0   86.77  119.17   87.58  224.32   86.23  315.45   81.74  329.48    79.1
  337.02   75.99  340.73   74.27  357.52   67.75  371.54   66.01   413.6   72.37
  448.65   73.96  455.66    73.9  567.82   71.28  707.02   75.62  771.96   81.88
  834.13   84.39  874.02    85.4 1161.63  105.77 1208.02  112.05 1235.85  118.34
  1254.4  119.04 1291.52  124.14 1384.29  129.05  1588.4  136.72 1996.62  140.57
 2231.24  146.07  2256.4  145.65 2293.51  148.98 2432.68  155.69  2553.2  159.78
#Mann= 5 ,-1 , 0
       0     .05       0  337.02    .038       0  455.66     .08       0
  834.13      .1       0 2231.24     .08       0
Bank Sta=340.73,448.65
XS Rating Curve= 0 ,0
Exp/Cntr=0.3,0.1

Type RM Length L Ch R = 1 ,38686   ,273.93,402.32,453.94
XS GIS Cut Line= 2
1644098.21013595725200.9292094261640256.94830689724003.884825483
#Sta/Elev= 30
       0  139.53   29.33  150.47   36.66  149.42   73.32  134.38   87.98  123.45
  102.65  106.98  117.31   98.46   161.3   98.84   205.3   89.05  234.62   88.15
  278.62   75.71  300.55   73.14   366.6   76.68  392.39   71.98  417.93   63.65
  454.59   63.16  476.58   64.46  505.91   71.85  762.53   70.11  975.16   76.55
 1004.49    75.6 1033.82   69.29 1202.45    74.6 1481.07   74.04  1671.7   79.16
 1708.36   76.34 2016.31   93.11 2375.58  106.11 3453.39  124.45 4023.46  143.86
#Mann= 4 ,-1 , 0
       0     .05       0  300.55      .1       0  392.39    .038       0
  505.91      .1       0
#XS Ineff= 1 ,-1
  837.35 4023.4683.15336
Permanent Ineff=
       F
Bank Sta=392.39,505.91
XS Rating Curve= 0 ,0
Exp/Cntr=0.3,0.1