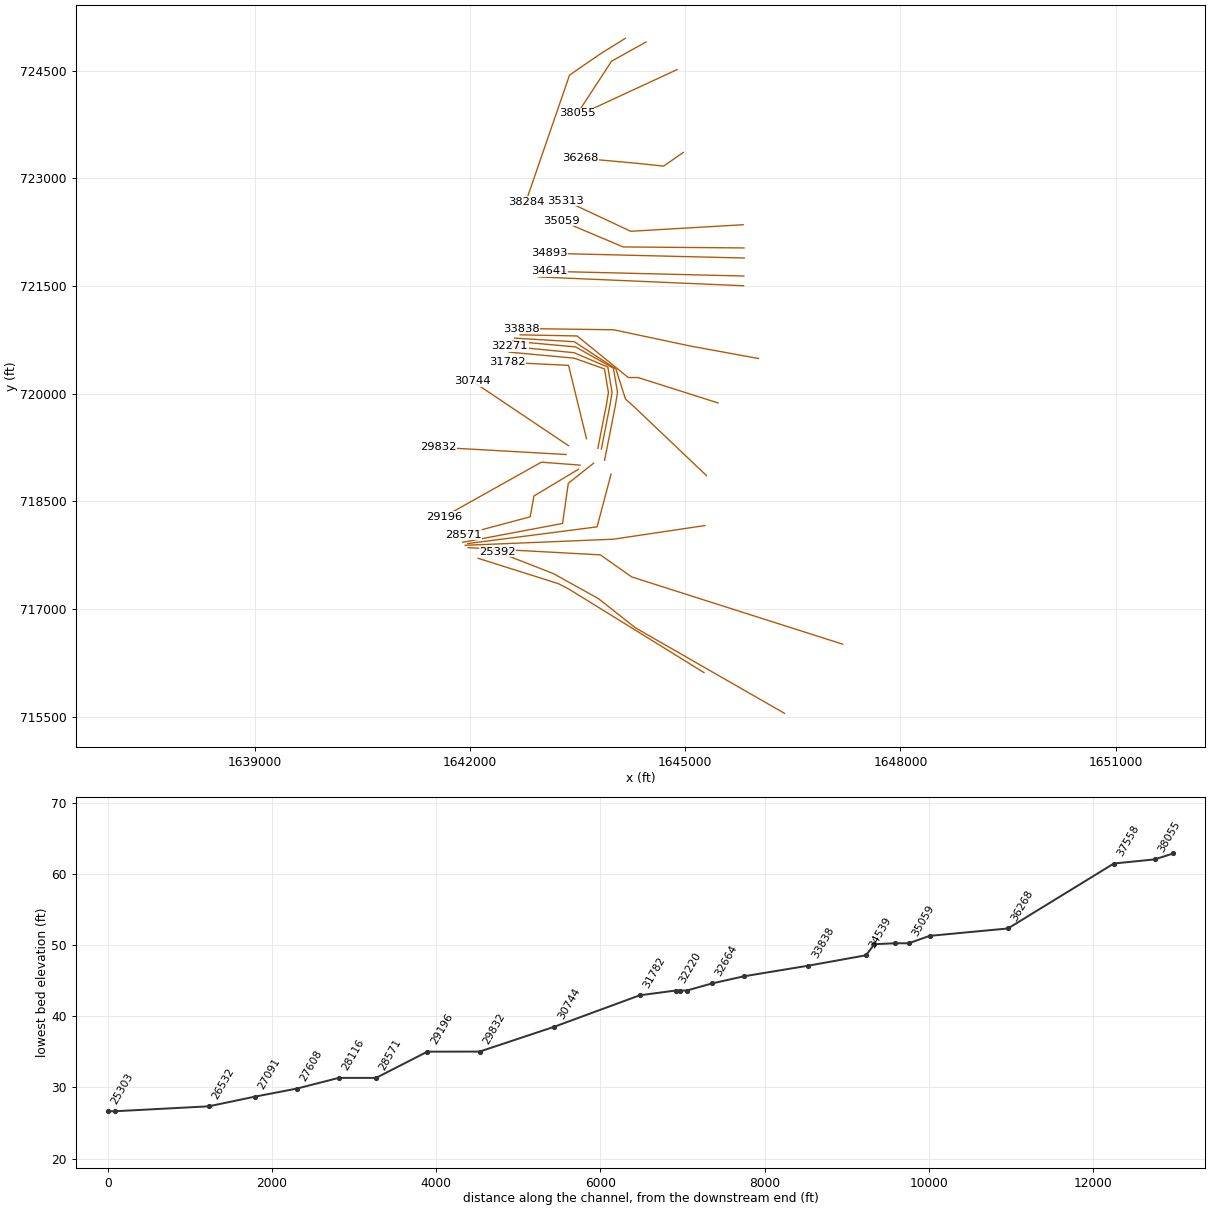
HEC-RAS study bigelkcreek.prj: Big Elk Creek

--- bigelkcreek.g23 (geometry) --- (continued)

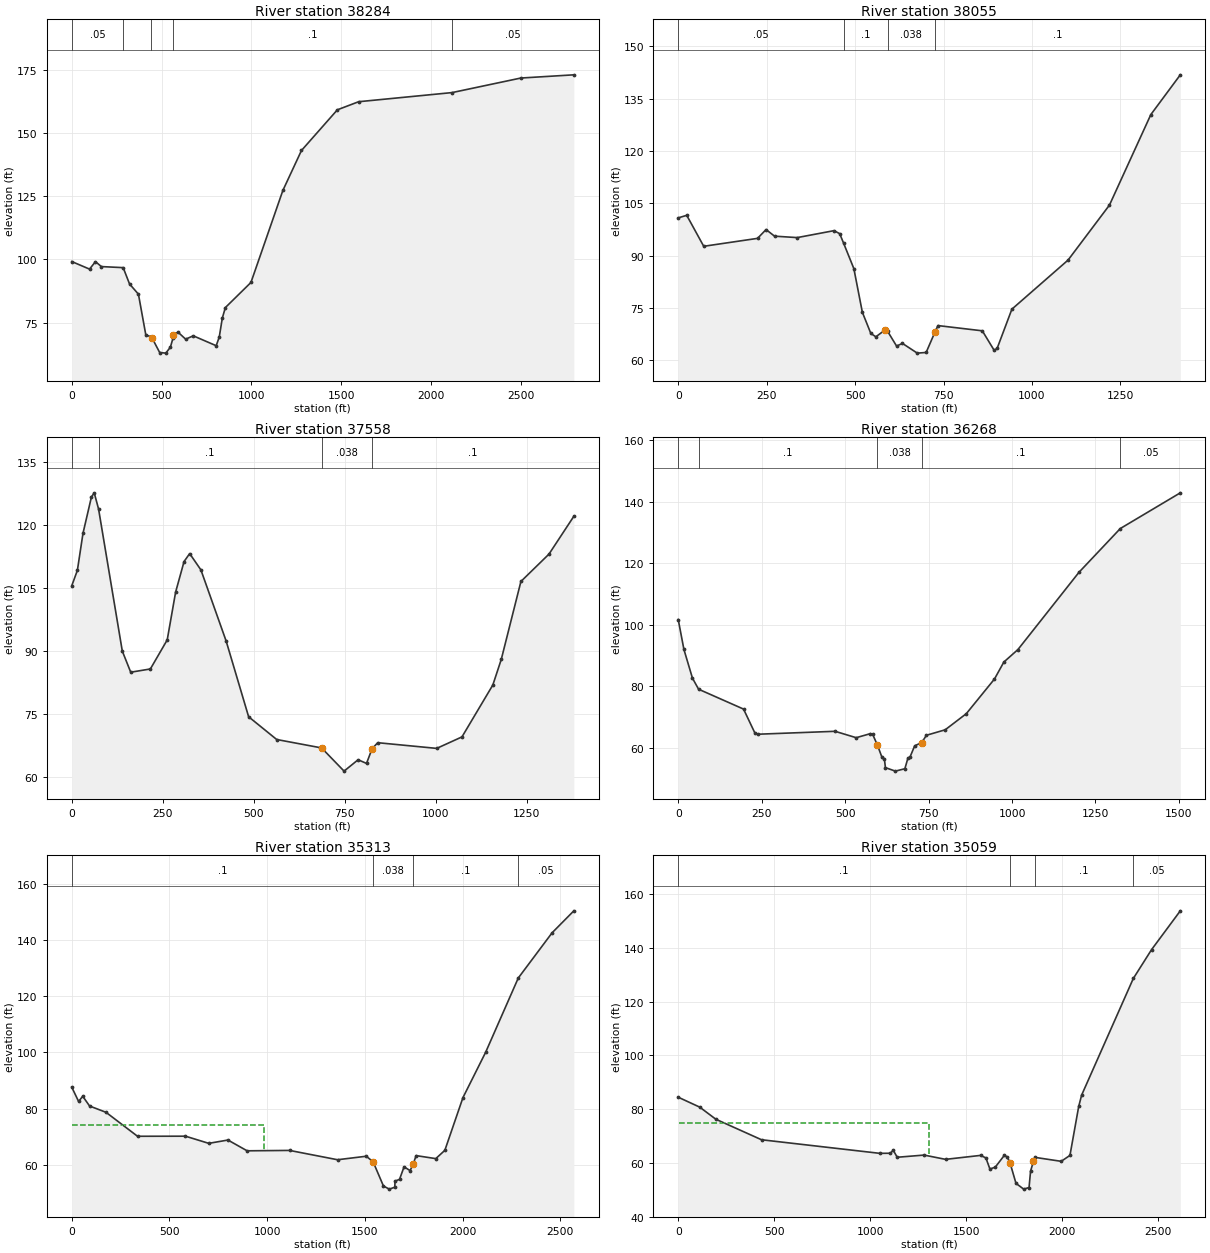
Type RM Length L Ch R = 1 ,38284   ,184.1,228.25,305.69
XS GIS Cut Line= 4
1644166.44128619 724950.361709611643808.77318554724727.201270759
1643389.39226763724437.3350480791642781.71394312722674.046436921
#Sta/Elev= 30
       0   99.12   99.01   96.13  132.01   99.08  165.02   97.13  286.36   96.71
  321.78   90.26  371.28   86.22  412.54   70.08   438.6   69.47   447.1   68.92
  489.65   63.16  523.69   62.92  549.22   65.25  564.33   68.96  566.24   70.19
  591.76   71.21  634.31   68.44  676.86   69.76   804.5   65.85  821.52    69.3
  838.53   76.77  855.55   80.93  998.02   90.86 1175.72  127.22 1279.37  143.02
 1479.28   159.1 1597.75   162.3 2118.31  165.91 2501.04  171.66 2796.45  172.93
#Mann= 5 ,-1 , 0
       0     .05       0  286.36      .1       0   438.6    .038       0
  564.33      .1       0 2118.31     .05       0
Bank Sta=447.1,566.24
XS Rating Curve= 0 ,0
Exp/Cntr=0.3,0.1

Type RM Length L Ch R = 1 ,38055   ,590.45,497.34,340.51
XS GIS Cut Line= 3
 1644456.3991037724899.2742314931643975.29207937724631.992551327
1643500.40486352 723904.24331142
#Sta/Elev= 30
       0  100.82   24.02  101.55   72.07   92.68  224.22   94.95  248.24   97.47
  272.26   95.58  336.32   95.17  440.42   97.16  456.44   96.29  467.82   93.49
  496.48   86.28   520.5   73.78  544.52   67.71  558.73   66.76   583.8   68.65
  592.16   68.28  617.23   64.11  633.95   64.86  675.74   62.08  700.82   62.27
   725.9   68.15  734.25   69.97  859.63   68.47  893.07   62.89  901.42   63.41
  943.22   74.67 1102.03   88.73 1219.05  104.48 1336.07  130.41 1419.35  141.79
#Mann= 4 ,-1 , 0
       0     .05       0  467.82      .1       0  592.16    .038       0
   725.9      .1       0
Bank Sta=583.8,725.9
XS Rating Curve= 0 ,0
Exp/Cntr=0.3,0.1

Type RM Length L Ch R = 1 ,37558   ,1223.82,1290,1010.45
BEGIN DESCRIPTION:
Beginning of approximate reach.
END DESCRIPTION:
XS GIS Cut Line= 2
1644888.06231248 724514.812588961643636.08692522723935.080143631
#Sta/Elev= 30
       0  105.52   15.43  109.18   30.86  117.99      54  126.59   61.71  127.59
   73.68  123.73  138.85   90.01     162   84.99  215.99   85.76  262.28   92.66
  285.42  104.03  308.56  111.27  323.99  113.16  354.85  109.29  424.27   92.38
  485.99   74.41  563.13   69.01  686.55   67.01  748.26    61.5  786.83    64.2
  809.98   63.33   825.4   66.85  840.83   68.25 1002.83    66.9 1072.25   69.63
 1157.11   81.96 1180.25   88.03 1234.25  106.54 1311.39  113.04 1379.68  122.02
#Mann= 4 ,-1 , 0
       0     .05       0   73.68      .1       0  686.55    .038       0
   825.4      .1       0
Bank Sta=686.55,825.4
XS Rating Curve= 0 ,0
Exp/Cntr=0.3,0.1

Type RM Length L Ch R = 1 ,36268   ,945.56,954.68,912.68
BEGIN DESCRIPTION:
underwater portion from bigelk.dat hec2 mode interpl xsec 18.0869
END DESCRIPTION:
XS GIS Cut Line= 4
1644976.67313282723361.5625156761644700.15766051723170.567292497
1644343.82328892723207.6260671321643537.40906218 723281.33930102
#Sta/Elev= 30
       0  101.68   17.02   91.96   42.54   82.64   60.92   79.02  195.67   72.55
   229.7   64.75  238.21   64.37  469.78   65.32  533.12   63.24  575.35   64.55
  582.39   64.35  596.46   60.88  610.54   56.81  617.58   56.31  620.71    53.5
650.4301   52.36   678.9   53.14  687.95   56.53  694.32   56.95  708.38    60.6
  729.47   61.65  743.53   64.03  799.76   65.81  863.02   71.06  947.37   82.34
  975.49   87.86 1017.66   91.93 1200.42  117.05 1324.36  131.31  1504.1  142.93
#Mann= 5 ,-1 , 0
       0     .05       0   60.92      .1       0  596.46    .038       0
  729.47      .1       0 1324.36     .05       0
Bank Sta=596.46,729.47
XS Rating Curve= 0 ,0
Exp/Cntr=0.3,0.1

Type RM Length L Ch R = 1 ,35313   ,304.99,254.15,254.48
BEGIN DESCRIPTION:
underwater portion from bigelk.dat hec2 model interp xsec 18.0434
END DESCRIPTION:
XS GIS Cut Line= 3
1645808.89824873722353.4676933291644242.17666653722262.121066242
1643336.32599169722686.738570079
#Sta/Elev= 30
       0   87.64   35.06   82.54    56.1   84.41   91.15   80.93   175.3   78.69
  336.57   70.15  581.99   70.18  701.19   67.63  799.36   68.81  897.52   64.97
 1114.89   65.11 1360.31   61.79 1507.55   63.04 1542.61   61.02 1595.36   52.42
 1625.22   51.32 1653.45   52.01 1654.42   54.16 1677.61    54.8  1700.8   59.27
 1731.73   57.91 1747.19   60.24 1762.65   63.26 1863.15   62.19 1909.54   65.14
 2002.31   83.94 2118.27  100.06 2285.34  126.53 2458.43  142.64 2569.81  150.47
#Mann= 4 ,-1 , 0
       0      .1       0 1542.61    .038       0 1747.19      .1       0
 2285.34     .05       0
#XS Ineff= 1 ,-1
       0  984.6674.22108
Permanent Ineff=
       F
Bank Sta=1542.61,1747.19
XS Rating Curve= 0 ,0
Exp/Cntr=0.3,0.1

Type RM Length L Ch R = 1 ,35059   ,171.35,166.42,206.59
BEGIN DESCRIPTION:
underwater portion from bigelk.dat hec2 model xsec 18
END DESCRIPTION:
XS GIS Cut Line= 3
1645820.87415084722030.1183366781644136.96651542722044.098831236
1643278.24923362 722406.87244226
#Sta/Elev= 30
       0   84.46     112   80.77  196.01   76.27  434.02   68.64 1050.04   63.59
 1106.04   63.62 1120.04   64.77 1141.04   62.13 1281.04   62.94 1393.05   61.35
 1575.05   62.82 1603.06    61.9 1624.06   57.75 1652.06   58.46 1699.16   62.84
 1714.36   62.25 1729.56   59.89 1759.96   52.43    1800   50.28    1828   50.88
 1835.95   56.99 1851.14   60.63 1858.74   62.09 1995.53   60.62 2041.12   62.82
 2086.71   81.02 2101.91   85.23  2371.3  128.62 2466.67  139.37 2616.17  153.77
#Mann= 4 ,-1 , 0
       0      .1       0 1729.56    .038       0 1858.74      .1       0
  2371.3     .05       0
#XS Ineff= 1 ,-1
    2.34 1305.36 74.6869
Permanent Ineff=
       F
Bank Sta=1729.56,1851.14
XS Rating Curve= 0 ,0
Exp/Cntr=0.5,0.3

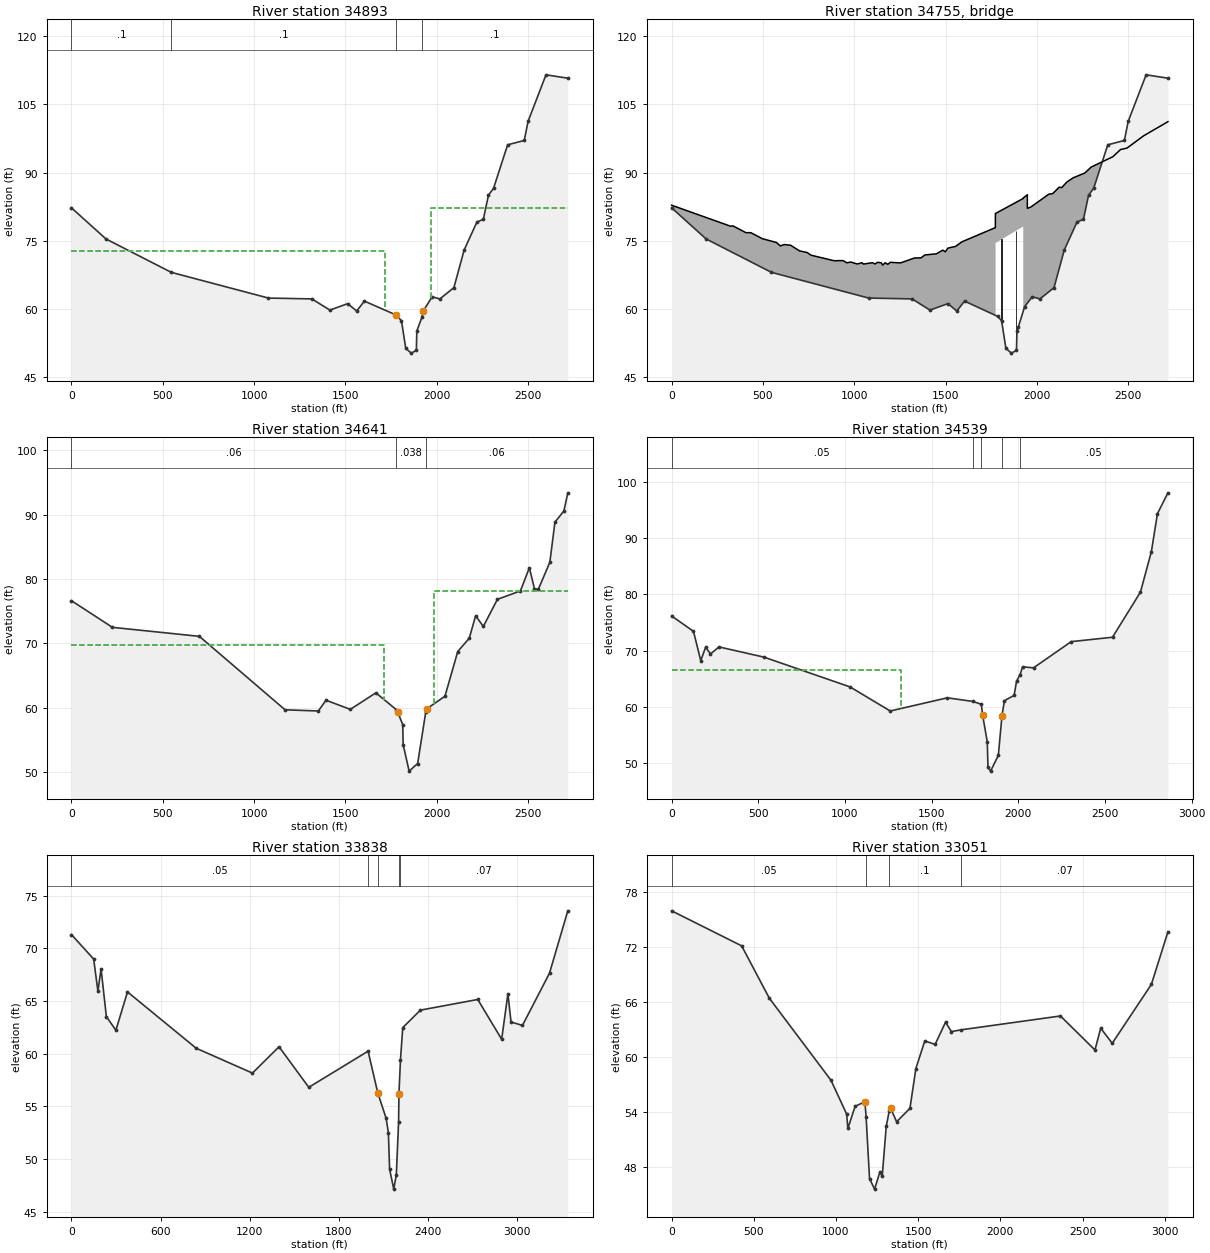
Type RM Length L Ch R = 1 ,34893   ,254.32,252.29,251.08
BEGIN DESCRIPTION:
underwater portion from bigelk.dat hec2 model xsec 18
END DESCRIPTION:
XS GIS Cut Line= 2
1645824.85699072721889.6847563681643108.52080356721955.271939978
#Sta/Elev= 30
       0   82.23  189.06   75.38  546.69   68.04 1078.31   62.39 1316.38    62.2
 1414.41   59.74 1512.44   61.16 1561.46   59.53 1603.47   61.72 1778.52   58.64
 1806.53    57.4    1830   51.33    1860   50.28    1888   50.88 1890.55   55.15
 1918.56   58.16 1925.56   59.53 1974.58   62.67 2016.59   62.19 2093.61   64.69
 2149.63   72.95 2219.65   79.12 2254.66   79.69 2282.67      85 2310.67   86.53
 2387.69   96.09 2478.72   97.05 2499.73  101.26 2597.75  111.48 2717.12  110.74
#Mann= 4 ,-1 , 0
       0      .1       0  546.69      .1       0 1778.52    .038       0
 1918.56      .1       0
#XS Ineff= 2 ,-1
       0 1714.1972.81598 1969.09 2717.12   82.11
Permanent Ineff=
       F       F
Bank Sta=1778.52,1925.56
XS Rating Curve= 0 ,0
Exp/Cntr=0.5,0.3

Type RM Length L Ch R = 3 ,34755   ,,,
BEGIN DESCRIPTION:
I95 Bridge  CE050807FS-1   Pier spacing from bridge inspection measurements and low chord taken from HEC2 model.  Assumed 3' rail height.
Top of road from LIDAR.
END DESCRIPTION:
Bridge Culvert--1,0,-1,-1, 0
Deck Dist Width WeirC Skew NumUp NumDn MinLoCord MaxHiCord MaxSubmerge Is_Ogee
55,165,2.6,0, 60, 60, , , 0.95, 0, 0,0,,
       0  322.09   336.1  406.12  434.13  497.15  574.17  595.17  616.18  651.19
   700.2  742.22  763.22  889.26  938.27  959.28  980.28 1015.29  1043.3  1050.3
 1099.32 1113.32 1127.33 1148.33 1155.34 1169.34 1183.34 1197.35 1253.36 1330.39
  1365.4  1386.4 1449.42 1484.43 1498.44 1512.44 1554.45 1589.46 1771.52 1772.49
  1772.5  1773.7    1925 1925.01  1947.5 1947.51 1967.58  2065.6 2086.61 2121.62
 2135.62 2163.63 2198.64 2261.66 2296.67  2415.7 2457.71 2492.72 2583.75 2717.12
   82.81    78.2   78.26   76.78   76.76   75.44   74.61   73.85   74.16   74.01
   72.77    72.4   71.82    70.6   70.63   70.14   70.31   69.89   70.15   69.86
   70.17   69.88   70.25   70.14   69.63   70.15   69.81   70.25   70.12   71.21
   71.23   71.87   72.12   72.93   72.56   73.37   73.75   74.76   77.87    77.9
      81      81    84.3    84.4   85.11   82.11   82.44   85.25   85.37   86.77
   86.68    87.9   88.84   89.88   91.19   93.47   95.05   95.36   98.06  101.18
                                                                                
                                                                                
                                                                                
                                                                                
           74.51   78.14
                                                                                
       0  322.09   336.1  406.12  434.13  497.15  574.17  595.17  616.18  651.19
   700.2  742.22  763.22  889.26  938.27  959.28  980.28 1015.29  1043.3  1050.3
 1099.32 1113.32 1127.33 1148.33 1155.34 1169.34 1183.34 1197.35 1253.36 1330.39
  1365.4  1386.4 1449.42 1484.43 1498.44 1512.44 1554.45 1589.46 1771.52 1772.49
  1772.5  1773.7    1925 1925.01  1947.5 1947.51 1967.58  2065.6 2086.61 2121.62
 2135.62 2163.63 2198.64 2261.66 2296.67  2415.7 2457.71 2492.72 2583.75 2717.12
   82.81    78.2   78.26   76.78   76.76   75.44   74.61   73.85   74.16   74.01
   72.77    72.4   71.82    70.6   70.63   70.14   70.31   69.89   70.15   69.86
   70.17   69.88   70.25   70.14   69.63   70.15   69.81   70.25   70.12   71.21
   71.23   71.87   72.12   72.93   72.56   73.37   73.75   74.76   77.87    77.9
      81      81    84.3    84.4   85.11   82.11   82.44   85.25   85.37   86.77
   86.68    87.9   88.84   89.88   91.19   93.47   95.05   95.36   98.06  101.18
                                                                                
                                                                                
                                                                                
                                                                                
           74.51   78.14
                                                                                
Pier Skew, UpSta & Num, DnSta & Num=  ,1806, 2 ,1806, 2 , 0 , 0 , 0 ,,
       3       3
       0      78
       3       3
       0      78
Pier Skew, UpSta & Num, DnSta & Num=  ,1885, 2 ,1885, 2 , 0 , 0 , 0 ,,
       3       3
       0      78
       3       3
       0      78
BR Coef=-1 , 1 , 0 ,, 0 ,,,0.8,0,0.5,0,
WSPro=,,,, 1 ,,,, 0 ,,,, 0 ,,,,-1 ,-1 ,-1 , 0 , 0 , 0 , 0 , 0
BR U #Sta/Elev= 30
       0   82.23  189.06   75.38  546.69   68.04 1078.31   62.39 1316.38    62.2
 1414.41   59.74 1512.44   61.16 1561.46   59.53 1603.47   61.72 1785.52   58.35
 1806.53    57.4    1830   51.33    1860   50.28    1888   50.88 1890.55   55.15
 1897.56   55.94 1932.57   60.49 1974.58   62.67 2016.59   62.19 2093.61   64.69
 2149.63   72.95 2219.65   79.12 2254.66   79.69 2282.67      85 2310.67   86.53
 2387.69   96.09 2478.72   97.05 2499.73  101.26 2597.75  111.48 2717.12  110.74
BR U #Mann= 4
       0      .1  546.69      .1 1785.52    .035 1897.56      .1
BR D #Sta/Elev= 30
       0   76.64  224.07    72.5   700.2    71.1  1029.3   64.35 1169.34   59.68
 1351.39    59.5 1393.41   61.17 1526.45   59.75 1666.49   62.32 1785.52   59.35
 1813.53   57.38 1815.84   54.26 1848.54   50.15 1895.16   51.33 1918.56   56.62
 1946.57   59.87  2044.6   61.79 2114.62   68.74 2177.64   70.81 2212.65    74.3
 2254.66   72.64 2331.68   76.85 2457.71   78.16 2506.73   81.76 2534.74   78.49
 2555.74   78.41 2618.76   82.61 2646.77   88.85 2695.78   90.59 2717.12   93.41
BR D #Mann= 3
       0     .06 1785.52    .035 1946.57     .06
BC Design=,, 0 ,, 0 ,,,,,,
BC Use User HTab Curves=0
BC User HTab FreeFlow(D)= 0

Type RM Length L Ch R = 1 ,34641   ,102.86,101.12,98.82
BEGIN DESCRIPTION:
underwater portion from bigelk.dat hec2 model xsec 17
END DESCRIPTION:
XS GIS Cut Line= 2
1645818.79824644721638.7578912971643102.46205927721704.345074907
#Sta/Elev= 30
       0   76.64  224.07    72.5   700.2    71.1 1169.34   59.68 1351.39    59.5
 1393.41   61.17 1526.45   59.75 1666.49   62.32 1778.52    59.7 1785.52   59.35
 1813.53   57.38 1815.84   54.26 1848.54   50.15 1895.16   51.33 1939.57   59.35
 1946.57   59.87  2044.6   61.79 2114.62   68.74 2177.64   70.81 2212.65    74.3
 2254.66   72.64 2331.68   76.85 2457.71   78.16 2506.73   81.76 2534.74   78.49
 2555.74   78.41 2618.76   82.61 2646.77   88.85 2695.78   90.59 2717.12   93.41
#Mann= 3 ,-1 , 0
       0     .06       0 1778.52    .038       0 1939.57     .06       0
#XS Ineff= 2 ,-1
       0    1713    69.8 1984.99 2717.12   78.14
Permanent Ineff=
       F       F
Bank Sta=1785.52,1946.57
XS Rating Curve= 0 ,0
Exp/Cntr=0.5,0.3

Type RM Length L Ch R = 1 ,34539   ,703.98,701.82,697.97
BEGIN DESCRIPTION:
underwater portion from bigelk.dat hec2 model xsec 16
END DESCRIPTION:
XS GIS Cut Line= 2
1645814.88619979 721503.178644271642954.44869983721626.333598837
#Sta/Elev= 30
       0   76.15  126.12   73.42  168.16   68.21  196.18   70.61  224.21    69.4
  273.25   70.65  532.49   68.84 1029.95   63.54 1261.17   59.27 1590.47   61.61
 1737.61   60.97 1786.65   60.46 1793.66   58.63 1820.93   53.79    1825    49.3
    1840   48.59 1884.74   51.39 1905.76   58.42 1919.77    61.1 1975.83   62.04
 1989.84   64.56 2010.47   65.75 2024.87   67.11 2087.93   66.94 2305.13   71.59
 2543.36   72.37 2704.51   80.38 2767.57   87.57  2802.6   94.32  2863.1   98.02
#Mann= 5 ,-1 , 0
       0     .05       0 1737.61      .1       0 1786.65    .038       0
 1905.76      .1       0 2010.47     .05       0
#XS Ineff= 1 ,-1
 -294.48 1322.3866.46709
Permanent Ineff=
       F
Bank Sta=1793.66,1905.76
XS Rating Curve= 0 ,0
Exp/Cntr=0.3,0.1

Type RM Length L Ch R = 1 ,33838   ,761.69,787.06,717.02
BEGIN DESCRIPTION:
underwater portion from bigelk.dat hec2 model xsec 15 with 1.5 foot vertical adjustment
END DESCRIPTION:
XS GIS Cut Line= 5
1646023.22396146720489.3782267721645070.87954636720663.683902487
1644007.17188562  720889.47090591643691.18533958720894.332237393
1642720.98826562720907.228717968
#Sta/Elev= 30
       0    71.3  149.44   68.98  177.91   65.94  199.26   68.05  234.84   63.52
  298.88   62.22  377.16   65.86  839.72   60.51 1218.62   58.15 1397.52   60.65
 1597.89    56.8 1997.12   60.23 2062.58   56.26 2118.58   53.86 2133.83    52.5
    2142   49.03    2170   47.13 2187.27   48.48 2202.59   53.51 2204.97    56.2
 2215.34   59.44  2230.6   62.47 2349.61   64.13 2735.64   65.14 2896.65   61.36
 2938.66   65.69 2959.66      63 3036.67   62.68 3218.69   67.64  3341.9   73.56
#Mann= 5 ,-1 , 0
       0     .05       0 1997.12      .1       0 2062.58    .038       0
 2202.59      .1       0 2215.34     .07       0
Bank Sta=2062.58,2204.97
XS Rating Curve= 0 ,0
Exp/Cntr=0.3,0.1

Type RM Length L Ch R = 1 ,33051   ,444.61,386.85,196.34
BEGIN DESCRIPTION:
underwater portion from bigelk.dat hec2 model xsec 15
END DESCRIPTION:
XS GIS Cut Line= 5
1645459.88010591719870.3276618271644345.49915588720224.197935641
1644208.91764672720224.1979356411643494.70250586720803.831527054
1642700.83218013720819.364104807
#Sta/Elev= 30
       0   75.91  425.98    72.1   594.9   66.39  969.47   57.48 1064.95   53.79
 1072.29   52.23 1116.36   54.64 1176.22   55.14 1183.22   53.49 1204.22   46.77
    1235   45.63 1267.22    47.5 1281.22   47.03  1305.8   52.46 1323.83   54.12
 1332.85   54.41 1368.91   52.96 1450.04   54.42  1486.1   58.75 1540.19   61.75
  1603.3   61.38 1666.41   63.79 1702.47   62.77 1760.44   62.96 2365.65   64.47
 2575.68   60.77 2610.69   63.14  2680.7    61.5 2918.74    67.9 3019.63   73.62
#Mann= 4 ,-1 , 0
       0     .05       0 1183.22    .038       0 1323.83      .1       0
 1760.44     .07       0
Bank Sta=1176.22,1332.85
XS Rating Curve= 0 ,0
Exp/Cntr=0.3,0.1

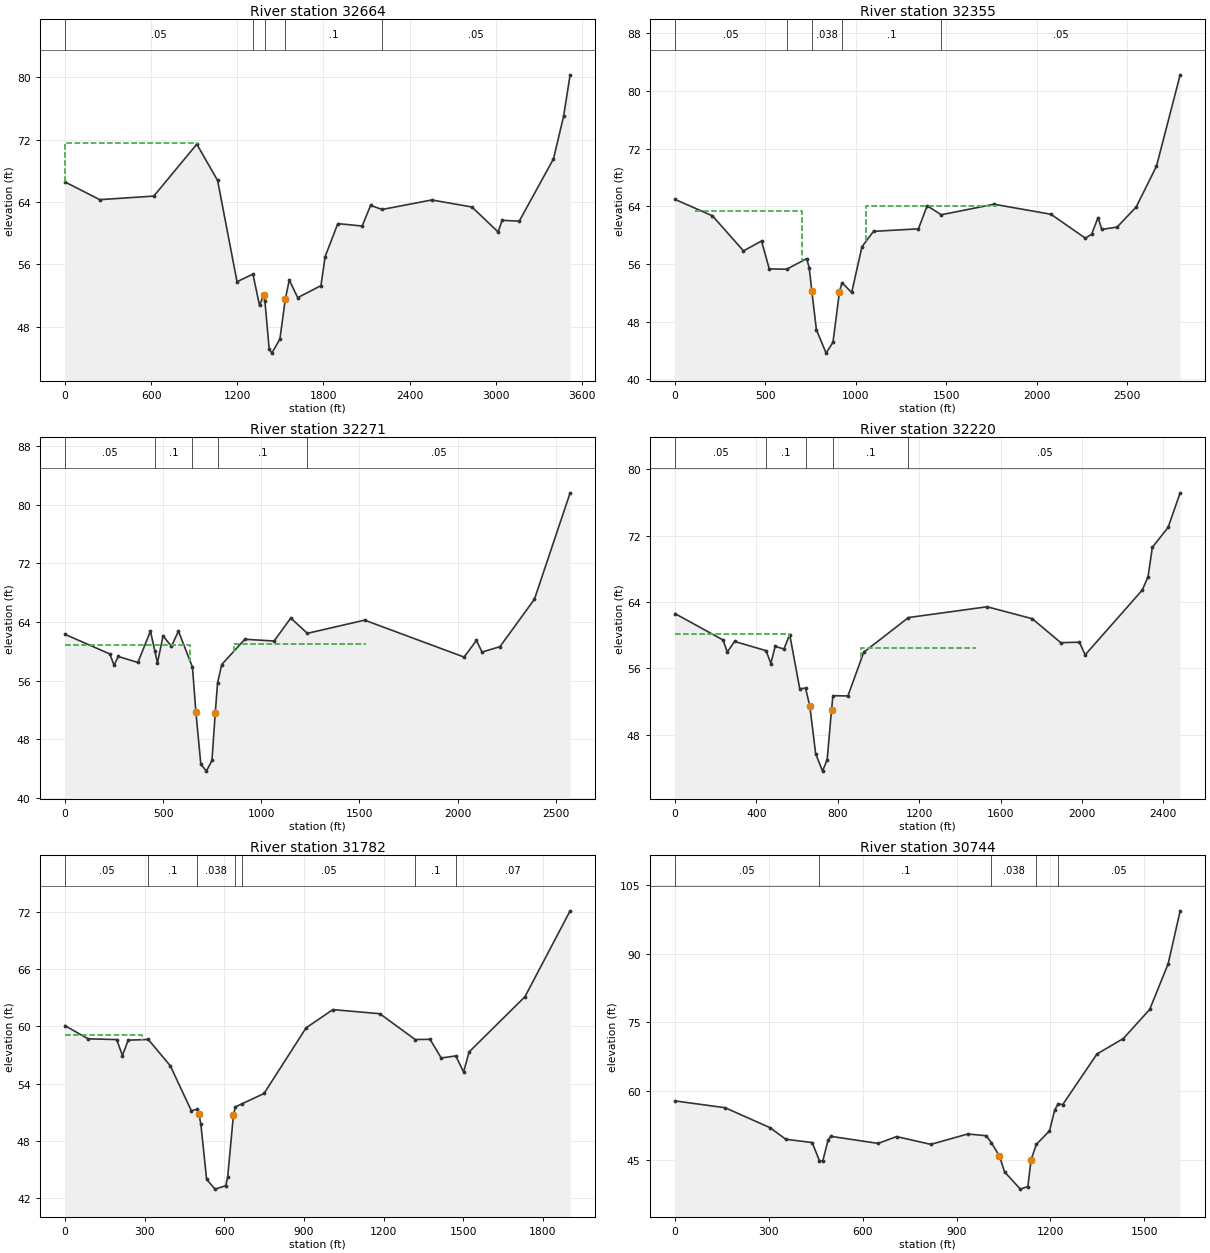
Type RM Length L Ch R = 1 ,32664   ,315.92,308.94,69.9
BEGIN DESCRIPTION:
underwater portion from bigelk.dat hec2 model xsec 15
END DESCRIPTION:
XS GIS Cut Line= 6
1645298.11187737718857.8853971511644323.49219923719785.001548812
1644168.56401899719926.2019155771644035.08663498720345.258818805
1643455.11433104720723.6972016251642625.39893422 720773.40365395
#Sta/Elev= 30
       0   66.57  241.53    64.3  618.32   64.76  917.82   71.41 1062.74   66.76
    1198   53.78  1308.8   54.76 1354.62   50.75 1383.03   52.04 1392.51   51.25
 1421.87   45.19    1440   44.63 1496.69   46.43 1534.57   51.59 1562.12      54
 1620.89   51.74 1782.51   53.28  1811.9   57.01 1900.06   61.23  2069.8   60.92
 2128.31   63.57 2208.43   63.04 2554.59   64.26 2834.35   63.36 3016.68   60.16
 3044.73   61.65 3163.94   61.55 3402.36   69.53 3472.49   74.96 3518.28    80.3
#Mann= 5 ,-1 , 0
       0     .05       0  1308.8      .1       0 1392.51    .038       0
 1534.57      .1       0 2208.43     .05       0
#XS Ineff= 2 , 0
          916.56   71.52
Permanent Ineff=
       F       F
Bank Sta=1383.03,1534.57
XS Rating Curve= 0 ,0
Exp/Cntr=0.5,0.3

Type RM Length L Ch R = 1 ,32355   ,75.17,84.09,74.89
BEGIN DESCRIPTION:
underwater portion from bigelk.dat hec2 model xsec 15 with -2 ft vertical adjustment
END DESCRIPTION:
XS GIS Cut Line= 6
1643877.80771065719070.9247700571644025.08045025 719816.59801954
1644058.35103807 720016.221546651644000.94125772720354.571194425
1643474.23219727720651.0493097311642594.81034815720731.344348133
#Sta/Elev= 30
       0   64.95  206.92   62.67  378.17   57.81  478.06   59.18  520.87   55.31
  617.28   55.27  727.79   56.74  742.06   55.44  756.33    52.2  781.37    46.9
     835   43.63  873.25   45.14   909.1   52.16   923.3   53.39  976.65   52.04
 1033.45   58.39 1097.36   60.52  1345.8   60.87    1394   64.07 1471.98   62.82
 1763.51   64.28 2078.76   62.89 2268.54   59.58 2303.69   60.12 2338.83   62.44
 2359.92   60.79 2444.27   61.11  2549.7   63.89 2662.17   69.56 2793.13   82.23
#Mann= 5 ,-1 , 0
       0     .05       0  617.28      .1       0  756.33    .038       0
   923.3      .1       0 1471.98     .05       0
#XS Ineff= 2 ,-1
  111.11  699.2763.35688 1058.31 1778.9964.00984
Permanent Ineff=
       F       F
Bank Sta=756.33,909.1
XS Rating Curve= 0 ,0
Exp/Cntr=0.5,0.3

Type RM Length L Ch R = 1 ,32271   ,50.05,50.26,50.63
BEGIN DESCRIPTION:
underwater portion from bigelk.dat hec2 model xsec 15 with -2 ft vertical adjustment   Looks like an old road or railway embankment was located at this cross sections.  Cross sections upstream and downstream of this section will have modified expansion and contraction coefficients to account fo the constrictions left by the embankment.  Ineffective flow limits have also been set to account for the constriction caused by this section.
END DESCRIPTION:
XS GIS Cut Line= 6
1643833.31849644 719227.773743571643951.27525434719829.974034101
1643982.31650646 720016.221546651643923.33812748720370.091820464
1643451.29075776720570.754271343 1642556.5746156720658.696456224
#Sta/Elev= 30
       0   62.31  228.26   59.63  249.66   58.09  271.05   59.29  370.92   58.47
  435.11   62.74  457.25   60.09  470.78   58.41  499.31   62.11  542.11   60.68
  577.77   62.75  649.13   57.83  666.56   51.71  691.71   44.59     720   43.63
  748.48   45.09  765.13   51.53  776.86   55.64  798.15   58.19  916.01   61.64
 1065.03    61.4 1150.19   64.54 1234.35   62.45 1526.31   64.25 2032.86   59.21
 2096.16   61.48  2124.3   59.89 2215.73   60.63 2391.58   67.12 2573.16   81.64
#Mann= 5 ,-1 , 0
       0     .05       0  457.25      .1       0  649.13    .038       0
  776.86      .1       0 1234.35     .05       0
#XS Ineff= 2 ,-1
       0  636.4760.83267   858.5 1535.2860.95327
Permanent Ineff=
       F       F
Bank Sta=666.56,765.13
XS Rating Curve= 0 ,0
Exp/Cntr=0.5,0.3

Type RM Length L Ch R = 1 ,32220   ,378.27,437.92,468.34
BEGIN DESCRIPTION:
underwater portion from bigelk.dat hec2 model xsec 15 with -2 ft vertical adjustment
END DESCRIPTION:
XS GIS Cut Line= 6
1643784.25093706719237.3849150091643902.07179046719838.891377136
1643931.62681873 720016.221546651643876.97580105720344.127652675
1643455.11433104720494.2828061731642548.92746903720578.401417822
#Sta/Elev= 30
       0   62.61  235.39   59.44  256.79   57.99  292.45   59.26  447.44   58.15
  470.78    56.6  492.18   58.68  534.98   58.34  563.51   60.09  612.94   53.55
  641.32   53.64  662.61   51.43     691   45.73     725   43.63  747.77   45.03
  769.06   51.03  776.16   52.72  849.49   52.69  927.55   57.96  1147.4   62.14
  1533.8   63.44 1755.71      62 1896.32   59.11 1987.71   59.17 2015.83   57.64
 2297.03   65.46 2325.15   67.07 2346.24    70.6 2423.57      73 2483.01   77.17
#Mann= 5 ,-1 , 0
       0     .05       0  447.44      .1       0  641.32    .038       0
  776.16      .1       0  1147.4     .05       0
#XS Ineff= 2 ,-1
  -31.53  557.8960.16853  916.43 1481.2158.51728
Permanent Ineff=
       F       F
Bank Sta=662.61,769.06
XS Rating Curve= 0 ,0
Exp/Cntr=0.5,0.3

Type RM Length L Ch R = 1 ,31782   ,710.63,1038.88,1077.23
BEGIN DESCRIPTION:
underwater portion from bigelk.dat hec2 model xsec 15 with -3.5ft vertical adjustment
END DESCRIPTION:
XS GIS Cut Line= 3
1643625.83498004719371.8523347821643376.12686302720394.186743394
1642527.19747749720435.342998371
#Sta/Elev= 30
       0   60.09   86.47   58.71  194.56   58.63  216.17   56.96  237.79   58.57
   313.5   58.64  396.32   55.89  475.58   51.18   497.2   51.32   504.4   50.83
  511.61   49.74  533.23   43.98     565   42.96  605.29   43.32  612.49   44.22
  634.11    50.7  641.32   51.57  666.38    51.9   749.4   52.98  907.93   59.86
 1008.81   61.77 1185.55   61.34 1318.8758.63316 1374.77   58.66 1416.82    56.7
 1471.82   56.92 1500.91   55.23 1521.94   57.34 1732.18   63.12 1902.31   72.12
#Mann= 7 ,-1 , 0
       0     .05       0   313.5      .1       0   497.2    .038       0
  641.32      .1       0  666.38     .05       0 1318.87      .1       0
 1471.82     .07       0
#XS Ineff= 2 , 0
          291.53   59.11
Permanent Ineff=
       F       F
Bank Sta=504.4,634.11
XS Rating Curve= 0 ,0
Exp/Cntr=0.3,0.1

Type RM Length L Ch R = 1 ,30744   ,466,911.32,803.86
BEGIN DESCRIPTION:
underwater portion from bigelk.dat hec2 model xsec 14
END DESCRIPTION:
XS GIS Cut Line= 2
1643374.68272519719275.0800028741642033.79798576720175.125923857
#Sta/Elev= 30
       0   57.83  160.18   56.34  303.51   51.98  354.09   49.44   438.4   48.73
  461.39   44.77  472.12   44.66  488.98   49.21  497.41   50.09  649.17   48.54
  708.18   50.03  817.78   48.33  935.81    50.6  994.83   50.22 1011.69   48.66
 1036.98   45.78 1053.84   42.28    1104   38.54    1128   39.11 1138.15   44.93
 1155.01   48.32 1197.16   51.28 1214.02   55.89 1224.93    57.2 1239.32   57.02
 1348.91   68.09 1433.22   71.47 1517.53   77.84 1576.54   87.82 1614.94    99.4
#Mann= 5 ,-1 , 0
       0     .05       0  461.39      .1       0 1011.69    .038       0
 1155.01      .1       0 1224.93     .05       0
Bank Sta=1036.98,1138.15
XS Rating Curve= 0 ,0
Exp/Cntr=0.3,0.1

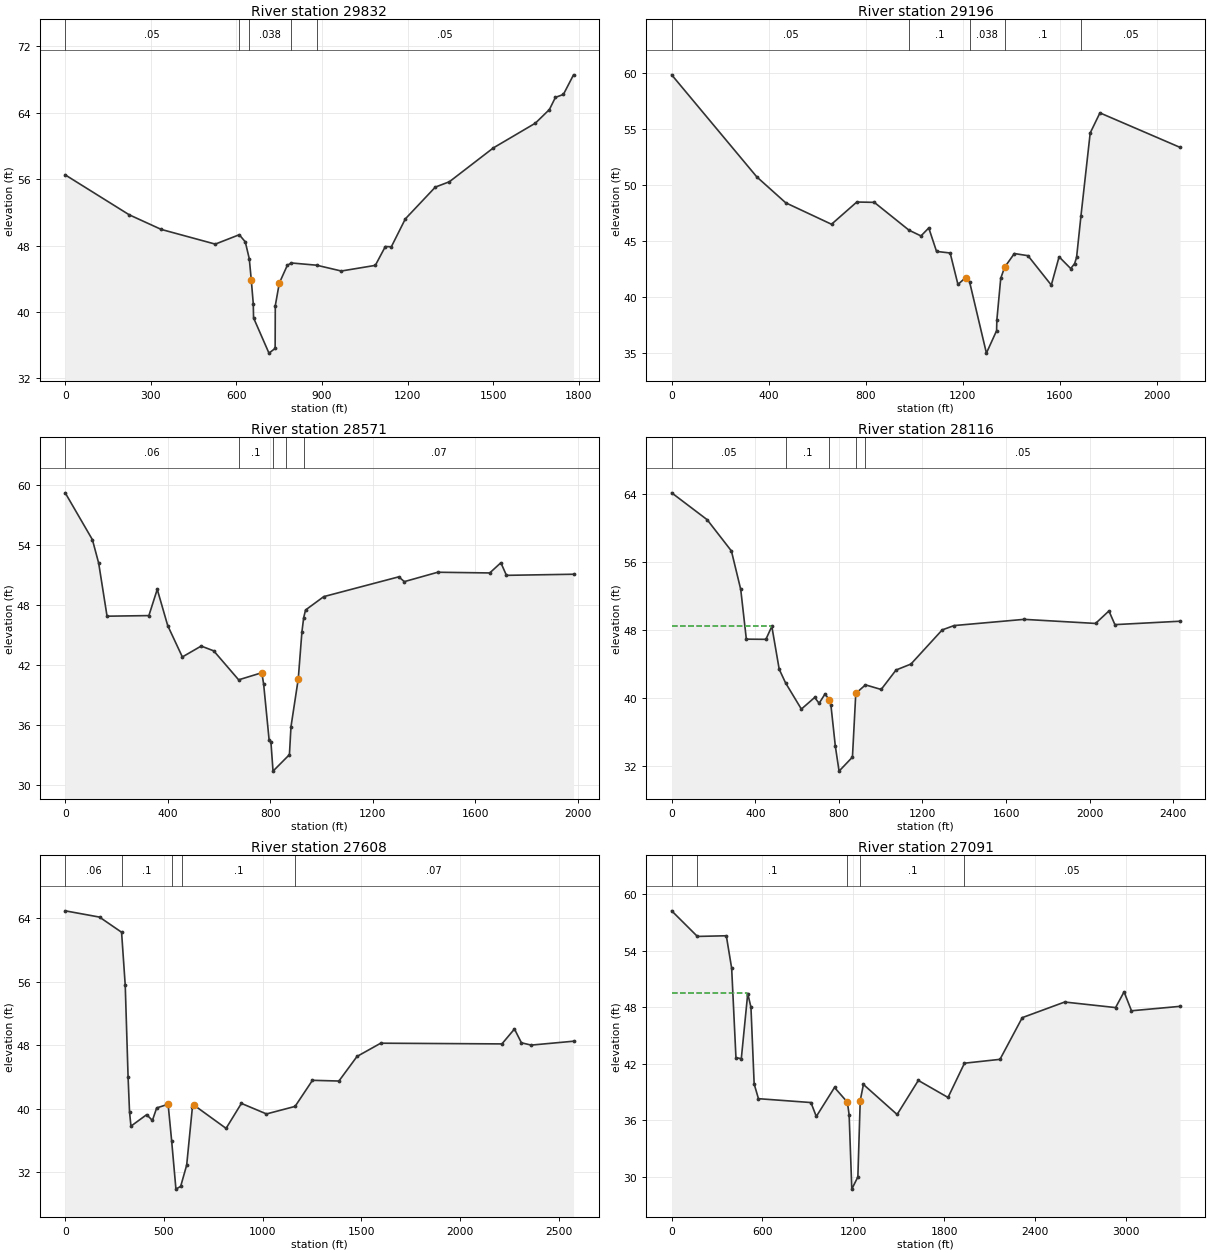
Type RM Length L Ch R = 1 ,29832   ,580.4,635.91,618.46
BEGIN DESCRIPTION:
underwater portion from bigelk.dat hec2 model xsec 14 with -3.5' vertical adjustment
END DESCRIPTION:
XS GIS Cut Line= 2
1643341.73135972719152.2589135021641563.29738785719252.369435087
#Sta/Elev= 30
       0   56.51  224.35    51.7  336.53   49.94  525.83   48.17  609.96    49.3
     631   48.44  645.02   46.41  652.03   43.84  659.04   40.98     660   39.29
     714   35.04  735.65   35.61  736.16   40.75  750.19   43.47  778.23   45.61
  792.25    45.9  881.01   45.63  967.53   44.93 1086.72   45.61 1121.78   47.88
 1142.81   47.85 1191.89   51.21 1297.05   55.04 1346.13   55.68 1500.38   59.76
 1647.61   62.74 1696.69   64.38 1717.72   65.84 1745.76    66.2 1781.25   68.56
#Mann= 5 ,-1 , 0
       0     .05       0  609.96      .1       0  645.02    .038       0
  792.25      .1       0  881.01     .05       0
Bank Sta=652.03,750.19
XS Rating Curve= 0 ,0
Exp/Cntr=0.3,0.1

Type RM Length L Ch R = 1 ,29196   ,531.95,625.29,768.76
BEGIN DESCRIPTION:
underwater portion from bigelk.dat hec2 model xsec 13
END DESCRIPTION:
XS GIS Cut Line= 3
1643535.40521109719004.1478123661642998.13290109719045.476451606
1641638.95921209718284.878287449
#Sta/Elev= 30
       0   59.82  351.03   50.73  470.39   48.42  659.18   46.51  763.46   48.49
  835.65   48.46   978.8   45.98 1028.17   45.47 1060.26   46.18 1092.34   44.09
 1148.49   43.95 1180.58   41.15 1212.66   41.76 1228.71   41.37    1298   35.03
    1340   37.03 1341.01   37.96 1357.05   41.69 1373.09   42.68  1413.2    43.9
 1469.35   43.71 1565.61   41.09  1597.7   43.61 1645.82   42.56 1661.87   43.01
 1669.89   43.56    1688   47.27 1726.04   54.64 1766.15   56.43 2096.37   53.36
#Mann= 5 ,-1 , 0
       0     .05       0   978.8      .1       0 1228.71    .038       0
 1373.09      .1       0    1688     .05       0
Bank Sta=1212.66,1373.09
XS Rating Curve= 0 ,0
Exp/Cntr=0.3,0.1

Type RM Length L Ch R = 1 ,28571   ,452.96,454.85,501.59
BEGIN DESCRIPTION:
underwater portion from bigelk.dat hec2 model xsec 12
END DESCRIPTION:
XS GIS Cut Line= 4
1643514.91119422718946.8431833981642893.59499367718574.053463072
1642841.81864363718284.1059028211641909.84434277718035.579422593
#Sta/Elev= 30
       0    59.2  106.12   54.51  130.61   52.16  163.27   46.85  326.53   46.91
  359.19   49.54     400   45.91  457.15   42.77  530.62   43.86   579.6   43.38
  676.82   40.48  767.24   41.19  774.35   40.05  795.68   34.48  802.79   34.25
     811   31.34     875   32.99  881.01   35.78  909.45   40.57  923.67   45.26
  930.53   46.69  937.89   47.47    1009   48.81 1301.65   50.79 1323.38   50.31
 1453.78   51.25 1656.63   51.18  1700.1    52.2 1721.84   50.94 1983.65   51.05
#Mann= 5 ,-1 , 0
       0     .06       0  676.82      .1       0   812.3    .038       0
  862.29      .1       0  930.53     .07       0
Bank Sta=767.24,909.45
XS Rating Curve= 0 ,0
Exp/Cntr=0.3,0.1

Type RM Length L Ch R = 1 ,28116   ,515.35,508.43,356.88
BEGIN DESCRIPTION:
underwater portion from bigelk.dat hec2 model xsec 12
END DESCRIPTION:
XS GIS Cut Line= 4
1643725.99202552719031.6759714781643372.59669293718751.626839966
1643292.58265534 718191.528576941641901.50527292717928.982516125
#Sta/Elev= 30
       0   64.09   169.7   60.93  285.81   57.25  330.46   52.72  357.26   46.87
  450.91   46.85  479.19   48.38  514.55   43.33  544.84   41.73  620.61   38.64
  684.25   40.01  705.46   39.32  733.75   40.42  754.96   39.71  762.03    39.1
  783.24   34.25     801   31.34     865   32.99     881   40.49  927.44   41.49
 1002.45   40.95 1073.68   43.24 1144.91   43.94 1294.51   47.96 1351.49   48.47
  1686.3    49.2 2028.23   48.72 2092.34   50.19 2120.84   48.58 2432.32   48.98
#Mann= 5 ,-1 , 0
       0     .05       0  544.84      .1       0  754.96    .038       0
     881      .1       0  927.44     .05       0
#XS Ineff= 2 , 0
          476.48   48.38
Permanent Ineff=
       F       F
Bank Sta=754.96,881
XS Rating Curve= 0 ,0
Exp/Cntr=0.3,0.1

Type RM Length L Ch R = 1 ,27608   ,692.33,517.1,185.96
BEGIN DESCRIPTION:
underunderwater portion from bigelk.dat hec2 model xsec 12 with -1.5 ft adjustment
END DESCRIPTION:
XS GIS Cut Line= 3
1643967.95425712718877.5923152121643773.79294443718144.309757695
1641971.97596285717911.316182479
#Sta/Elev= 30
       0   64.93  173.79   64.14  285.61   62.23  304.13   55.53  318.61   43.95
  325.86   39.59   333.1   37.78  412.75   39.23  441.72    38.5  463.44   40.08
  521.37   40.54  539.28   35.93     561   29.84     585   30.19   615.5   32.88
  644.47   40.19  651.71   40.44  815.02    37.5  892.66   40.65 1019.71   39.32
 1164.58   40.27 1252.63   43.56 1386.74   43.47 1478.49   46.57 1598.48   48.24
 2212.55   48.15 2276.08   50.03 2311.37   48.29 2360.78      48 2575.37   48.49
#Mann= 5 ,-1 , 0
       0     .06       0  285.61      .1       0  539.28    .038       0
  589.76      .1       0 1164.58     .07       0
Bank Sta=521.37,651.71
XS Rating Curve= 0 ,0
Exp/Cntr=0.3,0.1

Type RM Length L Ch R = 1 ,27091   ,658.22,558.98,258.51
BEGIN DESCRIPTION:
underwater portion from bigelk.dat hec2 model xsec 12 with -3 foot adjustment
END DESCRIPTION:
XS GIS Cut Line= 3
1645277.09748313 718162.356792391643998.06017031717971.864987239
 1641934.8444552717887.308538228
#Sta/Elev= 30
       0   58.26  169.92   55.54  360.94   55.61  396.32   52.16  424.63   42.66
  460.02   42.55  502.48   49.47  523.71   48.02  544.95   39.86  573.25    38.3
  920.04   37.89  955.42   36.41 1075.74   39.49 1160.66   37.93 1172.31   36.59
    1190   28.69    1230   29.99 1245.59    38.1 1266.82   39.81 1489.31   36.62
 1629.42   40.24 1825.59   38.43 1934.26   42.07 2168.88   42.48    2316   46.91
 2596.23   48.57 2932.51   47.98 2988.56   49.65  3037.6   47.64 3358.09   48.11
#Mann= 5 ,-1 , 0
       0     .05       0  169.92      .1       0 1160.66    .038       0
 1245.59      .1       0 1934.26     .05       0
#XS Ineff= 2 , 0
             500   49.49
Permanent Ineff=
       F       F
Bank Sta=1160.66,1245.59
XS Rating Curve= 0 ,0
Exp/Cntr=0.3,0.1

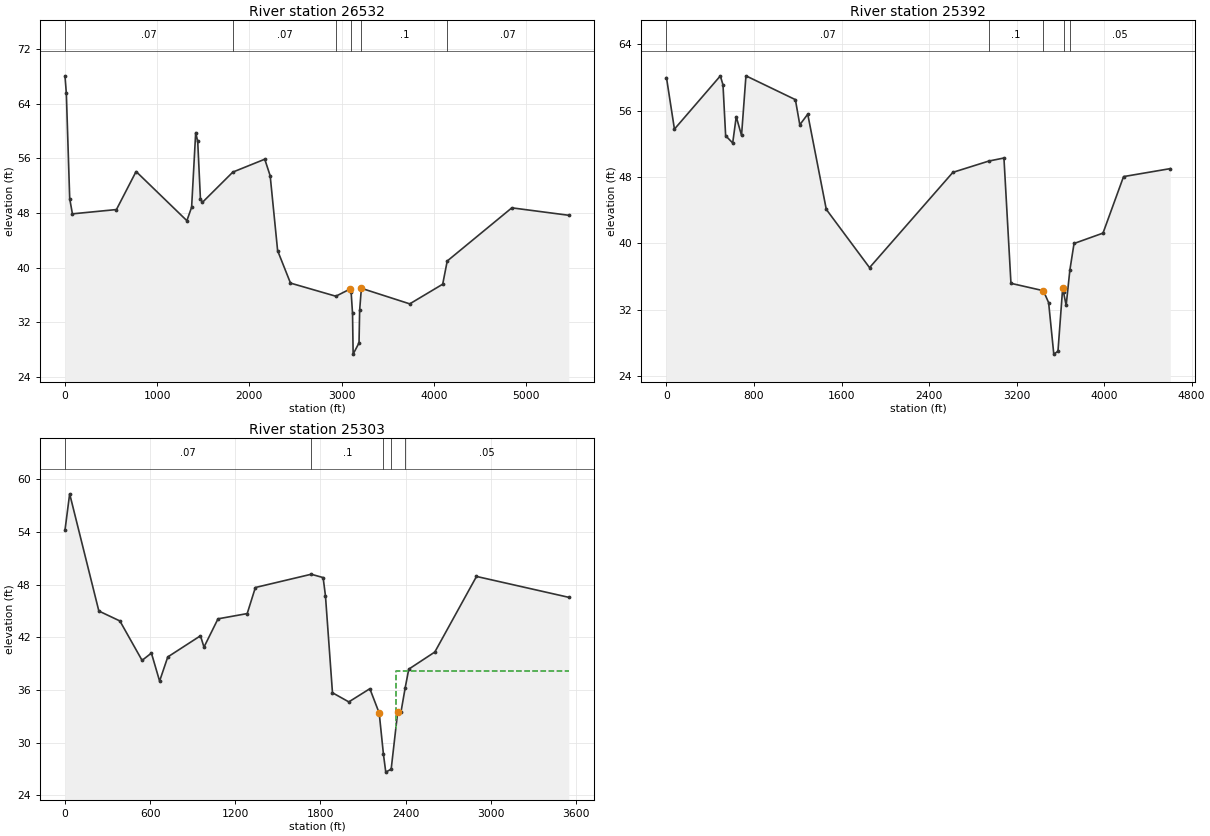
Type RM Length L Ch R = 1 ,26532   ,858.61,1139.52,426.2
BEGIN DESCRIPTION:
underwater portion from bigelk.dat hec2 model xsec 12 with -4 foot vertical adjustment
END DESCRIPTION:
XS GIS Cut Line= 4
1647196.50597318716509.4416392451644255.37915951717446.618208528
1643818.50825648717753.9518089291641976.51843312717853.969355926
#Sta/Elev= 30
       0   68.09   14.69   65.52   51.43   50.07   80.81   47.88  558.36   48.51
  771.41   54.08 1322.42   46.88 1373.85   48.85 1417.93   59.78 1439.97   58.48
 1469.36   50.08  1491.4   49.57 1821.1653.99677  2167.3   55.88 2226.08   53.45
 2306.89   42.49 2446.48   37.74 2938.33   35.82 3095.38   36.89 3103.94    36.5
 3119.56    33.3    3126   27.34    3190   28.99 3196.58   33.73  3215.2   36.98
 3740.14    34.7 4097.66   37.58 4146.79 40.9748 4847.76   48.76 5465.65   47.67
#Mann= 6 ,-1 , 0
       0     .07       0 1821.16     .07       0 2938.33      .1       0
 3103.94    .035       0  3215.2      .1       0 4146.79     .07       0
#XS Ineff= 2 , 0
         2126.67   49.84
Permanent Ineff=
       F       F
Bank Sta=3095.38,3215.2
XS Rating Curve= 0 ,0
Exp/Cntr=0.3,0.1

Type RM Length L Ch R = 1 ,25392   ,89.39,88.82,93.94
BEGIN DESCRIPTION:
underwater portion from bigelk.dat hec2 model xsec 11
END DESCRIPTION:
XS GIS Cut Line= 5
1646386.00956714715545.4421260211644308.67395268716736.723418176
1643792.30891635717143.905066162  1643163.447458 717493.35644497
1642387.38745469717796.433132678
#Sta/Elev= 30
       0   59.96   72.62   53.76  492.23   60.17  516.44   59.09  540.65   52.96
   605.2   52.09  637.48   55.26  685.89      53  726.24   60.18 1178.12   57.31
 1218.47   54.28 1291.09   55.56 1460.55   44.09 1855.95   37.07 2617.54   48.55
  2945.7   49.91  3084.3   50.28 3148.37   35.18 3444.66   34.29 3492.71   32.85
  3539.9   26.65    3578   26.99 3620.84   34.58 3628.85   34.11 3652.87   32.53
 3687.08    36.8 3724.95   39.98 3989.62   41.23 4177.49   48.04 4604.82      49
#Mann= 5 ,-1 , 0
       0     .07       0  2945.7      .1       0 3444.66    .035       0
 3628.85      .1       0 3687.08     .05       0
#XS Ineff= 2 , 0
         2326.09   43.05
Permanent Ineff=
       F       F
Bank Sta=3444.66,3620.84
XS Rating Curve= 0 ,0
Exp/Cntr=0.5,0.3

Type RM Length L Ch R = 1 ,25303   ,72.42,70.63,70.03
BEGIN DESCRIPTION:
underwater portion from bigelk.dat hec2 model xsec 11
END DESCRIPTION:
XS GIS Cut Line= 5
1645262.71070224716114.1495876761643375.66660669717280.404677883
1643233.53697577717352.8103389291642695.01361251717522.984475255
1642116.49383575717705.797534227
#Sta/Elev= 30
       0    54.2   32.92   58.35  238.64      45  386.76   43.87  543.11   39.38
  608.95   40.21  666.55   37.02  724.15   39.77  954.56   42.18  979.25   40.89
    1078   44.11 1283.72   44.71 1341.33   47.68 1734.91   49.19 1818.61   48.81
 1835.07   46.73 1884.44   35.69 1999.65   34.65 2147.77   36.15  2213.6   33.38
 2243.53   28.68  2259.9   26.65    2298   26.99 2344.05   33.52 2367.62   33.55
 2396.87   36.27 2421.91   38.38 2605.44   40.33 2899.08   48.94 3549.33   46.56
#Mann= 5 ,-1 , 0
       0     .07       0 1734.91      .1       0 2243.53    .038       0
    2298      .1       0 2396.87     .05       0
#XS Ineff= 2 , 0
       0 1034.78   42.63    2330       0   38.16
Permanent Ineff=
       F       F
Bank Sta=2213.6,2344.05
XS Rating Curve= 0 ,0
Exp/Cntr=0.5,0.3