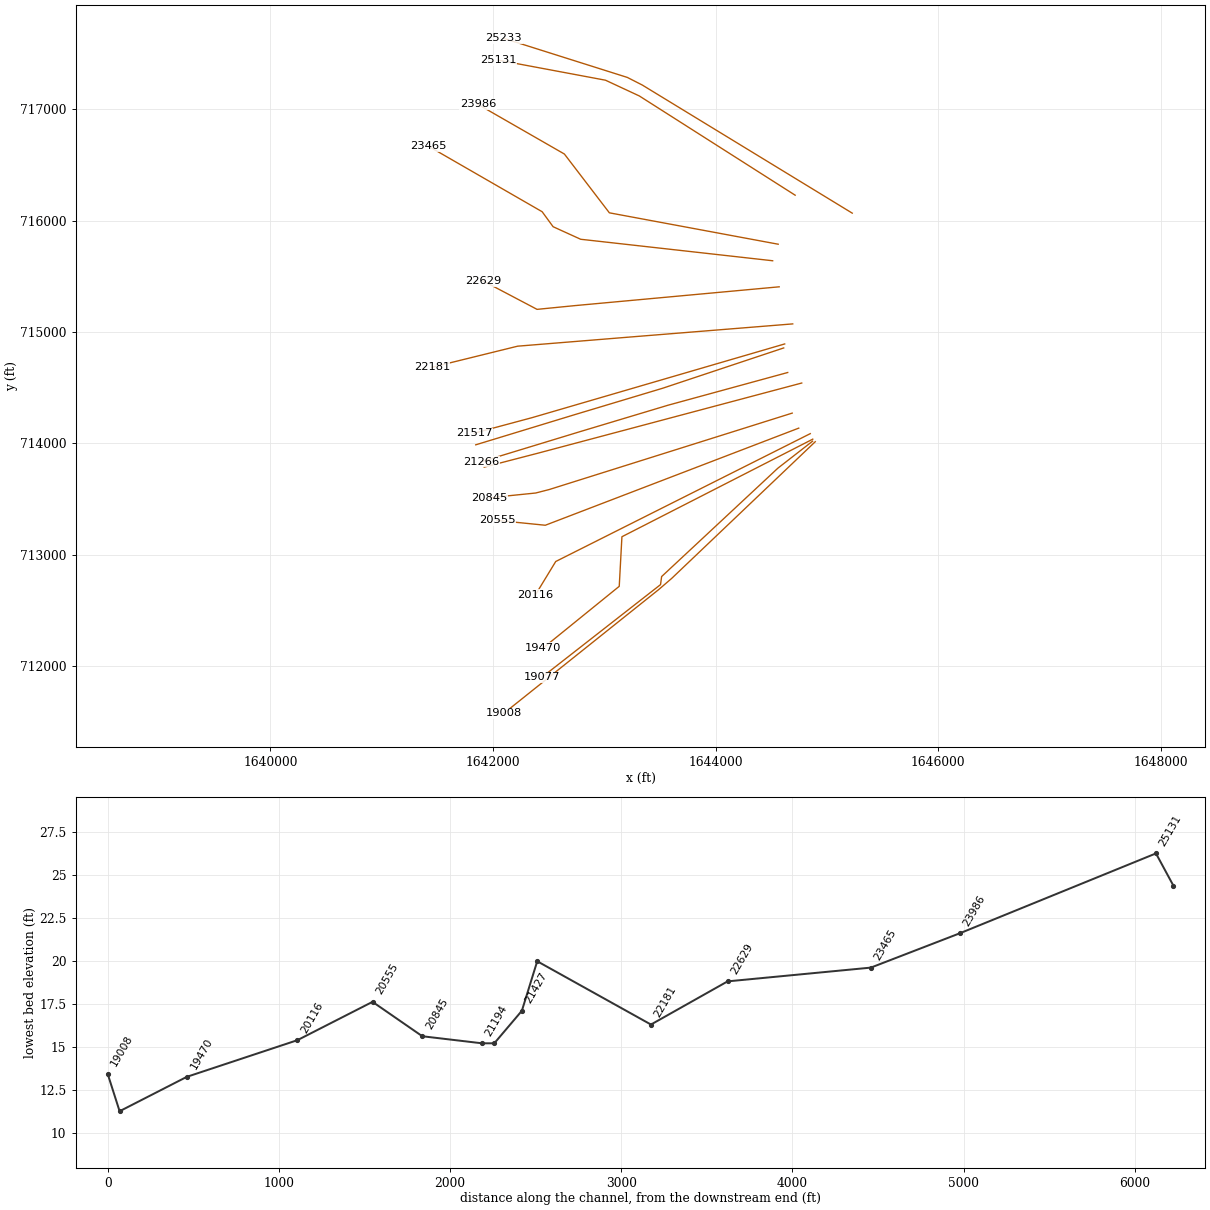
HEC-RAS study bigelkcreek.prj: Big Elk Creek

--- bigelkcreek.g23 (geometry) --- (continued)

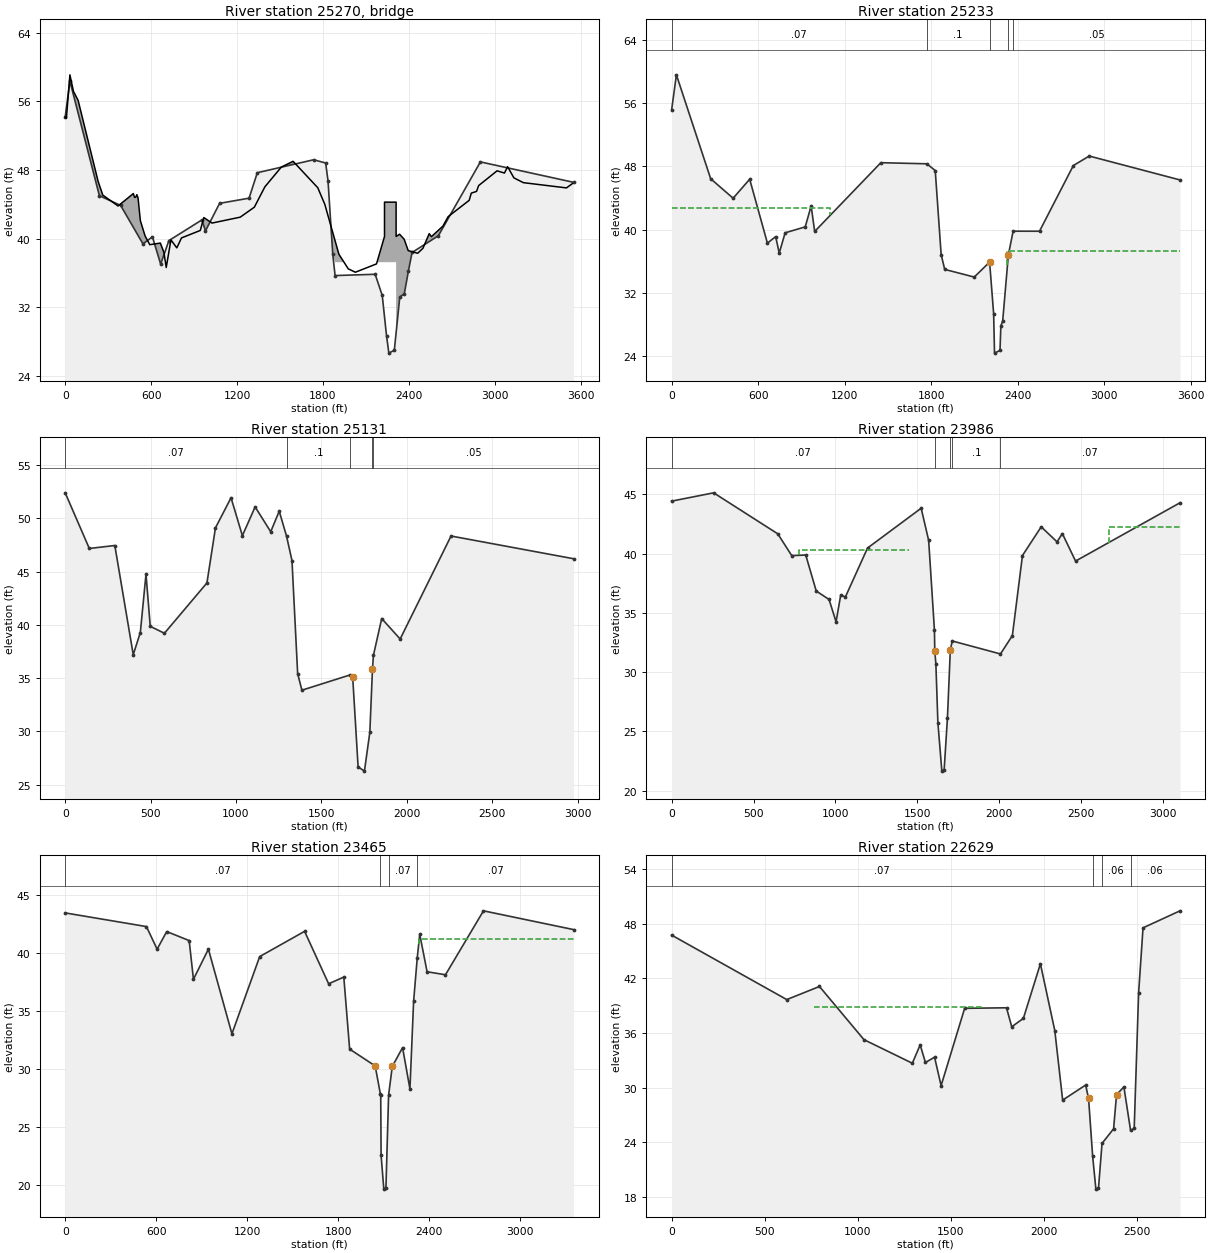
Type RM Length L Ch R = 3 ,25270   ,,,
BEGIN DESCRIPTION:
Ricketts Mill Rd CE0027  Approximate Reach.  81 foot span from bridge inspection report.  No piers.  Estimated railing ht to be 4'.
Top of road from LIDAR.
END DESCRIPTION:
Bridge Culvert--1,0,-1,-1, 0
Deck Dist Width WeirC Skew NumUp NumDn MinLoCord MaxHiCord MaxSubmerge Is_Ogee
20,27,2.6,0, 60, 60, , , 0.95, 0, 0,0,,
       0     8.2   32.81   57.42   90.22  229.66  262.47   369.1  475.73  483.93
  492.13  500.33  508.54  524.94  557.75  590.56  664.38  688.99  705.39   738.2
  779.21  812.02  943.25  967.86 1025.28 1222.13 1320.55 1394.37  1509.2 1591.22
 1763.47 1812.68 1911.11 1976.72 2025.94 2173.58 2229.49  2229.5  2310.5 2310.51
 2334.64 2366.95 2394.93    2461  2497.7 2541.75 2556.43 2637.18 2673.89 2820.71
 2835.39  2872.1 2886.78 3015.52 3066.91 3088.93 3132.98 3199.05 3500.03 3541.48
   54.15   54.02   59.09   57.17   56.11   46.68   45.07    43.8   45.25   44.81
   44.82   45.12   44.75   42.08   40.31   39.29   39.48    38.4   36.63   39.85
   38.92   40.08   40.95   42.45   41.81    42.5   43.66   46.04   48.34   49.01
   45.93   43.99   38.17   36.47   36.08   37.05   40.25   44.25   44.25   40.25
   40.51   39.92    38.6   38.29   38.87   40.58   40.22   41.45   42.56   44.46
    45.3    45.5   46.18    47.9   47.64   48.38   47.08   46.52   45.91   46.41
                                                                           37.25
   37.25
                                                                                
                                                           37.25   37.25
                                                                                
                                                                                
       0     8.2   32.81   57.42   90.22  229.66  262.47   369.1  475.73  483.93
  492.13  500.33  508.54  524.94  557.75  590.56  664.38  688.99  705.39   738.2
  779.21  812.02  943.25  967.86 1025.28 1222.13 1320.55 1394.37  1509.2 1591.22
 1763.47 1812.68 1911.11 1976.72 2025.94 2173.58 2229.49  2229.5  2310.5 2310.51
 2334.64 2366.95 2394.93    2461  2497.7 2541.75 2556.43 2637.18 2673.89 2820.71
 2835.39  2872.1 2886.78 3015.52 3066.91 3088.93 3132.98 3199.05 3500.03 3541.48
   54.15   54.02   59.09   57.17   56.11   46.68   45.07    43.8   45.25   44.81
   44.82   45.12   44.75   42.08   40.31   39.29   39.48    38.4   36.63   39.85
   38.92   40.08   40.95   42.45   41.81    42.5   43.66   46.04   48.34   49.01
   45.93   43.99   38.17   36.47   36.08   37.05   40.25   44.25   44.25   40.25
   40.51   39.92    38.6   38.29   38.87   40.58   40.22   41.45   42.56   44.46
    45.3    45.5   46.18    47.9   47.64   48.38   47.08   46.52   45.91   46.41
                                                                           37.25
   37.25
                                                                                
                                                           37.25   37.25
                                                                                
                                                                                
BR Coef=-1 , 0 , 0 ,, 0 ,,,0.8,0,,0,
WSPro=,,,, 1 ,,,, 0 ,,,, 0 ,,,,-1 ,-1 ,-1 , 0 , 0 , 0 , 0 , 0
BR U #Sta/Elev= 30
       0    54.2   32.92   58.35  238.64      45  386.76   43.87  543.11   39.38
  608.95   40.21  666.55   37.02  724.15   39.77  954.56   42.18  979.25   40.89
    1078   44.11 1283.72   44.71 1341.33   47.68 1734.91   49.19 1818.61   48.81
 1835.07   46.73 1867.98    38.2 1884.44   35.69 2164.23   35.84  2213.6   33.38
 2243.53   28.68  2259.9   26.65    2298   26.99  2336.2   33.19 2367.62   33.55
 2396.87   36.27 2421.91   38.38 2605.44   40.33 2899.08   48.94 3549.33   46.56
BR U #Mann= 5
       0     .07 1734.91      .1 2243.53    .032    2298      .1 2396.87     .07
BR D #Sta/Elev= 30
       0   55.17    32.8   59.56  270.61   46.43  426.41   43.97  541.22   46.37
  664.22    38.3  721.62   39.12  746.22   37.04  787.23    39.6  926.63   40.35
  967.63   42.99  992.23   39.77 1451.45   48.46 1770.12   48.32 1828.66   47.47
 1869.67   36.85 1894.27   34.98 2099.27   34.01 2205.88    35.9  2233.9   29.37
  2239.9    24.4    2278   24.74 2283.98   27.84 2296.64   28.46 2335.92   36.79
 2368.98  39.806 2552.03    39.8 2786.94    48.1 2897.06    49.3 3526.84   46.28
BR D #Mann= 5
       0     .07 1770.12      .1 2205.88    .032 2335.92      .1 2368.98     .07
BC Design=,, 0 ,, 0 ,,,,,,
BC Use User HTab Curves=0
BC User HTab FreeFlow(D)= 0

Type RM Length L Ch R = 1 ,25233   ,105.21,102.1,105.47
BEGIN DESCRIPTION:
underwater portion from bigelk.dat hec2 model xsec 10
END DESCRIPTION:
XS GIS Cut Line= 5
1645228.12326717716068.033007652 1643341.4081784717219.297155306
1643206.92260391 717287.808674411642673.92155454717456.237751812
1642095.40177771717639.050810769
#Sta/Elev= 30
       0   55.17    32.8   59.56  270.61   46.43  426.41   43.97  541.22   46.37
  664.22    38.3  721.62   39.12  746.22   37.04  787.23    39.6  926.63   40.35
  967.63   42.99  992.23   39.77 1451.45   48.46 1770.12   48.32 1828.66   47.47
 1869.67   36.85 1894.27   34.98 2099.27   34.01 2205.88    35.9  2233.9   29.37
  2239.9    24.4    2278   24.74 2283.98   27.84 2296.64   28.46 2335.92   36.79
 2368.9839.80608 2552.03    39.8 2786.94    48.1 2897.06    49.3 3526.84   46.28
#Mann= 5 ,-1 , 0
       0     .07       0 1770.12      .1       0 2205.88    .038       0
 2335.92      .1       0 2368.98     .05       0
#XS Ineff= 2 , 0
       0    1100   42.71    2330       0   37.25
Permanent Ineff=
       F       F
Bank Sta=2205.88,2335.92
XS Rating Curve= 0 ,0
Exp/Cntr=0.5,0.3

Type RM Length L Ch R = 1 ,25131   ,1073.46,1144.66,925.65
BEGIN DESCRIPTION:
underwater portion from bigelk.dat hec2 model xsec 9
END DESCRIPTION:
XS GIS Cut Line= 4
1644715.07631427716229.4410377891643314.79078957717121.153493673
1643010.63985828717262.7523000991642046.63073356 717443.26396887
#Sta/Elev= 30
       0   52.38  141.08   47.16  290.46   47.44  398.34    37.2  439.84   39.28
  473.03   44.75  497.93   39.86  580.92   39.21  829.88   43.93  879.68   49.09
  970.96   51.92 1037.35   48.36 1112.04   51.06 1203.33   48.73 1253.12   50.66
 1295.91   48.32 1327.81   46.03 1361.01   35.42  1385.9   33.87 1667.83    35.3
 1683.27    35.1    1715   26.68    1752   26.28 1783.65   29.92 1799.09   35.84
 1804.86   37.15 1853.14   40.59 1961.24   38.67  2259.1   48.33 2976.36    46.2
#Mann= 5 ,-1 , 0
       0     .07       0 1295.91      .1       0 1667.83    .038       0
 1799.09      .1       0 1804.86     .05       0
#XS Ineff= 2 , 0
          745.43   41.96
Permanent Ineff=
       F       F
Bank Sta=1683.27,1799.09
XS Rating Curve= 0 ,0
Exp/Cntr=0.3,0.1

Type RM Length L Ch R = 1 ,23986   ,512.18,520.66,519.47
BEGIN DESCRIPTION:
underwater portion from bigelk.dat hec2 model xsec 8 with 2 ft vertical adjustment
END DESCRIPTION:
XS GIS Cut Line= 4
1644562.49528578715788.9015983941643045.46623752 716071.02766633
1642641.19404195716599.3834070121641864.11389694717045.679436252
#Sta/Elev= 30
       0   44.43  256.32   45.13  647.92   41.67  733.36   39.83   818.8   39.88
  882.88   36.84   961.2   36.13 1003.92   34.24  1032.4    36.5 1060.88   36.34
 1196.16   40.47 1523.68   43.83 1569.48   41.11 1604.73   33.55 1606.77    31.8
 1613.55   30.68 1625.79   25.74    1650   21.64    1664   21.74 1684.06   26.09
 1701.69   31.84 1713.3332.62679 2007.95   31.53  2080.7   33.08 2142.39   39.84
 2256.75   42.26 2353.62   40.99 2385.91   41.69 2466.63   39.37 3104.43   44.29
#Mann= 5 ,-1 , 0
       0     .07       0 1606.77    .035       0 1701.69     .07       0
 1713.33      .1       0 2007.95     .07       0
#XS Ineff= 2 ,-1
  778.65 1449.3940.32613 2667.97 3616.8142.25026
Permanent Ineff=
       F       F
Bank Sta=1606.77,1701.69
XS Rating Curve= 0 ,0
Exp/Cntr=0.3,0.1

Type RM Length L Ch R = 1 ,23465   ,774.08,836.76,834.74
BEGIN DESCRIPTION:
underwater portion from bigelk.dat hec2 model xsec 8
END DESCRIPTION:
XS GIS Cut Line= 5
1644512.95599081715640.2837135051642787.45063433715833.422168911
1642539.88574751715946.1381921621642441.33954036716080.854459628
1641423.06840926716667.640446782
#Sta/Elev= 30
       0   43.49  535.32   42.31  605.76   40.36  669.15   41.88  817.07    41.1
  845.24   37.76  943.86   40.36 1098.82   33.05 1281.95   39.72 1577.79    41.9
 1736.28   37.37 1836.27   37.95 1874.72   31.73 2042.99   30.28 2077.68   27.83
 2079.68   27.75    2082   22.57    2100   19.64    2114   19.74 2131.56   27.76
 2155.73   30.23 2223.68   31.86 2272.16   28.29 2296.39   35.86 2320.52   39.63
 2336.79   41.64 2385.26   38.41 2506.45   38.15  2756.9   43.67 3350.45   42.05
#Mann= 4 ,-1 , 0
       0     .07       0 2077.68    .035       0 2131.56     .07       0
 2320.52     .07       0
#XS Ineff= 2 ,-1
  829.38 1636.4339.59843 2330.23 3371.9441.26806
Permanent Ineff=
       F       F
Bank Sta=2042.99,2155.73
XS Rating Curve= 0 ,0
Exp/Cntr=0.3,0.1

Type RM Length L Ch R = 1 ,22629   ,318.03,447.6,499.45
BEGIN DESCRIPTION:
underwater portion from bigelk.dat hec2 model xsec 8 with -0.8' adjustment
END DESCRIPTION:
XS GIS Cut Line= 4
1644571.50243033 715406.097955511642738.15229619715237.345799655
1642395.64014462715203.4723319111641911.84196033715458.233962104
#Sta/Elev= 30
       0   46.74   618.6   39.66  794.34    41.1 1033.35   35.26 1293.44   32.67
 1335.62   34.69 1363.74   32.75 1412.95   33.33 1448.09   30.21 1574.63    38.7
 1799.57   38.76 1827.69   36.67 1890.33    37.6 1981.78   43.59 2059.16   36.25
 2101.36   28.62 2224.84   30.27 2240.66    28.8 2262.41   22.49    2280   18.84
    2294   18.94 2312.95   23.86 2375.15   25.47 2390.97   29.21 2430.53   30.07
  2466.5   25.28  2485.9   25.51 2509.64   40.38 2533.37   47.54 2732.05   49.41
#Mann= 4 ,-1 , 0
       0     .07       0 2262.41    .035       0 2312.95     .06       0
  2466.5     .06       0
#XS Ineff= 1 ,-1
  763.36 1671.79    38.8
Permanent Ineff=
       F
Bank Sta=2240.66,2390.97
XS Rating Curve= 0 ,0
Exp/Cntr=0.3,0.1

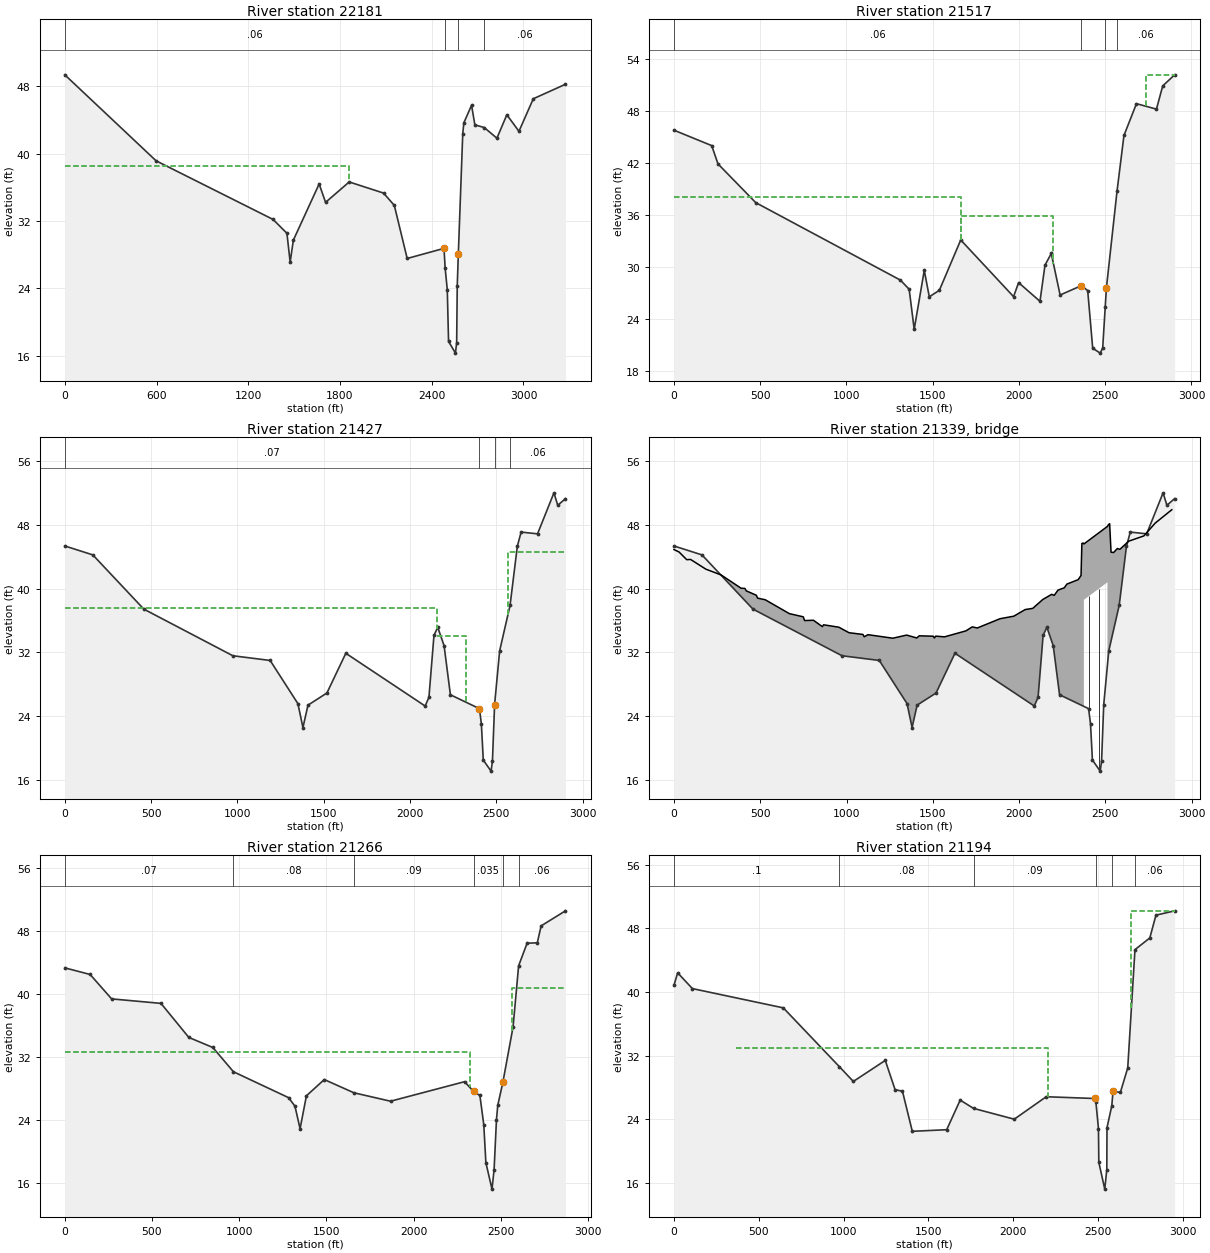
Type RM Length L Ch R = 1 ,22181   ,642.43,664.28,661.5
BEGIN DESCRIPTION:
underwater portion from bigelk.dat hec2 model xsec 7
END DESCRIPTION:
XS GIS Cut Line= 4
 1644693.0988816715072.8336075841643245.00631678714955.963911206
1642220.93187599714872.5787519511641449.51508021714682.440809324
#Sta/Elev= 30
       0   49.35  596.93   39.15 1362.41   32.19  1452.8   30.55 1473.87   27.13
 1494.94   29.74 1663.49    36.4 1705.63   34.22 1860.14   36.64 2084.89   35.32
 2155.12   33.86  2239.4   27.56 2480.27   28.76 2487.48   26.47 2501.68   23.85
    2510   17.72    2555   16.33    2563   17.56 2566.78   24.29 2573.99   28.12
 2602.83   42.35 2610.04   43.66  2660.5   45.74 2682.13   43.41 2743.27    43.1
 2826.32   41.83 2891.21   44.61 2970.51   42.65 3064.23   46.51 3274.77   48.23
#Mann= 4 ,-1 , 0
       0     .06       0 2487.48    .035       0 2573.99     .06       0
 2743.27     .06       0
#XS Ineff= 2 , 0
       0 1856.52    38.5               0
Permanent Ineff=
       F       F
Bank Sta=2480.27,2573.99
XS Rating Curve= 0 ,0
Exp/Cntr=0.3,0.1

Type RM Length L Ch R = 1 ,21517   ,97.81,89.7,91.73
BEGIN DESCRIPTION:
underwater portion from bigelk.dat hec2 model xsec 7
END DESCRIPTION:
XS GIS Cut Line= 3
1644621.04172532714892.690716818 1642353.2335709714231.009221867
1641831.54700705714090.901767567
#Sta/Elev= 30
       0   45.74  218.76   43.96  255.22   41.85  473.97   37.38 1312.54   28.44
 1363.58   27.38 1392.75   22.76 1451.08   29.56 1480.25   26.51 1538.58   27.26
 1662.55   33.07 1968.81   26.53 1997.97   28.15 2121.94   25.99  2151.1   30.17
 2187.56   31.51 2238.61   26.72 2362.37    27.8 2398.61   27.23  2427.6   20.58
 2471.09   20.01 2485.59   20.61 2500.08   25.31 2507.33   27.58 2568.46   38.67
  2608.8   45.13 2681.29    48.8 2797.25   48.17 2833.49   50.85 2902.54   52.13
#Mann= 4 ,-1 , 0
       0     .06       0 2362.37    .035       0 2500.08      .1       0
 2568.46     .06       0
#XS Ineff= 3 ,-1
       0 1665.25      38 1665.25 2200.13    35.8 2738.67 2902.54  52.128
Permanent Ineff=
       T       F       F
Bank Sta=2362.37,2507.33
XS Rating Curve= 0 ,0
Exp/Cntr=0.5,0.3

Type RM Length L Ch R = 1 ,21427   ,170.65,161.09,161.08
BEGIN DESCRIPTION:
underwater portion from bigelk.dat hec2 model xsec 7
END DESCRIPTION:
XS GIS Cut Line= 4
1644612.03458077714856.6621386861643524.65739827  714494.7181153
1642727.53167211714255.2714339791641844.63919175713986.228891805
#Sta/Elev= 30
       0   45.35  162.31   44.23  457.41   37.44  973.84   31.59 1189.89      31
 1350.69   25.59 1379.92   22.59 1409.16    25.4 1518.79   26.92 1628.43    31.9
 2088.11   25.29 2110.06   26.38 2139.33   34.16 2161.29   35.15 2197.88   32.85
 2234.47    26.7 2402.78   24.96  2413.9   23.05    2425   18.52    2470   17.13
    2478   18.36 2490.59   25.48 2519.86   32.21 2580.15    37.9 2622.31   45.31
 2644.27   47.09  2739.4   46.87 2834.53   52.01 2856.49   50.45 2901.33   51.28
#Mann= 4 ,-1 , 0
       0     .07       0 2402.78    .035       0 2490.59      .1       0
 2580.15     .06       0
#XS Ineff= 3 ,-1
 2157.84    2325   34.08       0 2157.84   37.56    2567 2901.33   44.57
Permanent Ineff=
       T       F       F
Bank Sta=2402.78,2490.59
XS Rating Curve= 0 ,0
Exp/Cntr=0.5,0.3

Type RM Length L Ch R = 3 ,21339   ,,,
BEGIN DESCRIPTION:
Elkton Rd  CE050207PF-4   Pier locations from Bridge Inspection Report.  Top of road from LIDAR.
END DESCRIPTION:
Bridge Culvert--1,0,-1,-1, 0
Deck Dist Width WeirC Skew NumUp NumDn MinLoCord MaxHiCord MaxSubmerge Is_Ogee
55,66,2.6,0, 60, 60, , , 0.95, 0, 0,0,,
       0   29.61   74.02   96.23  185.05  273.88  389.18  411.23  418.59  477.41
  484.76  528.88  668.59  749.47  756.82   808.3  859.77  867.12  955.35 1014.18
 1095.06 1102.41 1124.47 1268.07 1348.47 1406.94 1421.56 1501.96 1509.27 1516.57
 1567.74 1691.99 1728.53 1757.77 1889.33 1969.44  2035.3 2079.21 2137.75 2188.97
 2203.61 2225.56 2262.15 2276.79 2342.65    2359 2363.84 2371.15  2375.5    2512
 2517.51 2524.83 2532.91 2547.55  2569.5 2584.14 2635.36 2723.18 2789.04 2884.95
    44.9   44.59   43.63   43.66   42.44   41.71   40.05   40.03   39.73   39.17
   38.81   38.61   36.87   36.47      36   36.04   35.24   35.47   35.17   34.48
   34.26   33.97   34.23   33.79   34.18   33.82   34.09   34.04   33.82   34.05
   33.96   34.71   35.21   35.07   36.23   36.55   37.38   37.53   38.65   39.29
   39.16   39.82   40.11   40.57   41.13   41.66   45.66   45.72    45.6    47.8
      48   48.14   44.57   44.53   45.03   44.93   45.95   46.61   48.22   49.89
                                                                                
                                                                                
                                                                                
                                                                                
                                                                    38.6    40.8
                                                                                
       0   29.61   74.02   96.23  185.05  273.88  389.18  411.23  418.59  477.41
  484.76  528.88  668.59  749.47  756.82   808.3  859.77  867.12  955.35 1014.18
 1095.06 1102.41 1124.47 1268.07 1348.47 1406.94 1421.56 1501.96 1509.27 1516.57
 1567.74 1691.99 1728.53 1757.77 1889.33 1969.44  2035.3 2079.21 2137.75 2188.97
 2203.61 2225.56 2262.15 2276.79 2342.65    2359 2363.84 2371.15  2375.5    2512
 2517.51 2524.83 2532.91 2547.55  2569.5 2584.14 2635.36 2723.18 2789.04 2884.95
    44.9   44.59   43.63   43.66   42.44   41.71   40.05   40.03   39.73   39.17
   38.81   38.61   36.87   36.47      36   36.04   35.24   35.47   35.17   34.48
   34.26   33.97   34.23   33.79   34.18   33.82   34.09   34.04   33.82   34.05
   33.96   34.71   35.21   35.07   36.23   36.55   37.38   37.53   38.65   39.29
   39.16   39.82   40.11   40.57   41.13   41.66   45.66   45.72    45.6    47.8
      48   48.14   44.57   44.53   45.03   44.93   45.95   46.61   48.22   49.89
                                                                                
                                                                                
                                                                                
                                                                                
                                                                    38.6    40.8
                                                                                
Pier Skew, UpSta & Num, DnSta & Num=  ,2403.75, 2 ,2403.75, 2 , 0 , 0 , 0 ,,
     2.5     2.5
       0      40
     2.5     2.5
       0      40
Pier Skew, UpSta & Num, DnSta & Num=  ,2464.25, 2 ,2464.25, 2 , 0 , 0 , 0 ,,
     2.5     2.5
       0      40
     2.5     2.5
       0      40
BR Coef=-1 , 1 , 0 ,, 0 ,,,0.8,0,0.5,0,
WSPro=,,,, 1 ,,,, 0 ,,,, 0 ,,,,-1 ,-1 ,-1 , 0 , 0 , 0 , 0 , 0
BR U #Sta/Elev= 30
       0   45.35  162.31   44.23  457.41   37.44  973.84   31.59 1189.89      31
 1350.69   25.59 1379.92   22.59 1409.16    25.4 1518.79   26.92 1628.43    31.9
 2088.11   25.29 2110.06   26.38 2139.33   34.16 2161.29   35.15 2197.88   32.85
 2234.47    26.7 2402.78   24.96  2413.9   23.05    2425   18.52    2470   17.13
    2478   18.36 2490.59   25.48 2519.86   32.21 2580.15    37.9 2622.31   45.31
 2644.27   47.09  2739.4   46.87 2834.53   52.01 2856.49   50.45 2901.33   51.28
BR U #Mann= 4
       0     .07 2402.78    .032 2490.59     .07 2580.15     .07
BR D #Sta/Elev= 30
       0   43.33  145.13   42.49   268.5   39.39  551.51   38.82  711.16    34.5
  849.04   33.22  870.81   31.53  967.14   30.14 1283.47   26.85 1320.01   25.77
 1349.25   22.91 1385.79   27.09 1488.12   29.15 1658.04  27.471 1868.18    26.4
 2292.83   28.88 2387.97    26.2 2402.92   23.43    2415   18.61    2450   15.24
  2462.1   17.69 2475.78   24.07 2490.42   27.07 2541.64   31.45 2570.91   35.83
 2602.78   43.59 2651.41   46.46 2709.95   46.51 2731.91   48.66 2871.56   50.57
BR D #Mann= 6
       0      .1  967.14     .08 1658.04      .1 2387.97    .032 2490.42     .01
 2602.78     .07
BC Design=,, 0 ,, 0 ,,,,,,
BC Use User HTab Curves=0
BC User HTab FreeFlow(D)= 0

Type RM Length L Ch R = 1 ,21266   ,76.75,72.03,69.21
BEGIN DESCRIPTION:
underwater portion from bigelk.dat hec2 model xsec 6
END DESCRIPTION:
XS GIS Cut Line= 4
1644648.06315893714635.9870974721643572.16637015714341.926486447
 1642773.8665224714102.1271135961641891.27837746713833.177311093
#Sta/Elev= 30
       0   43.33  145.13   42.49   268.5   39.39  551.51   38.82  711.16    34.5
  849.04   33.22  967.14   30.14 1283.47   26.85 1320.01   25.77 1349.25   22.91
 1385.79   27.09 1488.12   29.15 1658.0427.47116 1868.18    26.4 2292.83   28.88
 2344.06   27.64 2380.65   27.13 2402.92   23.43    2415   18.61    2450   15.24
  2462.1   17.69 2475.78   24.07  2483.1   25.87 2512.37   28.79 2570.91   35.83
 2602.78   43.59 2651.41   46.46 2709.95   46.51 2731.91   48.66 2871.56   50.57
#Mann= 6 ,-1 , 0
       0     .07       0  967.14     .08       0 1658.04     .09       0
 2344.06    .035       0 2512.37      .1       0 2602.78     .06       0
#XS Ineff= 2 , 0
       0 2321.74    32.7    2567       0    40.8
Permanent Ineff=
       T       F
Bank Sta=2344.06,2512.37
XS Rating Curve= 0 ,0
Exp/Cntr=0.5,0.3

Type RM Length L Ch R = 1 ,21194   ,342.17,348.35,332.05
BEGIN DESCRIPTION:
underwater portion from bigelk.dat hec2 model xsec 6
END DESCRIPTION:
XS GIS Cut Line= 3
1644774.16318244714541.4120798111642405.16792227713911.360157058
1641920.61221465713785.682884187
#Sta/Elev= 30
       0   40.83   21.73    42.4  108.65   40.42  644.66      38  975.03   30.62
 1057.53   28.76 1245.85    31.4  1303.8   27.73 1347.26   27.53 1405.21    22.5
 1608.02    22.7 1687.69   26.42 1766.14   25.38  2006.4   24.02 2194.73   26.84
 2480.27   26.62  2487.5   26.23 2502.95   22.83    2505   18.61    2540   15.24
  2552.1   17.69 2553.13   22.94 2581.52   25.71 2588.75   27.51 2632.14   27.39
 2675.53   30.46 2718.15   45.31  2805.7   46.78 2841.86   49.64 2951.94   50.18
#Mann= 6 ,-1 , 0
       0      .1       0  975.03     .08       0 1766.14     .09       0
  2487.5    .035       0 2581.52      .1       0 2718.15     .06       0
#XS Ineff= 2 ,-1
  363.17 2206.3532.91013 2697.17 2951.94  50.184
Permanent Ineff=
       T       F
Bank Sta=2480.27,2588.75
XS Rating Curve= 0 ,0
Exp/Cntr=0.3,0.1

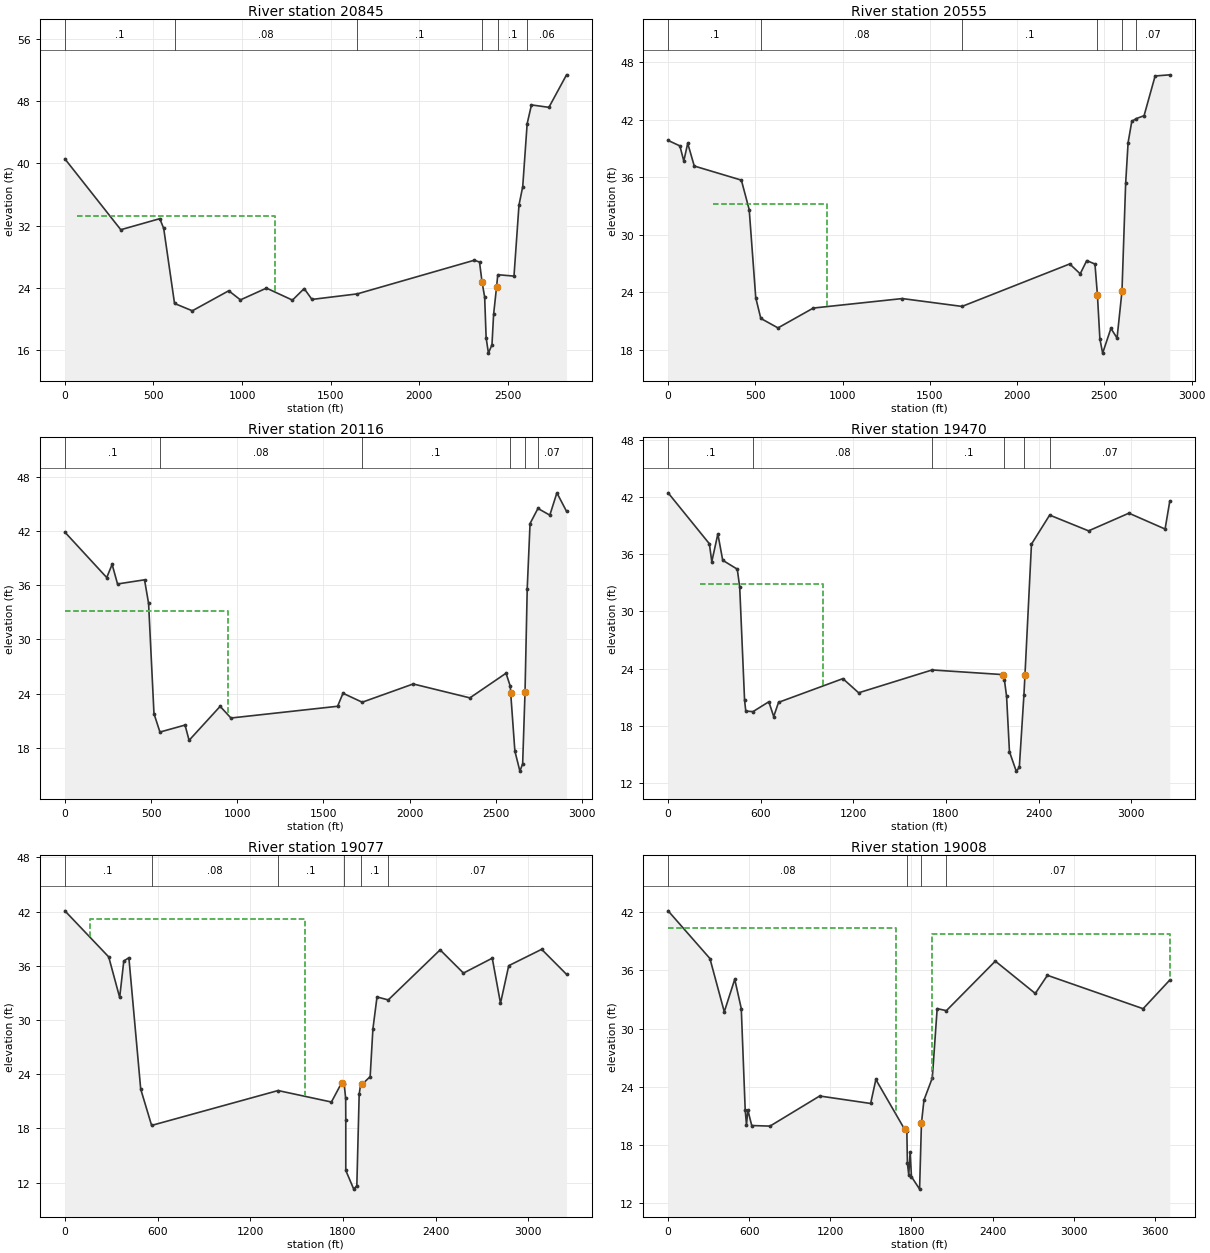
Type RM Length L Ch R = 1 ,20845   ,298.58,290.73,264.78
BEGIN DESCRIPTION:
underwater portion from bigelk.dat hec2 model xsec 5
END DESCRIPTION:
XS GIS Cut Line= 4
1644688.59530935714271.1977436841642504.96017659713584.329357997
1642383.36755458 713553.091044561641969.40484434713510.949609146
#Sta/Elev= 30
       0   40.57  315.54   31.48  535.68    32.9   557.7   31.64   618.8   22.02
  719.14   21.08  924.61   23.65  990.65   22.48 1137.41   23.99 1284.17   22.45
 1350.22   23.93 1394.25   22.54 1650.05   23.25  2310.8   27.57 2339.71   27.33
 2354.16   24.74 2368.71   22.85    2377   17.63    2390   15.65    2410   16.72
 2419.16   20.61 2435.76   24.11  2442.8   25.71 2534.27   25.53 2562.42   34.64
 2583.52   37.01 2608.54   45.08 2632.78   47.49 2731.28   47.18 2830.76   51.35
#Mann= 6 ,-1 , 0
       0      .1       0   618.8     .08       0 1650.05      .1       0
 2354.16    .035       0  2442.8      .1       0 2608.54     .06       0
#XS Ineff= 1 ,-1
      69 1185.46 33.2608
Permanent Ineff=
       T
Bank Sta=2354.16,2435.76
XS Rating Curve= 0 ,0
Exp/Cntr=0.3,0.1

Type RM Length L Ch R = 1 ,20555   ,356.21,439.16,522.74
BEGIN DESCRIPTION:
underwater portion from bigelk.dat hec2 model xsec 5
END DESCRIPTION:
XS GIS Cut Line= 3
1644747.14174882714136.0905755911642469.72683688713263.371260822
1642036.27760933713307.080426618
#Sta/Elev= 30
       0   39.83   67.47   39.26   89.96   37.68  112.45   39.53  149.93   37.16
   419.8   35.69  464.77   32.61  502.26   23.42  531.21   21.27  629.69   20.28
   832.1   22.35 1341.85   23.34 1684.19   22.52 2301.38   26.95 2361.35   25.92
 2398.83    27.3 2445.93   26.94    2460   23.73 2474.08   19.14    2490   17.65
 2537.39   20.23 2572.57   19.22 2600.71    24.1 2621.82   35.36 2635.89   39.61
    2657   41.82 2682.5242.10372 2727.35   42.41 2790.67   46.55 2874.54   46.67
#Mann= 6 ,-1 , 0
       0      .1       0  531.21     .08       0 1684.19      .1       0
    2460    .035       0 2600.71      .1       0 2682.52     .07       0
#XS Ineff= 1 ,-1
  255.59  908.93  33.237
Permanent Ineff=
       T
Bank Sta=2460,2600.71
XS Rating Curve= 0 ,0
Exp/Cntr=0.3,0.1

Type RM Length L Ch R = 1 ,20116   ,461.51,645.57,672.69
BEGIN DESCRIPTION:
underwater portion from bigelk.dat hec2 model xsec 4
END DESCRIPTION:
XS GIS Cut Line= 3
1644850.72391102714086.5512806181642563.41824964712937.593179628
1642380.86217698712637.773722872
#Sta/Elev= 30
       0   41.88  242.84   36.85  274.17   38.31  305.51   36.14  462.18    36.6
  485.68   33.99  517.01   21.78  551.5719.74589  697.18   20.52  720.68   18.83
  900.85   22.59  963.52    21.3 1582.37    22.6  1613.7   24.04 1725.16   23.05
 2021.04   25.07 2350.05   23.53 2559.66   26.26 2584.25   24.82 2586.44   24.12
    2611   17.64    2640   15.42    2656   16.22  2669.8   24.15 2682.59   35.62
 2698.98   42.83 2744.78    44.5 2813.72   43.76  2854.7   46.23 2910.69   44.18
#Mann= 6 ,-1 , 0
       0      .1       0  551.57     .08       0 1725.16      .1       0
 2584.25    .035       0  2669.8      .1       0 2744.78     .07       0
#XS Ineff= 2 , 0
       0  945.65   33.19               0
Permanent Ineff=
       T       F
Bank Sta=2586.44,2669.8
XS Rating Curve= 0 ,0
Exp/Cntr=0.3,0.1

Type RM Length L Ch R = 1 ,19470   ,441.76,392.63,337.81
BEGIN DESCRIPTION:
underwater portion from bigelk.dat hec2 model xsec 3 with 2' vertical adjustment
END DESCRIPTION:
XS GIS Cut Line= 4
1644873.24177238714037.0119856751643158.30940332713160.122183874
1643134.20056191712714.6327240021642452.64594817712162.233643293
#Sta/Elev= 30
       0   42.42  267.31   37.09  283.03   35.21  322.34   38.12  353.79   35.36
  448.13   34.43  463.86   32.55  495.31   20.73  503.17   19.57  550.15   19.52
  652.55   20.55  683.99      19  715.44   20.49 1132.13   22.97 1234.34   21.49
 1710.25   23.88 2171.48   23.39 2178.49   22.84 2192.51   21.12 2211.21   15.32
    2255   13.29    2275   13.67 2304.68   21.21 2311.69   23.36 2353.75   37.05
 2471.62   40.09 2723.67   38.44 2984.98   40.29 3219.25   38.63 3249.57   41.54
#Mann= 6 ,-1 , 0
       0      .1       0  550.15     .08       0 1710.25      .1       0
 2178.49    .045       0 2304.68      .1       0 2471.62     .07       0
#XS Ineff= 1 ,-1
   205.4 1001.9132.89802
Permanent Ineff=
       T
Bank Sta=2171.48,2311.69
XS Rating Curve= 0 ,0
Exp/Cntr=0.3,0.1

Type RM Length L Ch R = 1 ,19077   ,81.52,69.86,35.56
BEGIN DESCRIPTION:
underwater portion from bigelk.dat hec2 model xsec 3
END DESCRIPTION:
XS GIS Cut Line= 5
1644871.52187915714018.7702884971644559.57974394713776.124243394
1643515.01199989712802.2433570331643505.31327973 712729.87598376
 1642440.3656996711898.208298907
#Sta/Elev= 30
       0   42.09  283.79   36.99  354.73    32.5  381.34   36.53  414.34    36.9
  490.91   22.36   561.5   18.34 1380.21    22.2 1725.49   20.93 1792.49   23.08
 1808.05   22.93 1817.77   21.32 1818.49   18.92 1818.49   13.36    1870   11.29
    1890   11.67 1905.24   21.79 1914.12   22.82    1923   22.87 1976.29   23.74
 1994.05   29.02  2020.7   32.56 2093.38   32.23 2429.25   37.77 2580.24    35.2
 2766.75   36.85 2820.04   31.86 2873.33   36.02 3086.49   37.83 3247.56   35.06
#Mann= 6 ,-1 , 0
       0      .1       0   561.5     .08       0 1380.21      .1       0
 1808.05     .04       0 1914.12      .1       0 2093.38     .07       0
#XS Ineff= 1 ,-1
  164.04 1556.2541.20498
Permanent Ineff=
       F
Bank Sta=1792.49,1923
XS Rating Curve= 0 ,0
Exp/Cntr=0.5,0.3

Type RM Length L Ch R = 1 ,19008   ,143.62,170.05,170.21
BEGIN DESCRIPTION:
underwater portion from bigelk.dat hec2 model xsec 2.3
END DESCRIPTION:
XS GIS Cut Line= 4
1644895.75963369714014.0437670951643605.42522618712785.720729813
1643488.07457535712684.7977469561642096.51873948711572.781711638
#Sta/Elev= 30
       0   42.13  309.27   37.22  415.58   31.73  492.89   35.08  541.21   32.07
  570.21   21.64  579.87   20.08  589.54   21.63  618.53   20.02  753.83   19.96
 1121.09   23.06 1498.01   22.29 1536.66   24.76 1749.28   19.63 1765.84    19.5
    1770   16.12    1780   14.94  1790.1   17.32    1800   14.75    1860   13.47
 1873.83   20.24 1892.29   22.63  1954.2   24.92 1990.04   32.06 2058.41   31.85
 2420.15   36.95 2715.84   33.62 2805.45   35.49 3513.32   32.05 3710.45      35
#Mann= 4 ,-1 , 0
       0     .08       0 1765.84     .04       0 1873.83      .1       0
 2058.41     .07       0
#XS Ineff= 2 ,-1
       0    1683   40.39    1949    4000   39.78
Permanent Ineff=
       F       F
Bank Sta=1749.28,1873.83
XS Rating Curve= 0 ,0
Exp/Cntr=0.5,0.3