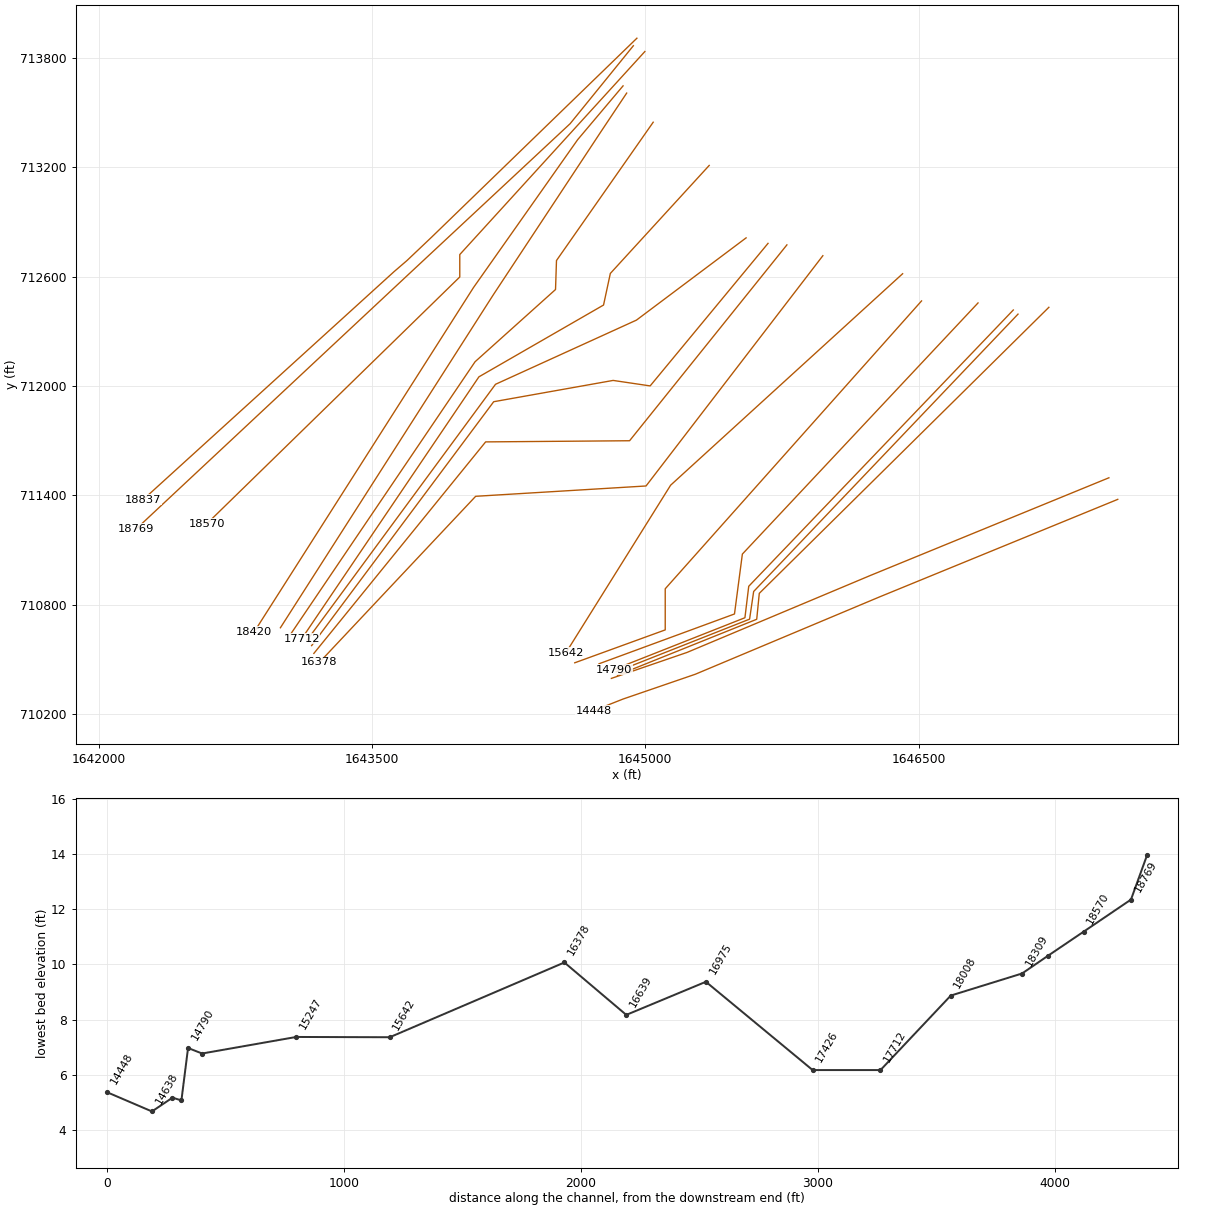
HEC-RAS study bigelkcreek.prj: Big Elk Creek

--- bigelkcreek.g23 (geometry) --- (continued)

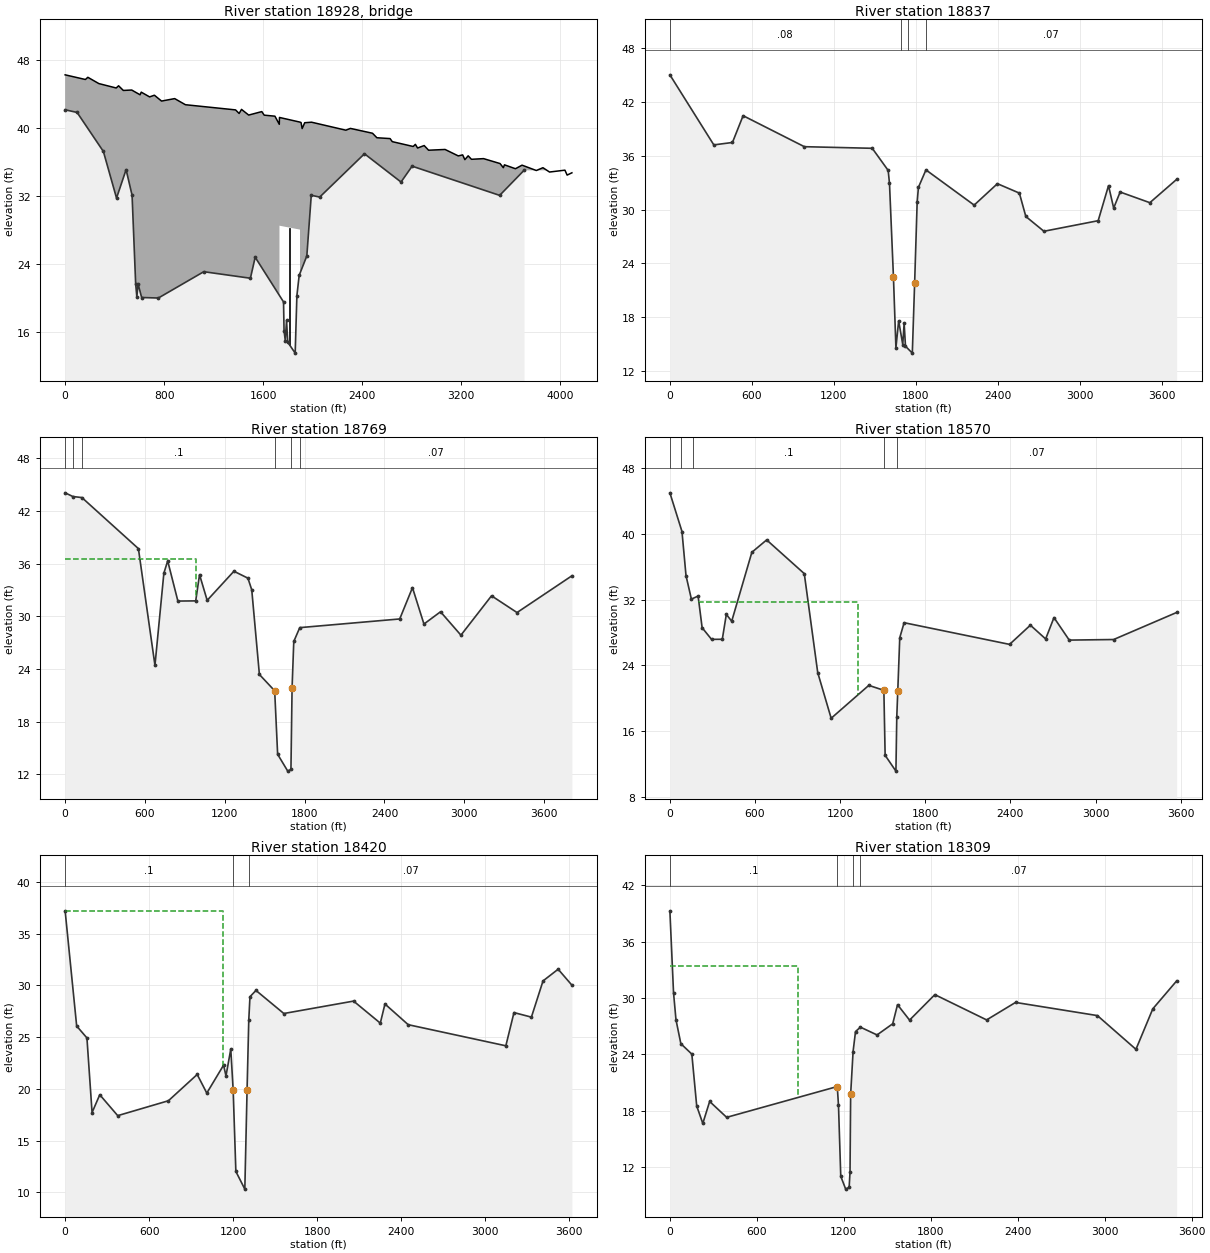
Type RM Length L Ch R = 3 ,18928   ,,,
BEGIN DESCRIPTION:
Conrail RR  CE050907FS-4  Geometry taken from existing HEC2  model. Top of road from LIDAR.
END DESCRIPTION:
Bridge Culvert--1,0,-1,-1, 0
Deck Dist Width WeirC Skew NumUp NumDn MinLoCord MaxHiCord MaxSubmerge Is_Ogee
50,60,2.6,0, 60, 60, , , 0.95, 0, 0,0,,
       0  163.87  183.62   272.5   412.8   432.1   470.7  538.25   605.8  615.45
  683.01  721.61  779.51  885.66  972.51 1377.83 1406.78 1426.08 1483.98 1590.13
 1609.43 1696.28 1731.56  1732.9    1733    1899  1899.1 1907.54 1916.22 1937.14
 1992.53 2269.51 2306.44 2485.05 2520.61  2627.3 2645.08    2814 2831.78 2849.56
 2902.91 2938.47 3071.83 3178.51 3214.08 3231.86 3258.53  3285.2    3383 3516.36
 3543.03 3551.92 3640.83 3694.17 3809.75 3863.09 3916.44 4040.91 4058.69 4097.23
   46.25    45.7   45.96   45.22    44.7   44.96   44.41   44.46    43.9   44.21
   43.65   43.85   43.16   43.45   42.73   42.12    41.7   42.18   41.51   41.92
    41.5   41.38   40.42   41.23   41.23   40.68   40.68   40.63   39.92   40.61
   40.67   39.73   39.94   39.37   38.84   38.74   38.38   37.81   38.06   37.63
   37.92   37.37   37.46    36.7   36.82   36.26   36.71    36.3   36.38    35.8
   35.31   35.65   35.19   35.61   34.98   35.31    34.8   35.02   34.44   34.71
                                                                                
                                                                                
                               0   28.48   28.02       0
                                                                                
                                                                                
                                                                                
       0  266.62   357.1   395.7  463.25   530.8  540.45  608.01  646.61  704.51
  810.66  897.51 1302.83 1331.78 1351.08 1408.98 1515.13 1534.43 1611.63 1617.33
 1626.56  1627.9    1628    1794  1794.1 1802.54 1811.22 1815.97 1825.21 2194.51
 2231.44 2401.16 2410.05 2445.61  2552.3 2570.08    2739 2756.78 2774.56 2827.91
 2863.47 2996.83 3103.51 3139.08 3156.86 3183.53  3210.2    3308 3441.36 3468.03
 3476.92 3565.83 3619.17 3734.75 3788.09 3832.55 3841.44 3965.91 3983.69 4022.23
   46.25   44.94   44.96   44.41   44.46    43.9   44.21   43.65   43.85   43.16
   43.45   42.73   42.12    41.7   42.18   41.51   41.92    41.5    41.4   40.38
   40.42   41.23   41.23   40.68   40.68   40.63   39.92   40.45   40.68   39.73
   39.94   39.12   39.37   38.84   38.74   38.38   37.81   38.06   37.63   37.92
   37.37   37.46    36.7   36.82   36.26   36.71    36.3   36.38    35.8   35.31
   35.65   35.19   35.61   34.98   35.31   35.16    34.8   35.02   34.44   34.71
                                                                                
                                                                                
               0   28.48   28.02       0
                                                                                
                                                                                
                                                                                
Pier Skew, UpSta & Num, DnSta & Num=  ,1816, 2 ,1725, 2 , 0 , 0 , 0 ,,
     5.2     5.2
       0      30
     5.2     5.2
       0      30
BR Coef=-1 , 1 , 0 ,, 0 ,,,0.8,0,0.5,0,
WSPro=,,,, 1 ,,,, 0 ,,,, 0 ,,,,-1 ,-1 ,-1 , 0 , 0 , 0 , 0 , 0
BR U #Sta/Elev= 30
       0   42.13   96.65   41.82  309.27   37.22  415.58   31.73  492.89   35.08
  541.21   32.07  570.21   21.64  579.87   20.08  589.54   21.63  618.53   20.02
  753.83   19.96 1121.09   23.06 1498.01   22.29 1536.66   24.76 1765.84    19.5
    1770   16.12    1780   14.94  1790.1   17.32    1800   14.75    1860   13.47
 1873.83   20.24 1892.29   22.63  1954.2   24.92 1990.04   32.06 2058.41   31.85
 2420.15   36.95 2715.84   33.62 2805.45   35.49 3513.32   32.05 3710.45      35
BR U #Mann= 4
       0     .08 1765.84    .032 1873.83     .01 2058.41     .07
BR D #Sta/Elev= 30
       0   45.04  321.69   37.22  458.16   37.49  536.15   40.48  984.56   37.02
 1530.45    36.1 1598.25   34.37 1617.55   29.91    1655   14.58    1675   17.59
    1695   16.12    1705   14.94  1715.1   17.32    1725   14.75    1745   15.37
    1775   13.98 1810.47   30.83 1828.93   33.34 1874.79   34.43 2227.76    30.5
    2398   32.89 2558.79   31.84 2606.09   29.23  2738.5   27.58 3135.75   28.76
 3211.41   32.67 3249.25   30.17 3296.54   31.96 3514.08   30.77 3710.25   33.37
BR D #Mann= 4
       0     .08    1695    .032    1745     .08 1874.79     .07
BC Design=,, 0 ,, 0 ,,,,,,
BC Use User HTab Curves=0
BC User HTab FreeFlow(D)= 0

Type RM Length L Ch R = 1 ,18837   ,72.66,68.65,73.08
BEGIN DESCRIPTION:
underwater portion from bigelk.dat hec2 model xsec 2
END DESCRIPTION:
XS GIS Cut Line= 5
1644954.25511341713909.2704195831643827.36000307712817.113157809
1643692.60375014712689.2322239131643621.06695825712627.709715322
1642243.88172244 711376.29773441
#Sta/Elev= 30
       0   45.04  321.69   37.22  458.16   37.49  536.15   40.48  984.56   37.02
 1481.71   36.84 1598.25   34.37  1607.9   32.92 1636.85   22.48    1655   14.58
    1675   17.59    1705   14.94  1715.1   17.32    1725   14.75    1775   13.98
    1792   21.81 1810.47   30.83  1819.7   32.48 1874.79   34.43 2227.76    30.5
    2398   32.89 2558.79   31.84 2606.09   29.23  2738.5   27.58 3135.75   28.76
 3211.41   32.67 3249.25   30.17 3296.54   31.96 3514.08   30.77 3710.25   33.37
#Mann= 4 ,-1 , 0
       0     .08       0 1689.28     .04       0 1739.74     .08       0
 1874.79     .07       0
#XS Ineff= 2 , 0
       0    1578   28.48    1844       0   28.02
Permanent Ineff=
       F       F
Bank Sta=1636.85,1792
XS Rating Curve= 0 ,0
Exp/Cntr=0.5,0.3

Type RM Length L Ch R = 1 ,18769   ,143.09,199.21,244.74
BEGIN DESCRIPTION:
underwater portion from bigelk.dat hec2 model xsec 1
END DESCRIPTION:
XS GIS Cut Line= 4
1644934.78847006713867.9038024541644587.89662191713440.276269227
1643698.25187618712610.6951657981642207.04097666711216.654502928
#Sta/Elev= 30
       0   44.08   57.89   43.66  126.06   43.54  550.64   37.72  675.06   24.41
  742.06   34.92  770.77   36.32  847.34   31.74  981.34   31.76 1010.05   34.75
 1067.48   31.82 1268.47   35.14 1373.76   34.35 1402.47   33.02  1459.9   23.37
 1574.75   21.51    1597   14.27    1673   12.35    1697   12.54 1705.54   21.84
 1718.32   27.13 1763.28   28.71 2514.48    29.7  2610.3   33.27 2696.54   29.12
 2821.11   30.52 2974.43   27.85  3204.4   32.34 3396.05   30.43 3808.37   34.62
#Mann= 6 ,-1 , 0
       0     .08       0   57.89     .06       0  126.06      .1       0
 1574.75     .04       0    1697      .1       0 1763.28     .07       0
#XS Ineff= 2 , 0
          986.39   36.57
Permanent Ineff=
       F       F
Bank Sta=1574.75,1705.54
XS Rating Curve= 0 ,0
Exp/Cntr=0.3,0.1

Type RM Length L Ch R = 1 ,18570   ,192,149.77,107.6
BEGIN DESCRIPTION:
No underwater information available.  copied  bigelk section 1 with -1.16 ft adjustment
END DESCRIPTION:
XS GIS Cut Line= 4
1644998.05506095713836.2705070081643982.06674325712721.773661718
1643982.06674325712598.714632094 1642593.2653545 711243.79692401
#Sta/Elev= 30
       0   44.94   85.25   40.25  113.67    34.9  151.55   32.05  198.91   32.42
  227.33   28.58  293.64   27.17  369.41   27.18  397.83    30.2  435.72   29.37
   577.8   37.73  681.99   39.23  947.21   35.14 1041.93   23.14 1136.65    17.6
 1401.87   21.59 1508.09   20.99    1517   13.11    1593   11.19 1599.09   17.76
 1606.09   20.91 1620.09   27.37 1650.71   29.19 2393.95   26.56 2540.64   28.89
 2648.21   27.22 2706.89   29.81 2814.47   27.08 3127.41   27.15  3571.4   30.43
#Mann= 5 ,-1 , 0
       0      .1       0   76.78     .06       0  165.05      .1       0
 1508.09     .04       0 1599.09     .07       0
#XS Ineff= 1 ,-1
  197.48  1322.731.74398
Permanent Ineff=
       F
Bank Sta=1508.09,1606.09
XS Rating Curve= 0 ,0
Exp/Cntr=0.3,0.1

Type RM Length L Ch R = 1 ,18420   ,120.97,110.73,115.73
BEGIN DESCRIPTION:
No underwater information available.  copied  bigelk section 1 with -2.03 ft adjustment
END DESCRIPTION:
XS GIS Cut Line= 4
1644878.31415592713647.6793635041644629.14120123713352.347144067
1644057.53675017712540.944220603 1642854.5784647710652.144598991
#Sta/Elev= 30
       0   37.21   82.43   26.08   155.7   24.93  192.33   17.72  247.28   19.44
   375.5   17.42  737.47   18.86  942.97    21.4 1011.47    19.6 1131.35    22.3
 1148.47   21.26 1182.72   23.85 1199.85   19.87    1219   12.03    1283   10.32
 1299.08   19.91 1311.16   26.64 1319.72   28.91 1362.53   29.52 1561.51   27.29
 2059.46   28.49 2250.34   26.36 2283.54   28.21 2449.52   26.21 3146.64   24.17
 3204.73   27.38 3329.22   26.94 3412.21   30.44  3520.1   31.57 3618.26   30.03
#Mann= 3 ,-1 , 0
       0      .1       0 1199.85     .04       0 1311.16     .07       0
#XS Ineff= 1 ,-1
  -51.56  1127.937.21204
Permanent Ineff=
       F
Bank Sta=1199.85,1299.08
XS Rating Curve= 0 ,0
Exp/Cntr=0.3,0.1

Type RM Length L Ch R = 1 ,18309   ,212.6,300.65,287.94
BEGIN DESCRIPTION:
No underwater information available.  copied  bigelk section 1 with -2.68 ft adjustment
END DESCRIPTION:
XS GIS Cut Line= 4
1644898.13461441713608.0384464561644759.85112792713400.676751971
1644164.73269758712498.8590622991642997.54625142710673.302627832
#Sta/Elev= 30
       0   39.29   25.24   30.57   42.07    27.7   75.72   25.15  151.45   24.04
   185.1   18.52  227.17   16.66   274.4      19  391.82   17.31 1155.02   20.59
  1163.4   18.58    1179   11.04    1213    9.67    1237    9.86    1243    11.5
 1247.27   19.77 1264.04   24.31 1280.82   26.44 1314.6826.90879 1429.42   26.08
 1537.43   27.27 1570.67    29.3 1653.75   27.66 1828.23   30.37 2185.49   27.68
 2384.89   29.54 2949.86   28.14 3215.73   24.55 3332.05   28.86  3496.5   31.83
#Mann= 4 ,-1 , 0
       0      .1       0 1155.02     .04       0 1264.04      .1       0
 1314.68     .07       0
#XS Ineff= 1 ,-1
 -314.72  885.7133.42696
Permanent Ineff=
       F
Bank Sta=1155.02,1247.27
XS Rating Curve= 0 ,0
Exp/Cntr=0.3,0.1

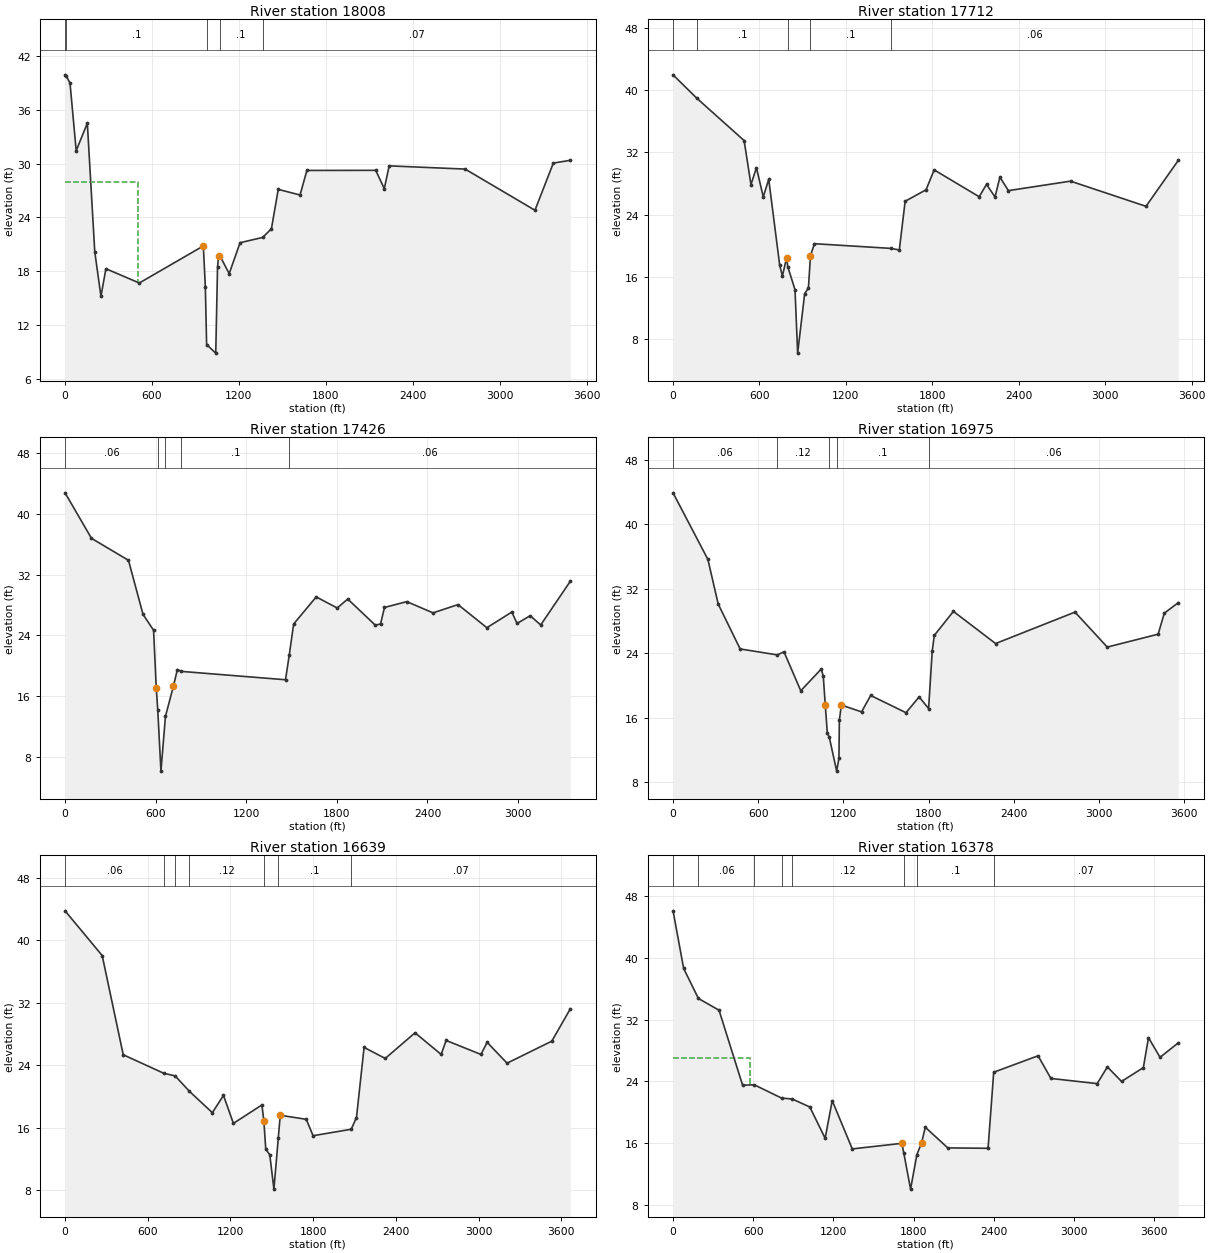
Type RM Length L Ch R = 1 ,18008   ,309.92,296.51,216.73
BEGIN DESCRIPTION:
No underwater information available.  copied  bigelk section 1 with -4.44 ft adjustment
END DESCRIPTION:
XS GIS Cut Line= 5
1645043.74845234713448.1933233591644512.91311617712689.098792687
1644507.60476282712529.8481918571644065.97889076712133.388602152
1643052.64009906710636.573396072
#Sta/Elev= 30
       0    39.9    7.32   39.79   34.17   38.99   76.88   31.44  153.75   34.51
     205   20.19  247.71    15.2  281.88   18.28  512.51   16.69  954.31   20.82
  968.31   16.21     977    9.83    10408.870001 1052.36   18.47 1059.36   19.68
 1066.37    19.8 1132.66   17.73 1207.92   21.18 1363.64   21.77 1424.28   22.74
 1471.31   27.13 1621.82    26.5 1668.85   29.24 2144.03   29.25 2203.21   27.21
 2237.02   29.75 2761.13   29.39 3242.97    24.8 3369.77   30.06 3486.69   30.37
#Mann= 5 ,-1 , 0
       0     .06       0    7.32      .1       0     977     .04       0
 1066.37      .1       0 1363.64     .07       0
#XS Ineff= 2 , 0
       0  500.22      28               0
Permanent Ineff=
       F       F
Bank Sta=954.31,1059.36
XS Rating Curve= 0 ,0
Exp/Cntr=0.3,0.1

Type RM Length L Ch R = 1 ,17712   ,328.16,286.23,143.09
BEGIN DESCRIPTION:
underwater portion from baltimore district hecras model xsec  3.39
END DESCRIPTION:
XS GIS Cut Line= 5
1645351.09844786713210.9333044741644808.42468841712618.094937235
1644771.17712668 712444.660977871644087.18012761 712050.64881967
1643113.85548536 710612.08724153
#Sta/Elev= 30
       0   41.98   166.6   38.94  493.47   33.52  540.92   27.85  578.88   30.02
  626.33   26.27  664.29   28.54  740.21    17.5  759.19   16.09  787.66    18.4
  797.15   17.26  846.67   14.33     865    6.17  913.67   13.82  939.74   14.55
  954.06   18.69   981.1   20.25 1509.92   19.65 1570.82   19.45 1611.21   25.71
 1756.62   27.19 1812.73   29.75 2125.44   26.29 2176.15   27.89 2235.31   26.26
 2269.12   28.81 2328.28   27.08 2759.31    28.3 3283.32   25.06 3507.36   30.97
#Mann= 5 ,-1 , 0
       0     .06       0   166.6      .1       0  797.15     .04       0
  954.06      .1       0 1509.92     .06       0
Bank Sta=787.66,954.06
XS Rating Curve= 0 ,0
Exp/Cntr=0.3,0.1

Type RM Length L Ch R = 1 ,17426   ,345.63,450.43,210.36
BEGIN DESCRIPTION:
underwater portion from baltimore district hecras model xsec 3.33
END DESCRIPTION:
XS GIS Cut Line= 4
1645553.62827605712813.3158463241644951.74277651712361.901721701
 1644178.1617045712009.6460549531643144.46317853710605.965702891
#Sta/Elev= 30
       0   42.75     175   36.77     420   33.88  516.25   26.78  586.25   24.68
  603.75   17.14  613.92   14.22     635    6.17  664.77   13.36   717.5   17.33
  743.75   19.52  769.49   19.28 1459.98   18.18 1485.11   21.48 1513.82   25.51
 1663.21   29.07 1802.31   27.61 1871.85   28.79 2054.41   25.36 2089.18   25.51
 2115.26   27.68 2263.05   28.45 2436.92   26.97 2602.09   28.06 2793.35   25.02
 2958.52   27.08 2993.29   25.58 3080.23    26.6 3149.77   25.38  3345.6   31.12
#Mann= 5 ,-1 , 0
       0     .06       0  613.92     .04       0  664.77     .08       0
  769.49      .1       0 1485.11     .06       0
Bank Sta=603.75,717.5
XS Rating Curve= 0 ,0
Exp/Cntr=0.3,0.1

Type RM Length L Ch R = 1 ,16975   ,172.54,335.89,295.28
BEGIN DESCRIPTION:
underwater portion from baltimore district hecras model xsec 3.25 with 1.5 vertical adjustment
END DESCRIPTION:
XS GIS Cut Line= 5
1645674.00537592712783.2215713411645026.97846392712000.770421967
1644823.84210788 712030.864696951644168.19993922711914.017577797
1643168.94933301710575.358009741
#Sta/Elev= 30
       0    43.9  245.25   35.64  317.92    30.1  472.33   24.53  733.84   23.79
  781.16   24.17  899.25   19.34 1043.63   22.04 1057.78   21.14 1071.93   17.52
 1086.08   14.11 1100.22   13.56    1152    9.37    1168   10.97    1171    15.7
 1185.15   17.57 1327.33   16.72 1391.32   18.76 1640.18   16.62 1732.62   18.58
  1799.2   17.14 1825.05    24.3 1839.27   26.21    1974   29.19    2271    25.2
 2830.04    29.1 3057.16   24.76  3415.3   26.36 3458.97   28.97 3557.13   30.27
#Mann= 5 ,-1 , 0
       0     .06       0  733.84     .12       0 1100.22     .04       0
 1154.29      .1       0  1799.2     .06       0
Bank Sta=1071.93,1185.15
XS Rating Curve= 0 ,0
Exp/Cntr=0.3,0.1

Type RM Length L Ch R = 1 ,16639   ,341.36,261.15,273.34
BEGIN DESCRIPTION:
underwater portion from baltimore district hecras model xsec 3.20
END DESCRIPTION:
XS GIS Cut Line= 4
1645777.59076789712774.8564696461644914.12493283711699.827672228
1644123.97507654711693.5064733621643181.19241029710532.507239357
#Sta/Elev= 30
       0   43.77  269.35   38.05  421.98   25.36  714.97      23  798.89   22.65
  902.23   20.68 1068.43   17.95 1149.23   20.16 1221.06   16.58 1427.86   18.94
 1441.86   16.94 1455.86   13.28    1485   12.57    1515    8.17 1546.87   14.74
 1560.87   17.62 1749.87    17.1 1798.88      15 2075.65   15.83 2113.89   17.33
 2169.04    26.3 2322.33   24.89 2538.75   28.17 2728.11    25.4 2764.18   27.19
 3016.67    25.4 3061.76   26.95 3206.03   24.28 3530.66    27.1 3664.63   31.22
#Mann= 7 ,-1 , 0
       0     .06       0  714.97      .1       0  798.89     .08       0
  902.23     .12       0 1441.86     .04       0 1546.87      .1       0
 2075.65     .07       0
Bank Sta=1441.86,1560.87
XS Rating Curve= 0 ,0
Exp/Cntr=0.3,0.1

Type RM Length L Ch R = 1 ,16378   ,155.97,736.7,787.15
BEGIN DESCRIPTION:
underwater portion from baltimore district hecras model xsec 3.14
END DESCRIPTION:
XS GIS Cut Line= 4
1645974.94812569712715.5094526561645004.40775771711451.549903661
1644069.30406615711394.8769526931643211.80010344710483.534930304
#Sta/Elev= 30
       0   46.05   79.43    38.6  189.8434.71742   344.2    33.2  520.71    23.5
  607.73   23.56   812.7 21.8383  891.74 21.7247 1023.77   20.69  1138.5   16.64
 1191.45   21.51 1341.49   15.27 1712.81   15.99 1726.84   14.77    1778   10.07
 1825.02   14.52 1860.08   16.04 1888.13   18.07 2056.44    15.4    2358   15.35
 2400.29   25.18 2732.26   27.31 2828.38   24.38 3174.39   23.71 3251.29   25.87
 3357.01   23.99 3520.41   25.78 3558.86   29.65 3645.36   27.11 3781.76   28.98
#Mann= 8 ,-1 , 0
       0      .1       0  189.84     .06       0  607.73      .1       0
   812.7     .06       0  891.74     .12       0 1726.84     .04       0
 1825.02      .1       0 2400.29     .07       0
#XS Ineff= 1 ,-1
  -71.17  578.8326.99267
Permanent Ineff=
       F
Bank Sta=1712.81,1860.08
XS Rating Curve= 0 ,0
Exp/Cntr=0.3,0.1

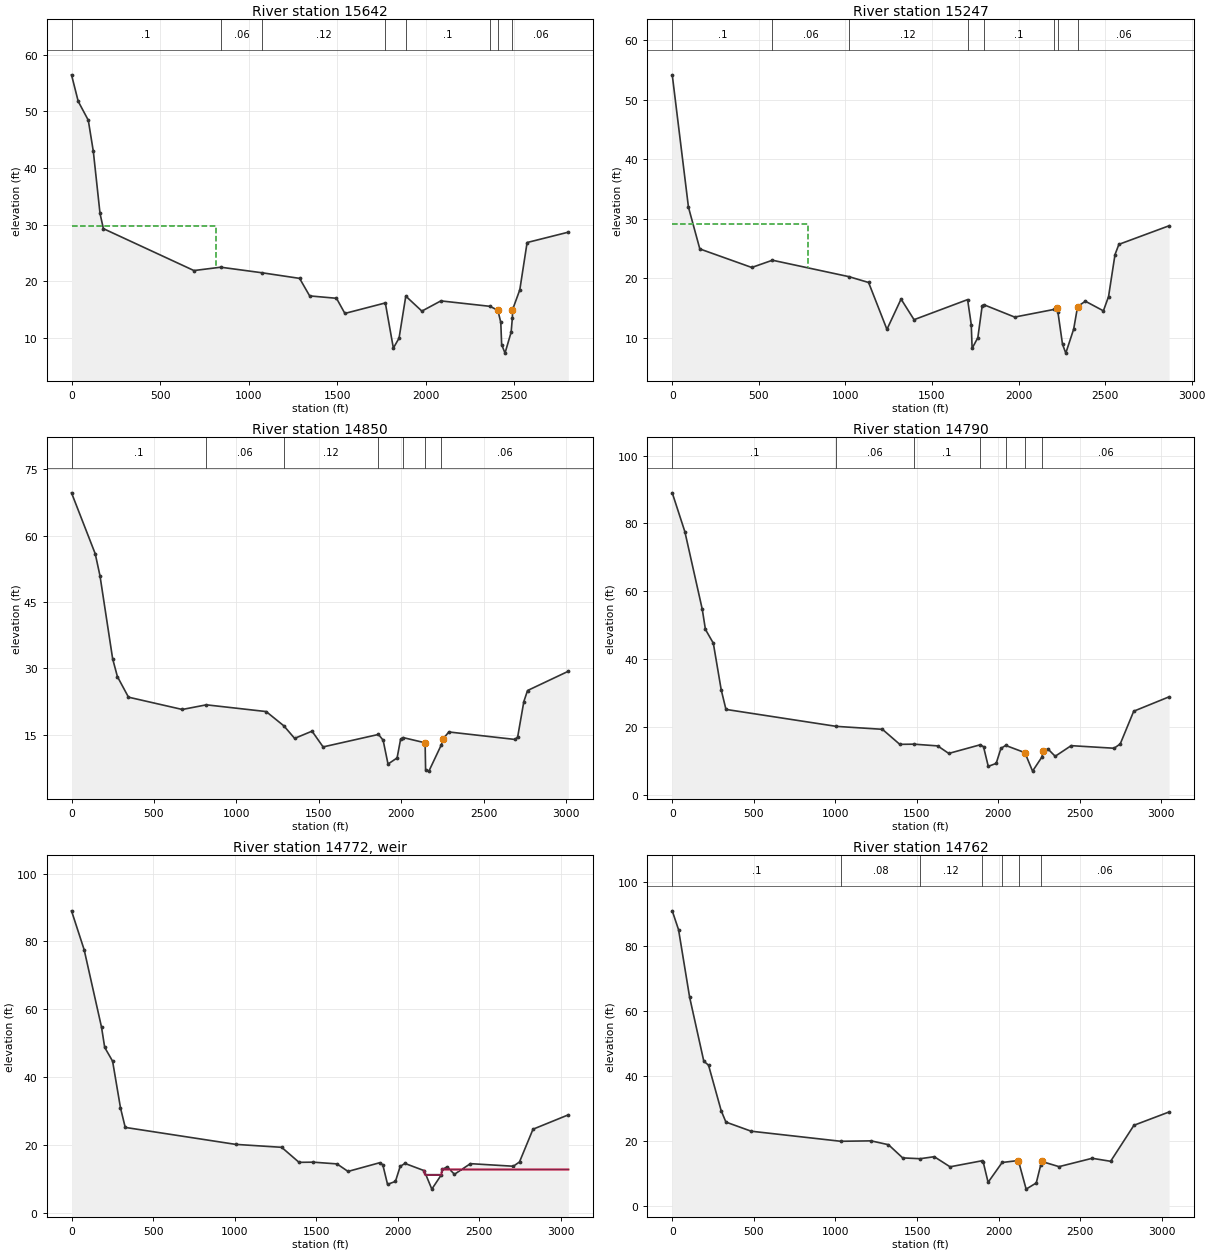
Type RM Length L Ch R = 1 ,15642   ,422.7,394.64,387.14
BEGIN DESCRIPTION:
underwater portion from baltimore district hecras model xsec 3.03
END DESCRIPTION:
XS GIS Cut Line= 3
 1646412.7237086712616.5277991441645139.47028051711455.954810694
1644565.42127299710537.331972241
#Sta/Elev= 30
       0   56.43   37.89   51.75   94.72   48.43  123.13   42.95  161.02   31.98
  179.96   29.31  691.43   21.92  842.66   22.51 1075.56   21.53 1288.13   20.54
 1344.96   17.45 1496.51   17.03 1543.87   14.36 1772.34   16.21 1817.65    8.25
 1849.84      10  1887.9   17.41  1978.7   14.77 2086.01   16.57 2363.82   15.61
 2407.93    14.9 2424.44   12.77 2429.19    8.88 2448.26    7.36 2482.83   11.05
 2489.98   13.64 2490.47   14.98 2531.75   18.52 2573.02   26.86 2806.05   28.69
#Mann= 8 ,-1 , 0
       0      .1       0  842.66     .06       0 1075.56     .12       0
 1772.34     .04       0  1887.9      .1       0 2363.82     .07       0
 2407.93     .04       0 2489.98     .06       0
#XS Ineff= 1 ,-1
       0  815.8229.72984
Permanent Ineff=
       F
Bank Sta=2407.93,2490.47
XS Rating Curve= 0 ,0
Exp/Cntr=0.3,0.1

Type RM Length L Ch R = 1 ,15247   ,255.1,397.15,157.89
BEGIN DESCRIPTION:
underwater portion from baltimore district hecras model xsec 2.96
END DESCRIPTION:
XS GIS Cut Line= 4
1646516.64507525712467.2316841041645109.73772015710887.282247856
1645109.73772015710661.575185552  1644613.182183710481.009535685
#Sta/Elev= 30
       0   54.22   93.73   31.93  159.34   24.91  459.28   21.79  578.81   23.01
 1021.02   20.24 1134.14   19.26    1240   11.37  1321.6   16.47 1396.59      13
  1705.9   16.38    1727   12.17    1732    8.17    1765    9.97 1790.25   15.36
 1799.63   15.52 1977.71   13.44 2207.61   14.74 2220.56   14.93 2227.56   14.27
    2254    8.87    2273    7.37 2318.56   11.42 2341.27   15.21 2385.96   16.11
 2490.24   14.49 2520.04    16.9 2557.28   23.96 2579.62   25.68 2869.64   28.81
#Mann= 8 ,-1 , 0
       0      .1       0  578.81     .06       0 1021.02     .12       0
  1705.9     .04       0 1799.63      .1       0 2207.61     .07       0
 2227.56     .04       0 2341.27     .06       0
#XS Ineff= 1 ,-1
       0  784.2329.08586
Permanent Ineff=
       F
Bank Sta=2220.56,2341.27
XS Rating Curve= 0 ,0
Exp/Cntr=0.3,0.1

Type RM Length L Ch R = 1 ,14850   ,122.91,59.38,141.04
BEGIN DESCRIPTION:
underwater portion from baltimore district hecras model xsec 2.89
END DESCRIPTION:
XS GIS Cut Line= 4
1646826.63489024712456.1956157831645533.15671414711077.735456109
1645489.89864616710748.9741392581644746.41879408710475.630590171
#Sta/Elev= 30
       0   69.65  143.99   55.87  172.79    50.9  249.58   32.15  278.38   28.13
  345.57   23.48  671.94    20.7  818.01   21.75  1180.7   20.23 1288.19      17
 1353.49   14.17 1459.08    15.8 1526.27   12.24 1862.25   15.06  1890.3   13.76
    1920    8.37 1975.03    9.75 1996.21   13.95 2010.33   14.36    2145   13.17
    2148    7.07    2168    6.77 2244.27   12.78 2251.73   13.95 2289.02   15.62
 2691.75   13.92 2706.67   14.54 2743.96   22.49 2766.33   24.98 3014.02   29.34
#Mann= 7 ,-1 , 0
       0      .1       0  818.01     .06       0 1288.19     .12       0
 1862.25     .04       0 2010.33      .1       0    2145     .04       0
 2244.27     .06       0
Bank Sta=2145,2251.73
XS Rating Curve= 0 ,0
Exp/Cntr=0.5,0.3

Type RM Length L Ch R = 1 ,14790   ,45.9,27.91,49.33
BEGIN DESCRIPTION:
underwater portion not changed because baltimore district hecras model xsec 2.88 is higher in elevation.  underwater portion of left  and right channels were cut in.
END DESCRIPTION:
XS GIS Cut Line= 4
1647020.24101596712417.4876102811645568.12896246710900.981872663
1645547.19737521710728.2962781341644827.44138722710444.029565215
#Sta/Elev= 30
       0   89.04   77.53   77.57  184.14   54.71  203.52   48.77  251.98    44.7
  300.44   30.93  329.51   25.17 1006.26   20.17 1288.98    19.3 1395.59   14.87
 1483.19   14.92 1628.19   14.41 1696.03   12.19 1889.87   14.75 1909.25   14.17
 1938.32    8.38 1986.78    9.24 2015.86   13.66 2044.93   14.55 2163.09   12.42
    2210    6.97    2268   11.17 2273.58   12.77 2303.68   13.54 2348.84   11.35
 2446.68   14.48 2710.09   13.72 2747.72   14.99 2830.51   24.64 3047.43   28.88
#Mann= 7 ,-1 , 0
       0      .1       0 1006.26     .06       0 1483.19      .1       0
 1889.87     .04       0 2044.93      .1       0 2163.09     .04       0
    2268     .06       0
Bank Sta=2163.09,2273.58
XS Rating Curve= 0 ,0
Exp/Cntr=0.5,0.3

Type RM Length L Ch R = 5 ,14772   ,,,
BEGIN DESCRIPTION:
Farrs Creek Dam - 100' wide at elevation 11.17 as per Baltimore District HEC-RAS model.
END DESCRIPTION:
IW Pilot Flow=0
#Inline Weir SE= 5
    2163   12.42    2168   11.17    2268   11.17    2273   12.77 3047.43   12.77
IW Dist,WD,Coef,Skew,MaxSub,Min_El,Is_Ogee,SpillHt,DesHd
17,3,3,0,0.95,, 0 ,,,0,0,

Type RM Length L Ch R = 1 ,14762   ,39.67,37.76,47.99
BEGIN DESCRIPTION:
underwater portion from baltimore district hecras model xsec 2.87
END DESCRIPTION:
XS GIS Cut Line= 4
1647046.12564881 712394.83739695 1645595.1156158710872.393023849
1645572.79238454710720.5950511541644840.56707227710431.562604129
#Sta/Elev= 30
       0   90.98   38.68   85.16  106.37   64.35   193.4   44.56  222.41   43.33
  299.77    29.3  328.78   25.77   483.5   22.95 1032.45   19.84 1218.43   19.97
  1324.8   18.78 1411.83   14.71 1518.55   14.46 1605.23   15.08 1701.93   11.96
 1895.33    13.8    1905   13.46    1935    7.17 2021.04   13.29 2117.31   13.88
 2124.38   13.17    2168    5.07    2230    6.97 2256.59   12.37 2264.11    13.6
 2369.47   12.01 2572.66   14.59 2685.55   13.66 2828.53   24.78 3043.79   28.89
#Mann= 7 ,-1 , 0
       0      .1       0 1032.45     .08       0 1518.55     .12       0
 1895.33     .04       0 2021.04      .1       0 2124.38     .04       0
 2256.59     .06       0
Bank Sta=2117.31,2264.11
XS Rating Curve= 0 ,0
Exp/Cntr=0.5,0.3

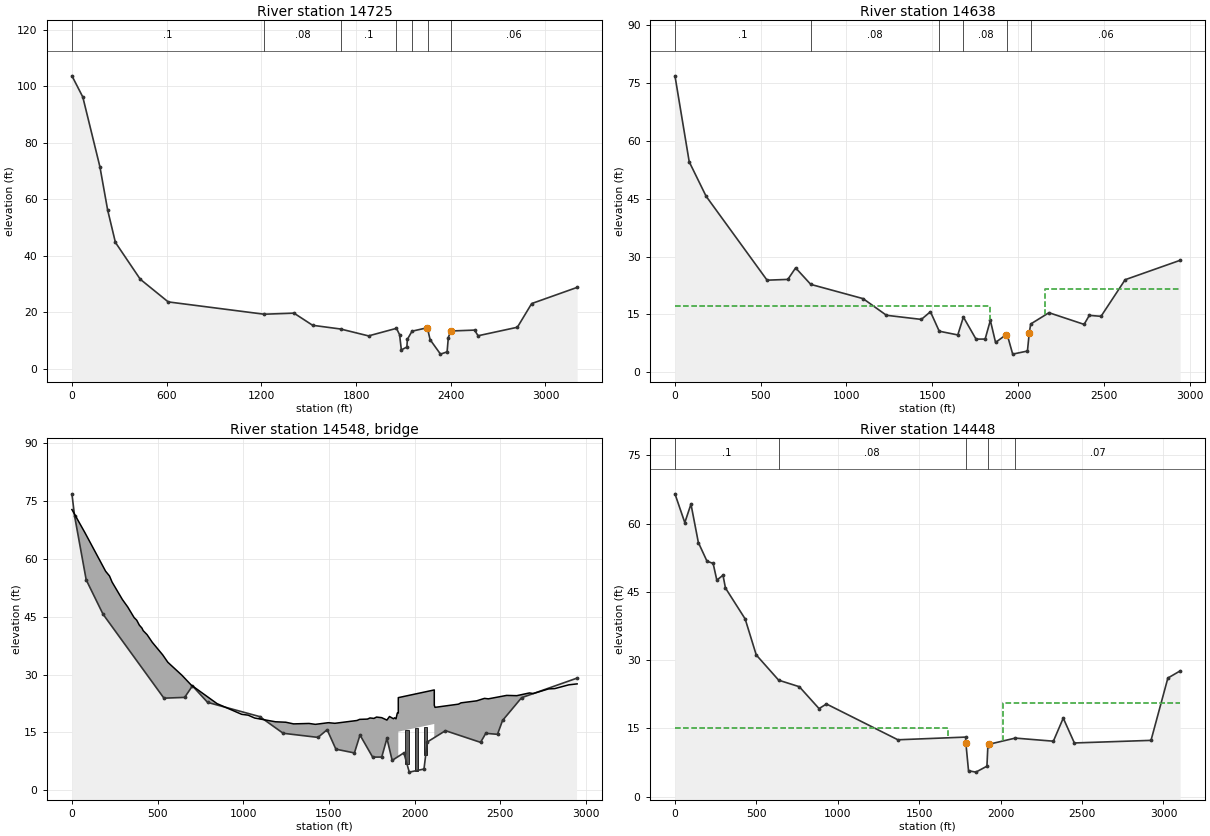
Type RM Length L Ch R = 1 ,14725   ,277.8,86.56,63.02
Node Photo=RIMG0036.JPG
BEGIN DESCRIPTION:
underwater portion from baltimore district hecras model xsec 2.86
END DESCRIPTION:
XS GIS Cut Line= 4
1647215.51351129712432.2580048441645626.02909914710862.214233056
1645611.94618677710719.9026978161644847.73984438710412.801169544
#Sta/Elev= 30
       0  103.64   68.87   96.15   177.1   71.51   226.3   56.16   275.5    44.7
  432.92   31.67  610.03   23.65 1217.58   19.29    1407   19.67 1525.07   15.37
 1701.86   14.06 1879.28   11.62 2056.38    14.3 2076.06   12.03    2087    6.67
    2122    7.67 2125.25    10.4 2154.77   13.28 2248.23   14.47 2255.27   13.66
 2269.33   10.29    2335    5.17    2377    5.97 2384.71   11.03  2399.8   13.35
 2550.69   13.67 2573.32   11.67 2822.28   14.68 2912.81   23.06 3200.79   28.78
#Mann= 7 ,-1 , 0
       0      .1       0 1217.58     .08       0 1701.86      .1       0
 2056.38     .04       0 2154.77      .1       0 2255.27     .04       0
  2399.8     .06       0
Bank Sta=2248.23,2399.8
XS Rating Curve= 0 ,0
Exp/Cntr=0.5,0.3

Type RM Length L Ch R = 1 ,14638   ,142.76,190.2,186.1
BEGIN DESCRIPTION:
underwater portion from baltimore district hecras model xsec 2.84
END DESCRIPTION:
XS GIS Cut Line= 4
1647545.05116709711496.5247254821646236.88854101710960.800983384
1645229.52682024710537.9577919391644814.13236812710395.359696448
#Sta/Elev= 30
       0   76.89   83.21   54.57  181.54   45.65  537.06   23.86  658.09   24.06
  703.48   27.05   791.7   22.77 1096.82   19.07 1232.97   14.75 1436.38   13.68
 1489.53   15.67 1540.68   10.62 1648.95    9.65 1681.47   14.29 1755.23    8.56
 1808.38    8.58 1838.74   13.43 1869.11     7.7 1929.84    9.69 1937.43    9.67
    1969    4.67    2055    5.47 2065.66   10.24 2074.08   12.49 2180.37   15.42
 2385.34   12.39  2415.7   14.73 2484.03   14.48 2624.52   23.98 2945.29   29.02
#Mann= 6 ,-1 , 0
       0      .1       0   791.7     .08       0 1540.68      .1       0
 1681.47     .08       0 1937.43     .04       0 2074.08     .06       0
#XS Ineff= 2 ,-1
    2155 2945.29   21.48       0    1835   17.23
Permanent Ineff=
       F       F
Bank Sta=1929.84,2065.66
XS Rating Curve= 0 ,0
Exp/Cntr=0.5,0.3

Type RM Length L Ch R = 3 ,14548   ,,,
BEGIN DESCRIPTION:
Main Street. Farrs Creek Bridge.  CE050907PF-6     Geometry taken from Baltimore District's HEC-RAS model.
Top of road from LIDAR.  Two streams converge at this bridge.
END DESCRIPTION:
Bridge Culvert--1,0,-1,-1, 0
Deck Dist Width WeirC Skew NumUp NumDn MinLoCord MaxHiCord MaxSubmerge Is_Ogee
70,40,2.6,0, 60, 60, , , 0.95, 0, 0,0,,
       0   75.64  196.67  219.36  234.49  295.01  325.26  363.08  378.21  393.34
  408.47  416.03  438.73  468.98   529.5  559.75  642.96  695.91   847.2  990.92
 1028.74 1066.56 1187.59  1248.1 1293.49 1384.26 1420.94 1496.86 1534.81 1663.87
 1679.06 1724.61 1739.79 1762.56 1777.75 1808.11 1838.48 1853.66 1876.44 1884.03
 1891.62 1899.21  1904.9    1905    2115  2115.1 2119.37 2256.02  2271.2  2362.3
 2407.85 2430.62 2537.19  2596.4 2670.41 2692.61 2781.42 2818.43 2899.84 2948.78
   72.81   66.83    56.8   55.57   53.98   49.43   47.56   44.77    44.1   42.82
   42.06   41.38   40.34   38.36   35.12   33.18   29.77   27.28   22.44   19.67
   19.45   18.71   17.74   17.62   17.19    17.3   17.07    17.5   17.34   18.07
   18.36   18.43   18.73   18.61   18.96    18.8   18.18   19.11   18.53   18.77
    18.5      20      20      24      26      22   21.48   22.31   22.65   23.17
   23.81   23.69   24.58   24.51   25.22   25.06   26.26   26.35   27.32   27.57
                                                                                
                                                                                
                                                                                
                                                                                
                       0   15.17   17.17       0
                                                                                
    -150  -74.36   46.67   69.36   84.49  145.01  175.26  213.08  228.21  243.34
  258.47  266.03  288.73  318.98   379.5  409.75  492.96  545.91   697.2  840.92
  878.74  916.56 1037.59  1098.1 1143.49 1234.26 1270.94 1346.86 1384.81 1513.87
 1529.06 1574.61 1589.79 1612.56 1627.75 1658.11 1688.48 1703.66 1726.44 1734.03
 1741.62 1749.21  1754.9    1755    1965  1965.1 1969.37 2106.02  2121.2  2212.3
 2257.85 2280.62 2387.19  2446.4 2520.41 2542.61 2631.42 2668.43 2786.84    3103
   72.81   66.83    56.8   55.57   53.98   49.43   47.56   44.77    44.1   42.82
   42.06   41.38   40.34   38.36   35.12   33.18   29.77   27.28   22.44   19.67
   19.45   18.71   17.74   17.62   17.19    17.3   17.07    17.5   17.34   18.07
   18.36   18.43   18.73   18.61   18.96    18.8   18.18   19.11   18.53   18.77
    18.5      20      20      24      26      22   21.48   22.31   22.65   23.17
   23.81   23.69   24.58   24.51   25.22   25.06   26.26   26.35   27.58   27.57
                                                                                
                                                                                
                                                                                
                                                                                
                       0   15.17   17.17       0
                                                                                
Pier Skew, UpSta & Num, DnSta & Num=  ,1955, 4 ,1805, 4 , 3 , 3 , 0 ,,
    13.6    13.6    19.9    19.9
    4.17   12.67   12.67   15.67
    13.6    13.6    19.9    19.9
    4.17   12.17   12.17   15.37
Pier Skew, UpSta & Num, DnSta & Num=  ,2010, 4 ,1860, 4 , 3 , 3 , 0 ,,
    13.6    13.6    19.9    19.9
    4.17   13.07   13.07   16.17
    13.6    13.6    19.9    19.9
    4.17   12.67   12.67   15.67
Pier Skew, UpSta & Num, DnSta & Num=  ,2065, 4 ,1915, 4 , 3 , 3 , 0 ,,
    13.6    13.6    19.9    19.9
    4.17   13.47   13.47   16.47
    13.6    13.6    19.9    19.9
    4.17   12.97   12.97   16.17
BR Coef=-1 , 1 , 0 ,, 0 ,,,0.8,0,0.5,0,
WSPro=,,,, 1 ,,,, 0 ,,,, 0 ,,,,-1 ,-1 ,-1 , 0 , 0 , 0 , 0 , 0
BR U #Sta/Elev= 30
       0   76.89   15.13   71.24   83.21   54.57  181.54   45.65  537.06   23.86
  658.09   24.06  703.48   27.05   791.7   22.77 1096.82   19.07 1232.97   14.75
 1436.38   13.68 1489.53   15.67 1540.68   10.62 1648.95    9.65 1681.47   14.29
 1755.23    8.56 1808.38    8.58 1838.74   13.43 1869.11     7.7 1937.43    9.67
    1969    4.67    2055    5.47 2074.08   12.49 2180.37   15.42 2385.34   12.39
  2415.7   14.73 2484.03   14.48 2513.51   18.07 2624.52   23.98 2945.29   29.02
BR U #Mann= 6
       0      .1   791.7     .08 1540.68      .1 1681.47     .08 1937.43    .038
 2074.08     .06
BR D #Sta/Elev= 30
       0   66.54   60.51   60.21   83.21   64.17   98.34   64.28  143.72   55.84
  196.67   51.74  234.49   51.24  257.18   47.57  295.01   48.65  310.13   45.84
  431.16   39.04  499.24   31.13  636.99   25.58  763.99   24.14  885.02   19.33
   930.4   20.35 1369.13   12.48 1655.98   14.51 1785.04   13.07    1803    5.67
    1848    5.37    1916    6.67 1921.69   11.01    2090   12.85 2324.05   12.17
 2384.78   17.24  2453.1   11.78 2923.72   12.35  3027.3   26.05 3102.73   27.62
BR D #Mann= 5
       0      .1  636.99     .08 1785.04    .038 1921.69     .08    2090     .07
BC Design=,, 0 ,, 0 ,,,,,,
BC Use User HTab Curves=0
BC User HTab FreeFlow(D)= 0

Type RM Length L Ch R = 1 ,14448   ,86.98,75.29,96.4
BEGIN DESCRIPTION:
underwater portion from baltimore district hecras model xsec 2.83
END DESCRIPTION:
XS GIS Cut Line= 5
 1647593.5600946711378.0726931991646285.91443102710842.560659558
1645275.12792557710418.2799041871644877.71046436710281.853014544
1644716.56401598710218.125411987
#Sta/Elev= 30
       0   66.54   60.51   60.21   98.34   64.28  143.72   55.84  196.67   51.74
  234.49   51.24  257.18   47.57  295.01   48.65  310.13   45.84  431.16   39.04
  499.24   31.13  636.99   25.58  763.99   24.14  885.02   19.33   930.4   20.35
 1369.13   12.48 1785.04   13.07 1786.71   11.74    1803    5.67    1848    5.37
    1916    6.67 1921.69   11.01 1929.28    11.5    2090   12.85 2324.05   12.17
 2384.78   17.24  2453.1   11.78 2923.72   12.35  3027.3   26.05 3102.73   27.62
#Mann= 5 ,-1 , 0
       0      .1       0  636.99     .08       0 1785.04     .04       0
 1921.69     .08       0    2090     .07       0
#XS Ineff= 2 ,-1
       0    1679   15.17    2015 3102.7320.52476
Permanent Ineff=
       F       F
Bank Sta=1786.71,1929.28
XS Rating Curve= 0 ,0
Exp/Cntr=0.5,0.3