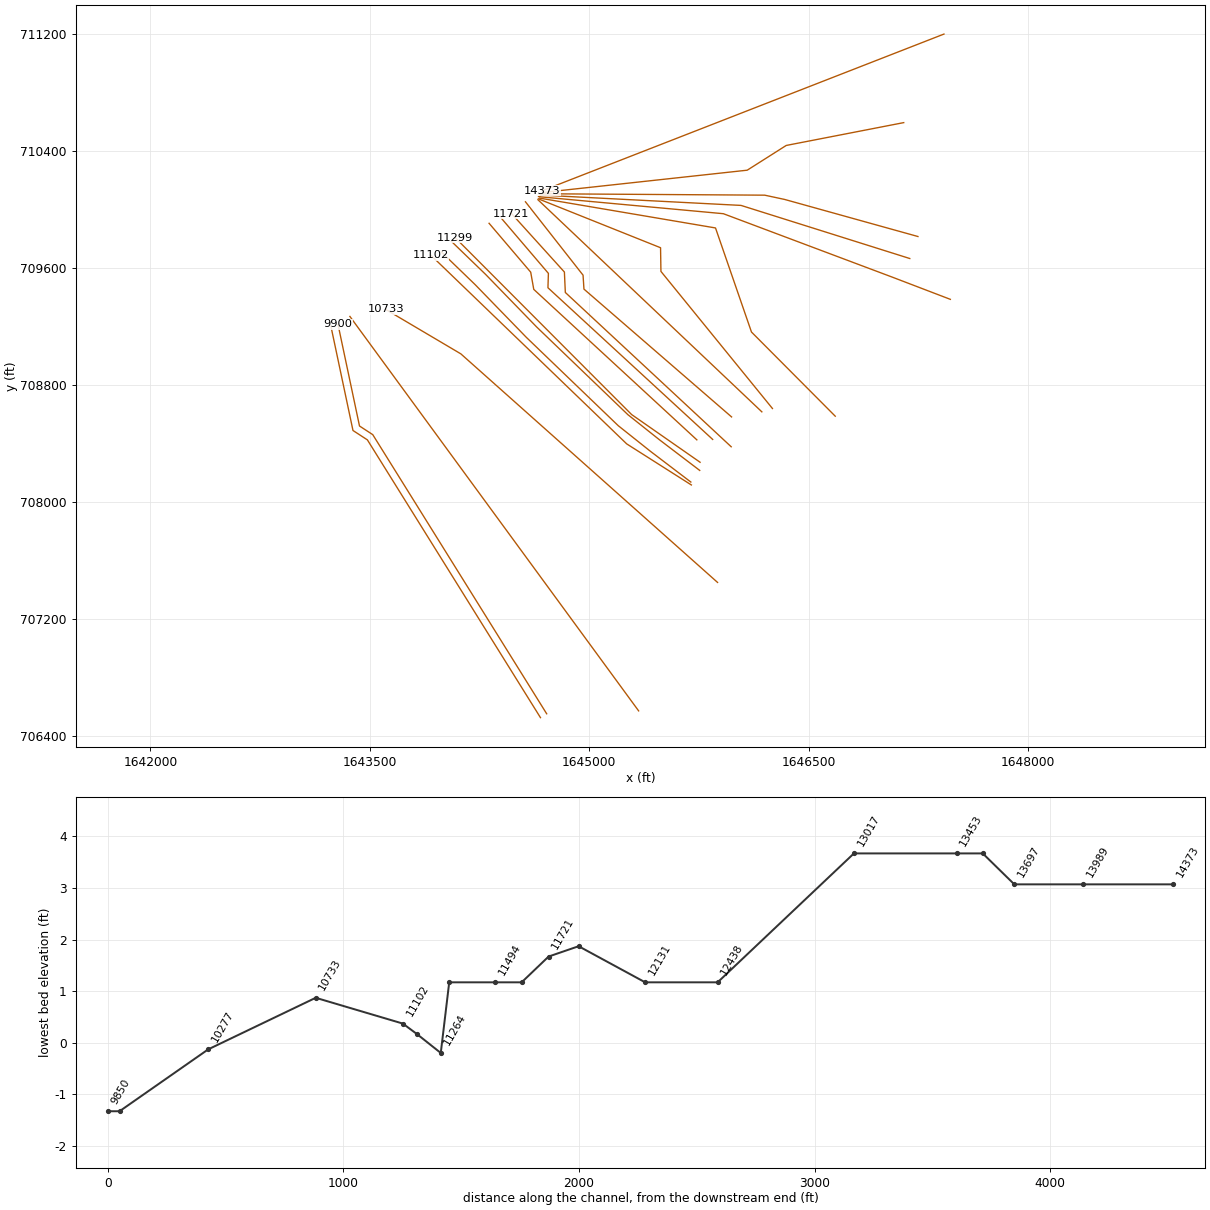
HEC-RAS study bigelkcreek.prj: Big Elk Creek

--- bigelkcreek.g23 (geometry) --- (continued)

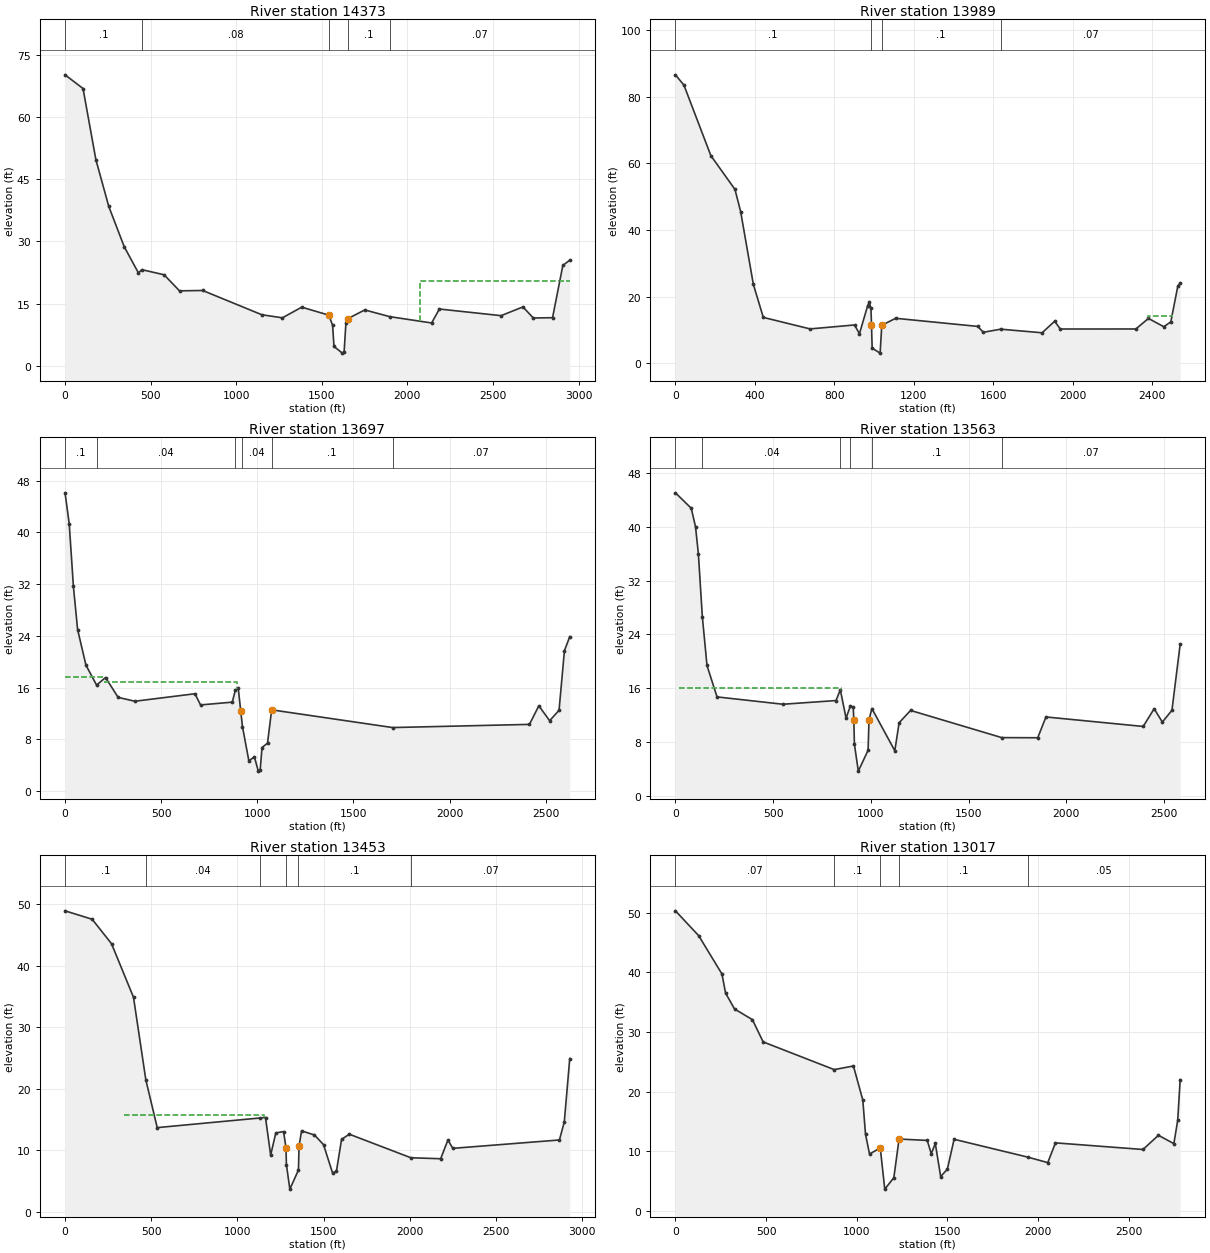
Type RM Length L Ch R = 1 ,14373   ,363.19,384.06,364.6
BEGIN DESCRIPTION:
underwater portion from baltimore district hecras model xsec 2.81
END DESCRIPTION:
XS GIS Cut Line= 2
1647424.54131304711198.1008510891644677.90868318710126.851843491
#Sta/Elev= 30
       0   70.15  105.19   66.85  180.33   49.68  255.46   38.43  345.62   28.73
  428.27   22.43   449.3   23.18  578.55   21.96  668.71   18.08  803.95   18.17
 1149.57   12.32 1269.79   11.58 1382.49   14.15 1540.28   12.23 1562.82    9.82
    1571    4.67    1620    3.07    1630    3.27 1640.65   10.28 1652.98   11.41
 1750.66   13.48 1896.84   11.86 2141.36   10.34 2186.45    13.7  2547.1    12.1
 2674.84   14.21 2734.95   11.54 2847.65   11.61 2907.76   24.21 2948.15   25.48
#Mann= 5 ,-1 , 0
       0      .1       0   449.3     .08       0 1540.28     .04       0
 1652.98      .1       0 1896.84     .07       0
#XS Ineff= 1 ,-1
 2076.26 2948.1320.45654
Permanent Ineff=
       F
Bank Sta=1540.28,1652.98
XS Rating Curve= 0 ,0
Exp/Cntr=0.3,0.1

Type RM Length L Ch R = 1 ,13989   ,408.41,291.21,159.45
BEGIN DESCRIPTION:
underwater portion from baltimore district hecras model xsec 2.74
END DESCRIPTION:
XS GIS Cut Line= 4
  1647149.452085710592.7239108231646346.24723007710436.635517955
 1646079.5962256710267.539759025 1644681.8013031710115.173983663
#Sta/Elev= 30
       0    86.5   42.79    83.4  178.27   62.26   299.5   52.16  328.02   45.52
   392.2   23.65  442.12   13.78  677.44   10.33  901.12   11.51  925.99     8.9
  967.43   17.31  975.72   18.33  984.01   16.45  986.53   11.65     990    4.57
    1030    3.07 1038.38   11.43 1108.34   13.51 1521.26   11.08 1549.43    9.32
 1636.82   10.25 1845.17    9.17 1908.54   12.64 1936.71    10.3 2316.95   10.31
 2380.32   13.47 2457.78   10.98 2492.99   12.46  2528.2   23.17 2540.06   24.02
#Mann= 4 ,-1 , 0
       0      .1       0  984.01     .04       0 1038.38      .1       0
 1636.82     .07       0
#XS Ineff= 1 ,-1
  2379.9 2503.2514.06806
Permanent Ineff=
       F
Bank Sta=986.53,1038.38
XS Rating Curve= 0 ,0
Exp/Cntr=0.3,0.1

Type RM Length L Ch R = 1 ,13697   ,138.05,134.04,68.57
BEGIN DESCRIPTION:
underwater portion from Baltimore Dist hecras model xsec 2.74
END DESCRIPTION:
XS GIS Cut Line= 4
1647246.59567387 709814.171792821646335.46109897710067.535417959
1646199.03453158710096.7696823781644659.36327124710106.514437199
#Sta/Elev= 30
       0   46.12    21.8   41.34   43.59   31.63   65.39   24.97  108.98   19.45
  164.06   16.38   210.7   17.55  276.09   14.48  363.28   13.88   675.7   15.04
  704.76   13.31  869.64   13.74   886.4   15.63  900.94   15.88  913.75   12.38
  922.73    9.97     956    4.67     985    5.27    1005    3.07    1015    3.27
 1024.46    6.72 1053.09     7.4 1074.57   12.55 1703.59    9.81 2415.26    10.3
 2464.26   13.18 2520.26   10.87 2569.27   12.48 2597.27   21.71 2624.94   23.88
#Mann= 6 ,-1 , 0
       0      .1       0  164.06     .04       0   886.4      .1       0
  922.73     .04       0 1074.57      .1       0 1703.59     .07       0
#XS Ineff= 2 ,-1
       0  203.44   17.64  203.44  895.61    16.8
Permanent Ineff=
       T       T
Bank Sta=913.75,1074.57
XS Rating Curve= 0 ,0
Exp/Cntr=0.3,0.1

Type RM Length L Ch R = 1 ,13563   ,117.44,110.37,85.32
BEGIN DESCRIPTION:
underwater portion from baltimore Distr hecras model sec 2.7
END DESCRIPTION:
XS GIS Cut Line= 3
1647190.83094077709663.7567755131646037.15253802710026.780912906
 1644665.0443577710097.539854944
#Sta/Elev= 30
       0   45.03   80.72   42.74  102.74   39.99  117.41   35.95  137.69    26.6
  161.44   19.37  212.81    14.7  550.38   13.61   821.9   14.16  843.91   15.76
  873.27   11.54  895.28   13.35  909.96   13.16  913.04   11.27     916    7.67
     936    3.67     986    6.77  990.68   11.28 1005.36   12.97 1122.77     6.7
 1144.79   10.86 1203.49   12.69 1670.15    8.65  1854.3    8.63 1896.36   11.72
 2394.01   10.31 2450.09   12.94 2492.14   10.96 2541.21   12.71 2583.37   22.54
#Mann= 6 ,-1 , 0
       0      .1       0  137.69     .04       0  843.91      .1       0
  895.28     .04       0 1005.36      .1       0 1670.15     .07       0
#XS Ineff= 1 ,-1
   16.12  845.11      16
Permanent Ineff=
       T
Bank Sta=913.04,990.68
XS Rating Curve= 0 ,0
Exp/Cntr=0.3,0.1

Type RM Length L Ch R = 1 ,13453   ,535.57,436.21,129
BEGIN DESCRIPTION:
underwater portion from baltimore district hecras model xsec 2.7
END DESCRIPTION:
XS GIS Cut Line= 5
1647468.24911612 709384.592705981647073.59958692709535.561376274
1645916.43664199709970.0878698381644674.77642724710084.513232768
1644652.96681456710087.825811386
#Sta/Elev= 30
       0   48.91  157.39   47.54  269.81   43.56  397.22   34.85   468.7   21.43
   534.7   13.67 1132.68   15.24 1162.79   15.31  1192.7     9.2 1222.61   12.81
 1267.47   13.02 1281.69   10.41    1284    7.67    1304    3.67    1354    6.77
  1357.2   10.64 1372.15   13.14 1446.92   12.47 1499.27    10.9 1551.61    6.31
 1574.04    6.55 1603.95   11.75 1648.81    12.6 2005.97    8.77 2178.79    8.61
 2220.97   11.66 2249.09    10.3 2867.69   11.66 2895.81   14.59 2927.57   24.89
#Mann= 6 ,-1 , 0
       0      .1       0   468.7     .04       0 1132.68      .1       0
    1284     .04       0    1354      .1       0 2005.97     .07       0
#XS Ineff= 1 ,-1
  344.62 1155.92   15.72
Permanent Ineff=
       T
Bank Sta=1281.69,1357.2
XS Rating Curve= 0 ,0
Exp/Cntr=0.3,0.1

Type RM Length L Ch R = 1 ,13017   ,399.55,578.4,433.23
BEGIN DESCRIPTION:
underwater portion from baltimore district hecras model xsec 2.61
END DESCRIPTION:
XS GIS Cut Line= 4
1646681.34463328708585.7929931581646108.69032046709161.121990487
1645862.84049052709872.6403217171644659.46898951710076.749628514
#Sta/Elev= 30
       0   50.29  128.39   46.12  256.79    39.7  276.54   36.52  325.92   33.85
  424.69   32.06  483.95   28.33   876.2   23.69  982.09    24.3 1033.93   18.58
 1048.74   12.87 1070.96    9.54 1130.21   10.58    1155    3.67    1205    5.57
  1233.9   12.06 1389.43   11.83 1411.64    9.59 1433.86   11.32 1463.49    5.77
 1500.52    7.02 1537.55   12.02 1945.68    9.02 2054.45    8.11 2097.05   11.42
 2579.85   10.31 2665.05   12.69 2750.25   11.29 2771.55    15.2 2785.12   22.01
#Mann= 5 ,-1 , 0
       0     .07       0   876.2      .1       0 1130.21    .035       0
  1233.9      .1       0 1945.68     .05       0
Bank Sta=1130.21,1233.9
XS Rating Curve= 0 ,0
Exp/Cntr=0.3,0.1

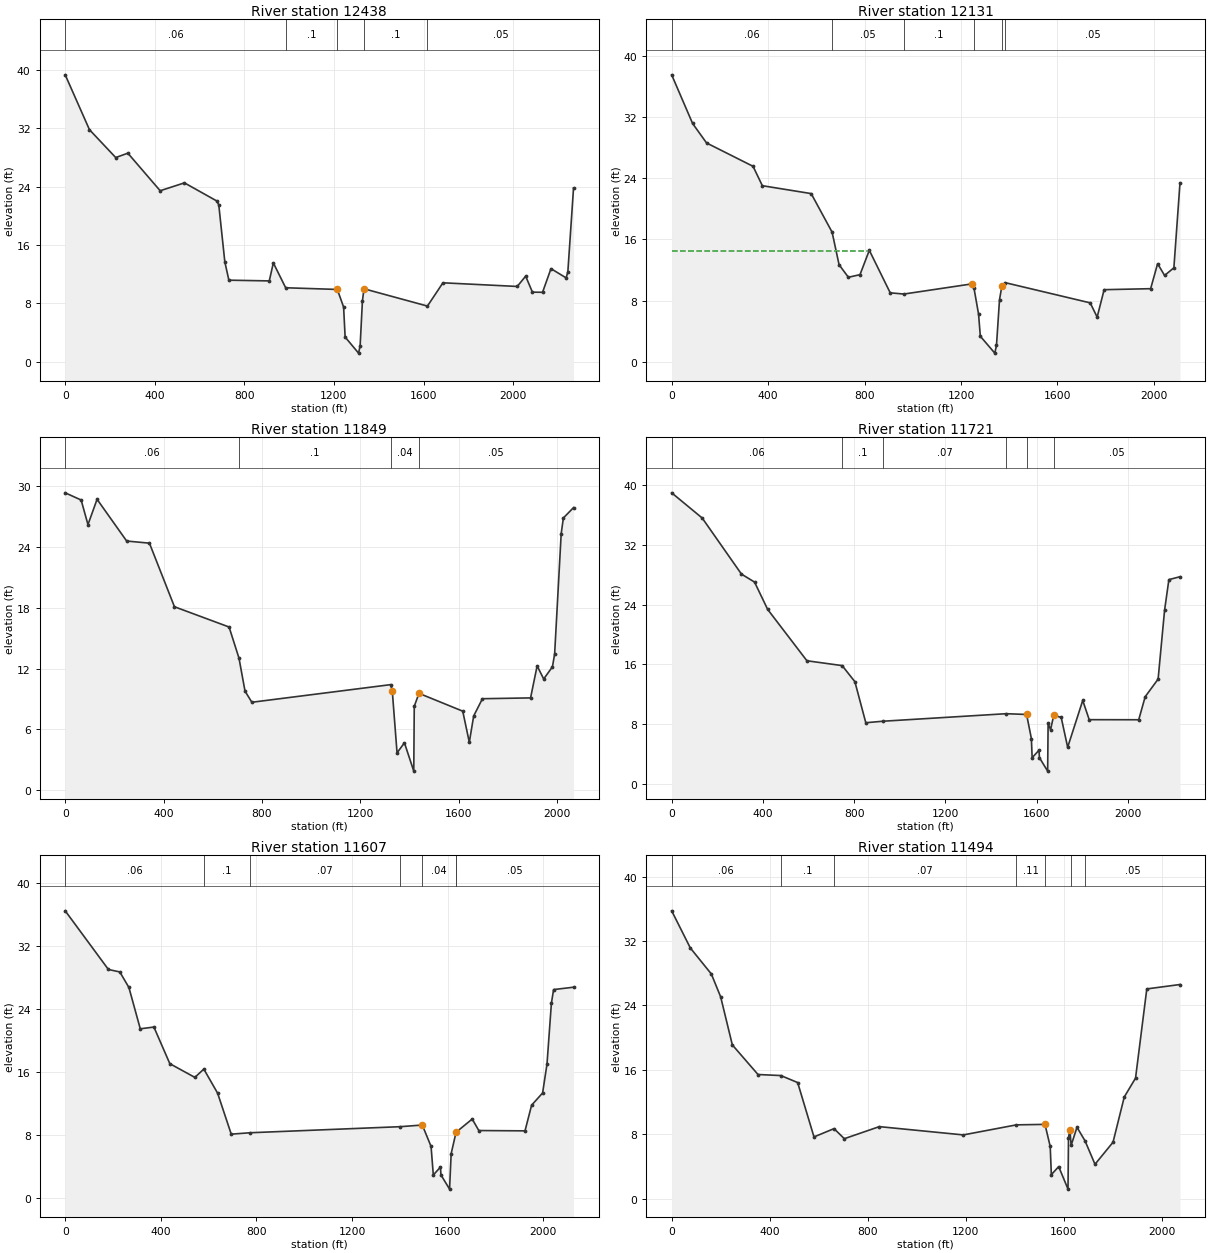
Type RM Length L Ch R = 1 ,12438   ,242.88,307.48,430.1
BEGIN DESCRIPTION:
underwater portion from baltimore district hecras model xsec 2.51
END DESCRIPTION:
XS GIS Cut Line= 4
1646252.11295325708638.2581270341645489.73517324709575.565055206
1645487.12429042709737.4397893251644651.64179178710071.632788777
#Sta/Elev= 30
       0   39.32  108.28    31.8  225.58   27.98  279.72   28.58  424.09   23.43
  532.36   24.51  676.74   22.03  685.76    21.5  712.83   13.67  730.87   11.17
  911.34   11.07  929.38   13.54  984.47   10.13 1215.21     9.9 1243.21    7.48
    1250    3.37    1310    1.17    1317    2.17 1327.22    8.33 1334.22    9.99
 1617.56    7.62 1686.75   10.81 2018.47   10.31 2056.17   11.72 2086.33    9.53
 2131.56    9.51 2169.26   12.75 2237.11   11.48 2244.65   12.35 2269.94   23.82
#Mann= 5 ,-1 , 0
       0     .06       0  984.47      .1       0 1215.21     .04       0
 1334.22      .1       0 1617.56     .05       0
#XS Ineff= 2 , 0
       0  929.97   13.49               0
Permanent Ineff=
       T       F
Bank Sta=1215.21,1334.22
XS Rating Curve= 0 ,0
Exp/Cntr=0.3,0.1

Type RM Length L Ch R = 1 ,12131   ,248.62,282.35,171.48
BEGIN DESCRIPTION:
underwater portion from baltimore district hecras model xsec 2.51
END DESCRIPTION:
XS GIS Cut Line= 2
1646179.54502192708615.5669509021644649.12649345710065.298202932
#Sta/Elev= 30
       0   37.49   86.78   31.14  144.63    28.6  337.47   25.55  376.04   23.02
  578.52   21.99   665.3   16.96  694.23   12.71   732.8   11.07  781.01   11.41
  819.58   14.59  906.35    9.04  962.96    8.88 1243.83    10.2 1253.47    9.69
 1272.75    6.25    1280    3.37    1340    1.17    1347    2.17 1359.53    8.14
 1369.18    9.88 1382.68   10.37 1735.57    7.73  1764.5    5.87 1793.43    9.45
 1986.27    9.58  2015.2   12.84 2044.12   11.31 2082.69    12.3 2108.06    23.4
#Mann= 6 ,-1 , 0
       0     .06       0   665.3     .05       0  962.96      .1       0
 1253.47     .04       0 1369.18      .1       0 1382.68     .05       0
#XS Ineff= 2 , 0
       0     822   14.45               0
Permanent Ineff=
       T       F
Bank Sta=1243.83,1369.18
XS Rating Curve= 0 ,0
Exp/Cntr=0.3,0.1

Type RM Length L Ch R = 1 ,11849   ,147.08,127.45,111.14
BEGIN DESCRIPTION:
underwater portion from baltimore district hecras model xsec 2.39 adj 0.7f t vertically
END DESCRIPTION:
XS GIS Cut Line= 4
 1645972.5465475708580.8373147991644963.46250454709454.556425154
1644957.30955307709549.9271731081644563.52065827710051.392718837
#Sta/Elev= 30
       0   29.35   64.82   28.64   92.59   26.21  129.63   28.71     250   24.59
   342.6   24.38  444.45    18.1  666.67    16.1  707.03   13.02  731.49    9.77
  759.27    8.67 1324.09   10.41 1330.61    9.78    1350    3.67    1380    4.67
    1418    1.87    1420    8.27 1439.25    9.55 1617.26    7.79 1643.96    4.72
 1661.76    7.32 1697.36    9.02 1893.17     9.1 1919.87   12.26 1946.57   10.97
 1982.17   12.17 1991.07   13.44 2017.78   25.33 2026.68   26.87 2067.95   27.89
#Mann= 4 ,-1 , 0
       0     .06       0  707.03      .1       0 1324.09     .04       0
 1439.25     .05       0
Bank Sta=1330.61,1439.25
XS Rating Curve= 0 ,0
Exp/Cntr=0.3,0.1

Type RM Length L Ch R = 1 ,11721   ,73.01,114.39,102.49
BEGIN DESCRIPTION:
underwater portion from baltimore district hecras model xsec 2.39 adjusted .5' vertically
END DESCRIPTION:
XS GIS Cut Line= 4
1645970.03279346708376.8204579951644836.14792016 709431.58784382
1644829.79666723709571.3154090341644467.77524824709971.444345832
#Sta/Elev= 30
       0   38.99  133.85   35.61  305.93   28.09  363.29   27.02  420.66   23.36
  592.74   16.47   747.3   15.82  803.07   13.66  850.87    8.16  925.32    8.36
 1465.63    9.37 1555.63    9.27 1576.65    6.04    1580    3.47    1610    4.47
    1612    3.47    1648    1.67    1650    8.07 1660.73    7.23 1674.75    9.16
 1707.37    8.87 1735.69    4.87 1801.77   11.15 1830.09    8.57  2047.2    8.56
 2075.52   11.65 2132.16   14.01 2160.48   23.25 2179.36   27.35 2228.08   27.74
#Mann= 6 ,-1 , 0
       0     .06       0   747.3      .1       0  925.32     .07       0
 1465.63     .11       0 1555.63     .04       0 1674.75     .05       0
Bank Sta=1555.63,1674.75
XS Rating Curve= 0 ,0
Exp/Cntr=0.3,0.1

Type RM Length L Ch R = 1 ,11607   ,97.29,112.57,106.33
BEGIN DESCRIPTION:
underwater portion from baltimore district hecras model xsec 2.35
END DESCRIPTION:
XS GIS Cut Line= 4
1645843.33456638708427.0135277661644717.34444527709463.785852388
1644720.42092104709562.2330760811644397.39096828709940.639592171
#Sta/Elev= 30
       0   36.51  180.79   29.06  228.37   28.75  266.43   26.78  314.01   21.53
   371.1   21.75  437.71    17.1  542.38   15.36  579.93   16.41  637.53   13.36
  694.62    8.15  774.09    8.33 1401.88     9.1 1493.91    9.31  1530.6    6.59
    1540    2.97    1570    3.97    1572    2.97    1608    1.17 1614.64    5.67
 1635.17    8.39 1702.73   10.07 1730.34    8.61 1923.62    8.57 1951.23   11.83
 1997.25   13.38 2015.66   17.06 2034.06   24.79 2043.27   26.51 2126.63   26.81
#Mann= 7 ,-1 , 0
       0     .06       0  579.93      .1       0  774.09     .07       0
 1401.88     .11       0 1493.91     .04       0 1635.17     .11       0
 1635.17     .05       0
Bank Sta=1493.91,1635.17
XS Rating Curve= 0 ,0
Exp/Cntr=0.3,0.1

Type RM Length L Ch R = 1 ,11494   ,156.94,194.8,219.24
BEGIN DESCRIPTION:
underwater portion from baltimore district hecras model xsec 2.33
END DESCRIPTION:
XS GIS Cut Line= 4
1645735.15815723 708424.165736781644620.31119806709452.853563219
 1644599.4241356709570.3432895841644314.83790952709904.536289066
#Sta/Elev= 30
       0   35.77    76.2   31.15  161.92   27.92  200.02   25.07  247.64    19.1
  352.41   15.42  445.55   15.29  514.33   14.42     581    7.66  662.82    8.69
  704.82    7.44  847.69    8.94 1190.58    7.91 1407.41    9.16 1524.04    9.22
 1545.37    6.47    1550    2.97    1580    3.97    1618    1.17    1620    7.57
    1626    8.57 1630.69     6.6 1654.65    8.86 1687.56    7.17 1728.21    4.26
 1801.76       7 1847.73   12.63  1893.7   14.97 1939.67   26.06 2075.21   26.61
#Mann= 7 ,-1 , 0
       0     .06       0  445.55      .1       0  662.82     .07       0
 1407.41     .11       0 1524.04     .04       0 1630.69     .11       0
 1687.56     .05       0
Bank Sta=1524.04,1626
XS Rating Curve= 0 ,0
Exp/Cntr=0.3,0.1

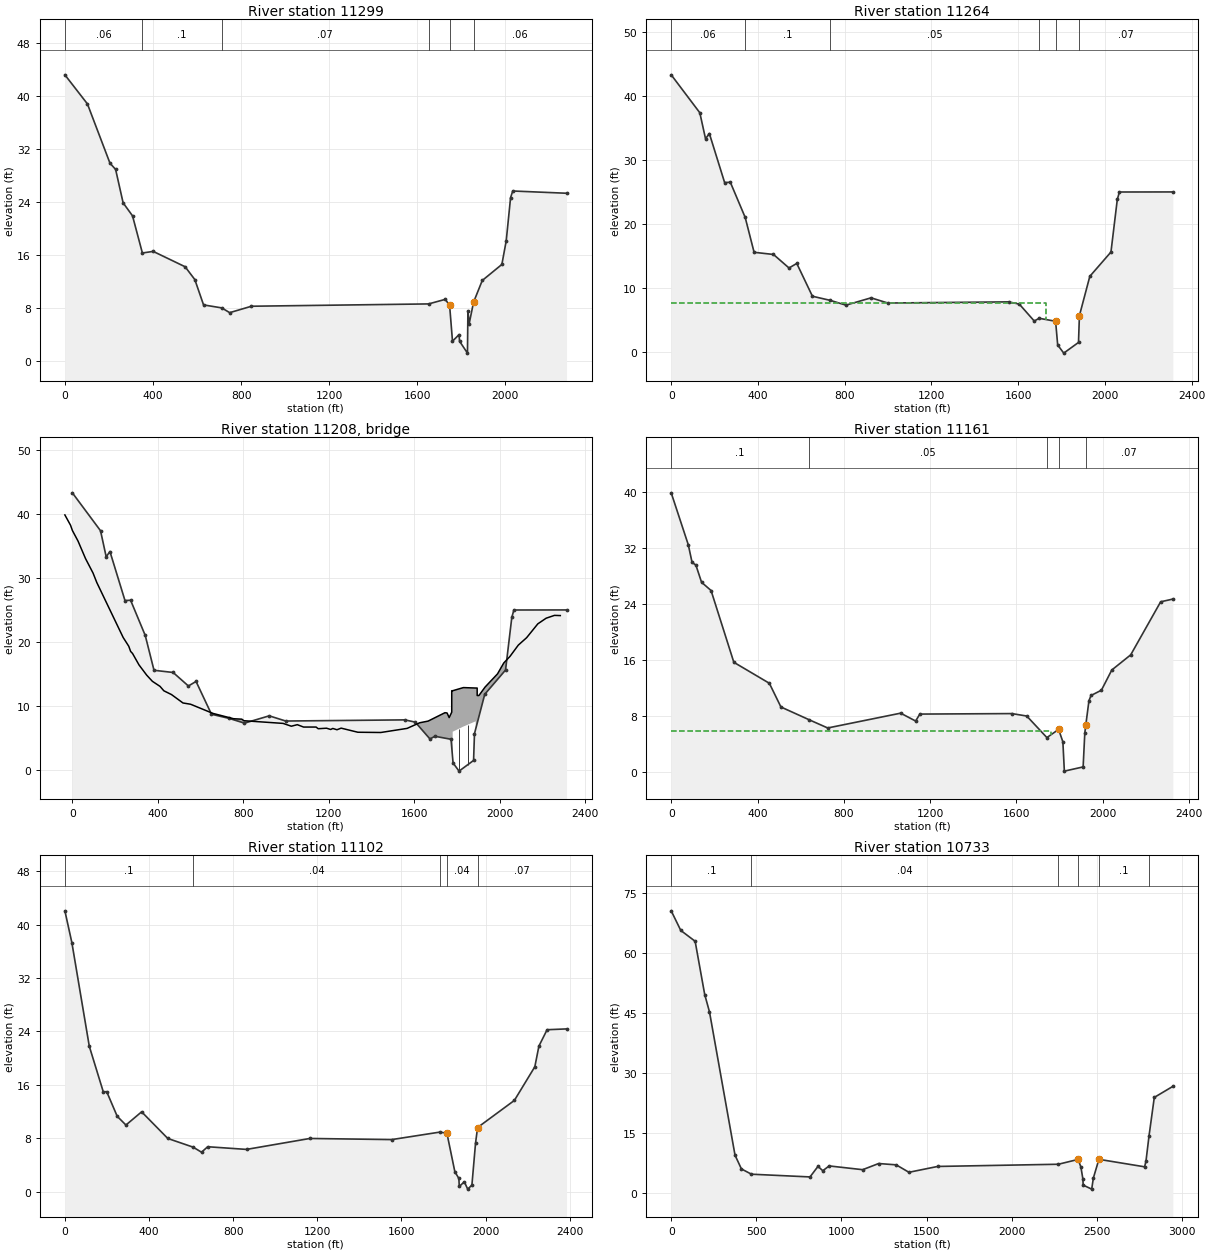
Type RM Length L Ch R = 1 ,11299   ,37.67,35.83,31.73
BEGIN DESCRIPTION:
underwater portion from baltimore district hecras model xsec 2.30
END DESCRIPTION:
XS GIS Cut Line= 3
 1645757.3640378708270.8847951291645289.40504898708596.977973446
1644083.62771629709805.847042903
#Sta/Elev= 30
       0   43.19  102.38    38.8  204.77   29.85  230.36   28.91  264.49   23.86
  307.15    21.9  351.92   16.29     401   16.53  546.04   14.21  590.14   12.27
  629.69    8.45  712.26       8  748.33    7.28   847.2    8.25 1651.62     8.6
 1727.13    9.29  1746.9    8.39    1760    2.97    1790    3.97    1792    2.97
    1828    1.17    1830    7.57 1835.89    5.64 1855.66    8.86 1895.21   12.14
 1984.19   14.56 2003.96   18.13 2023.74   24.65 2033.62   25.65 2277.79   25.31
#Mann= 6 ,-1 , 0
       0     .06       0  351.92      .1       0  712.26     .07       0
 1651.62     .11       0  1746.9     .04       0 1855.66     .06       0
Bank Sta=1746.9,1855.66
XS Rating Curve= 0 ,0
Exp/Cntr=0.5,0.3

Type RM Length L Ch R = 1 ,11264   ,103.36,102.09,101.08
BEGIN DESCRIPTION:
underwater portion from baltimore dist hecras model xsec 2.29 and the deepest invert elevations adjusted as per MDE bridge inspection measurements (taken in 2007) to account for the sedimentation that is taking place within the channel.
END DESCRIPTION:
XS GIS Cut Line= 6
1645754.80218904708215.1517912151645479.11360839708424.902575344
1645263.31327882708596.6168675721644639.86909059 709195.92490229
1644290.38801619709555.8649388551644057.14876066709781.242510781
#Sta/Elev= 30
       0   43.24  131.94   37.32  158.32   33.26  175.91   34.08  246.28   26.43
  272.67   26.47  341.18   20.98  382.19   15.54  471.65    15.2  543.21   13.09
     579    13.8  651.16    8.68  733.93    8.03  805.64    7.29   921.5    8.43
  998.74    7.62 1555.89     7.8 1605.11    7.45 1674.01    4.81 1696.63    5.24
 1772.43    4.77    1782    1.07    1810     -.2    1878    1.47  1882.2    5.65
 1930.26   11.79 2027.66   15.58 2056.87   23.78 2066.61   24.95 2313.06   24.96
#Mann= 6 ,-1 , 0
       0     .06       0  341.18      .1       0  733.93     .05       0
 1696.63      .1       0 1772.43     .04       0    1878     .07       0
#XS Ineff= 2 , 0
       0    1730    7.59    1940       0    11.6
Permanent Ineff=
       F       F
Bank Sta=1772.43,1882.2
XS Rating Curve= 0 ,0
Exp/Cntr=0.5,0.3

Type RM Length L Ch R = 3 ,11208   ,,,
BEGIN DESCRIPTION:
Delaware Avenue - CE050907PF-5   Geometry taken from Baltimore District's HEC-RAS model.  Top of road from LIDAR.  A hydraulic engineer from the COE Baltimore District indicated that this bridge has a major sedimentation problem.  The channel is dredged every 3 to 4 years.  It is dredged deep and wide, and acts like a sediment trap.  The COE RAS model contains a xsection with an underclearance of 8.5 feet (2000).  The MDE survey crew measured an underclearance of 6 feet.   The 2007 MDE survey data was used.
END DESCRIPTION:
Bridge Culvert--1,0,-1,-1, 0
Deck Dist Width WeirC Skew NumUp NumDn MinLoCord MaxHiCord MaxSubmerge Is_Ogee
46,20,2.6,0, 60, 60, , , 0.95, 0, 0,0,,
     -35   -8.61     .18   26.57   61.75   96.94  114.53  237.67  264.05  272.85
  281.64  311.95  347.74  374.57  410.35  428.25  464.03   517.7  553.48  658.06
  754.61  793.23  802.88  986.33 1024.95  1052.9 1082.21 1140.83  1150.6 1189.68
 1209.22 1218.99 1238.53 1258.07 1336.23 1443.71 1566.83 1625.88 1665.26    1744
 1753.84 1763.68 1775.74 1775.75 1780.18 1830.47    1888 1894.85 1894.86 1902.92
 1931.75 1990.01 2019.22 2048.43 2087.37 2126.32 2178.69 2217.61 2256.53 2283.93
   39.79   38.19   37.36   35.71   32.97   30.71   29.23   20.67   19.29   18.48
   18.17   16.38   14.79   13.82   13.03   12.34   11.75   10.44   10.24    8.81
    7.98    7.91    7.67    7.25    6.81    7.05    6.68    6.68    6.42     6.5
     6.3    6.46    6.26    6.51    5.87    5.83    6.47    7.35    7.61    8.92
    8.88    8.16       9   12.35   12.35   12.84   12.77   12.77    11.6    11.6
   12.92   14.98   16.68   17.71   19.47   20.63   22.79   23.67   24.11   24.08
                                                                                
                                                                                
                                                                                
                                                                                
                                    5.95    6.76    7.58
                                                                                
       0   26.39   35.18   61.57   96.75  131.94  149.53  272.67  299.05  307.85
  316.64  346.95  382.74  409.57  445.35  463.25  499.03   552.7  588.48  693.06
  789.61  828.23  837.88 1021.33 1059.95  1087.9 1117.21 1175.83  1185.6 1224.68
 1244.22 1253.99 1273.53 1293.07 1371.23 1478.71 1601.83 1660.88 1700.26    1779
 1788.84 1798.68 1810.74 1810.75 1815.18 1865.47    1923 1929.85 1929.86 1937.92
 1966.75 2025.01 2054.22 2083.43 2122.37 2161.32 2213.69 2252.61 2291.53 2318.93
   39.79   38.19   37.36   35.71   32.97   30.71   29.23   20.67   19.29   18.48
   18.17   16.38   14.79   13.82   13.03   12.34   11.75   10.44   10.24    8.81
    7.98    7.91    7.67    7.25    6.81    7.05    6.68    6.68    6.42     6.5
     6.3    6.46    6.26    6.51    5.87    5.83    6.47    7.35    7.61    8.92
    8.88    8.16       9   12.35   12.35   12.84   12.77   12.77    11.6    11.6
   12.92   14.98   16.68   17.71   19.47   20.63   22.79   23.67   24.11   24.08
                                                                                
                                                                                
                                                                                
                                                                                
                                    5.95    6.76    7.58
                                                                                
Pier Skew, UpSta & Num, DnSta & Num=  ,1810, 2 ,1845, 2 , 0 , 0 , 0 ,,
       3       3
   -5.83    6.37
       3       3
   -5.83    6.47
Pier Skew, UpSta & Num, DnSta & Num=  ,1852, 2 ,1887, 2 , 0 , 0 , 0 ,,
       3       3
   -4.83   13.17
       3       3
   -4.83   13.17
BR Coef=-1 , 1 , 0 ,, 0 ,,,0.8,0,0.5,6,
WSPro=,,,, 1 ,,,, 0 ,,,, 0 ,,,,-1 ,-1 ,-1 , 0 , 0 , 0 , 0 , 0
BR U #Sta/Elev= 30
       0   43.24  131.94   37.32  158.32   33.26  175.91   34.08  246.28   26.43
  272.67   26.47  341.18   20.98  382.19   15.54  471.65    15.2  543.21   13.09
     579    13.8  651.16    8.68  733.93    8.03  805.64    7.29   921.5    8.43
  998.74    7.62 1555.89     7.8 1605.11    7.45 1674.01    4.81 1696.63    5.24
 1772.43    4.77    1782    1.07    1810     -.2    1878    1.47  1882.2    5.65
 1930.26   11.79 2027.66   15.58 2056.87   23.78 2066.61   24.95 2313.06   24.96
BR U #Mann= 6
       0     .06  341.18      .1  733.93     .05 1696.63      .1 1772.43    .038
    1878     .07
BR D #Sta/Elev= 30
       0   39.83   79.16   32.43   96.75   29.91  114.34   29.54  140.73   27.08
  184.71   25.91  290.26   15.68  454.84   12.69  508.52    9.31  639.32    7.49
   725.3    6.32 1063.23    8.43 1132.76    7.31  1152.3     8.3 1578.86    8.37
 1647.76    8.02 1741.05    4.95  1795.4    6.11 1815.09    4.35    1822     .17
    1909     .77 1916.73    5.58 1921.13    6.69 1935.96    10.2 1945.57   10.95
 1993.64    11.7 2041.84   14.58 2129.46   16.74 2268.23    24.3 2324.81   24.69
BR D #Mann= 5
       0      .1  639.32     .05 1741.05      .1  1795.4    .038 1921.13     .07
BC Design=,, 0 ,, 0 ,,,,,,
BC Use User HTab Curves=0
BC User HTab FreeFlow(D)= 0

Type RM Length L Ch R = 1 ,11161   ,49.43,58.98,64.28
BEGIN DESCRIPTION:
underwater portion from baltimore district hecras model xsec 2.28 and the deepest invert elevations adjusted as per MDE bridge inspection measurements (taken in 2007) to account for the sedimentation that is taking place within the channel.
END DESCRIPTION:
XS GIS Cut Line= 6
1645694.25224848708135.5672154431645417.69911291708345.975774676
1645197.61744878708521.0967638641644569.42271197709124.944475085
1644219.18719368709485.6080936341643987.68930931709709.302364722
#Sta/Elev= 30
       0   39.83   79.16   32.43   96.75   29.91  114.34   29.54  140.73   27.08
  184.71   25.91  290.26   15.68  454.84   12.69  508.52    9.31  639.32    7.49
   725.3    6.32 1063.23    8.43 1132.76    7.31  1152.3     8.3 1578.86    8.37
 1647.76    8.02 1741.05    4.95  1795.4    6.11 1815.09    4.35    1822     .17
    1909     .77 1916.73    5.58 1921.13    6.69 1935.96    10.2 1945.57   10.95
 1993.64    11.7 2041.84   14.58 2129.46   16.74 2268.23    24.3 2324.81   24.69
#Mann= 5 ,-1 , 0
       0      .1       0  639.32     .05       0 1741.05      .1       0
  1795.4     .04       0 1921.13     .07       0
#XS Ineff= 2 , 0
       0    1760    5.95    1970       0    6.69
Permanent Ineff=
       F       F
Bank Sta=1795.4,1921.13
XS Rating Curve= 0 ,0
Exp/Cntr=0.5,0.3

Type RM Length L Ch R = 1 ,11102   ,339.91,369.55,396.39
BEGIN DESCRIPTION:
underwater portion from baltimore dist hecras model xsec 2.26
END DESCRIPTION:
XS GIS Cut Line= 3
1645697.66073044708115.6561959681645255.88976324708396.296518669
1643915.37283984709687.833015978
#Sta/Elev= 30
       0   42.06   33.17   37.31   116.1   21.77  182.45   14.96  199.03   14.96
  248.79   11.28  290.26    9.97  364.89   11.95  489.29    7.96  609.56    6.66
  649.74     5.9   678.9    6.72  863.59    6.32 1164.92    7.96 1553.73    7.79
 1781.95    8.91 1816.18    8.75    1854    2.97    1873    1.97    1875     .77
    1899    1.47    1915     .37    1935     .97 1952.26    7.25 1961.98     9.6
 2136.95   13.66 2234.15    18.7 2253.59    21.8 2292.47   24.25 2384.84   24.37
#Mann= 5 ,-1 , 0
       0      .1       0  609.56     .04       0 1781.95      .1       0
 1816.18     .04       0 1961.98     .07       0
Bank Sta=1816.18,1961.98
XS Rating Curve= 0 ,0
Exp/Cntr=0.3,0.1

Type RM Length L Ch R = 1 ,10733   ,502.35,456.23,417.14
BEGIN DESCRIPTION:
underwater portion from baltimore dist hecras model xsec 2.16 adj 2 ft vertically
END DESCRIPTION:
XS GIS Cut Line= 3
1645876.86393896707449.334635437 1644121.9132047709011.882133067
1643608.04497242709315.692674115
#Sta/Elev= 30
       0   70.45   56.24   65.55  140.59   62.84  196.82   49.53  224.94   45.17
   374.9    9.36  412.39    5.92  471.48     4.6  815.41    3.92  862.28    6.56
  890.39    5.47  927.88    6.67 1124.71    5.73 1218.43    7.27 1321.53    6.94
 1396.51    5.08 1565.22    6.54 2274.28    7.09 2390.43     8.3 2406.69    6.36
    2418    3.47    2420    1.87    2470     .87 2479.88    3.66  2512.4    8.32
 2780.76    6.45 2788.89    7.88 2806.46   14.09 2837.68    23.8 2946.72   26.56
#Mann= 6 ,-1 , 0
       0      .1       0  471.48     .04       0 2274.28     .12       0
 2390.43     .04       0  2512.4      .1       0 2806.46     .07       0
Bank Sta=2390.43,2512.4
XS Rating Curve= 0 ,0
Exp/Cntr=0.3,0.1

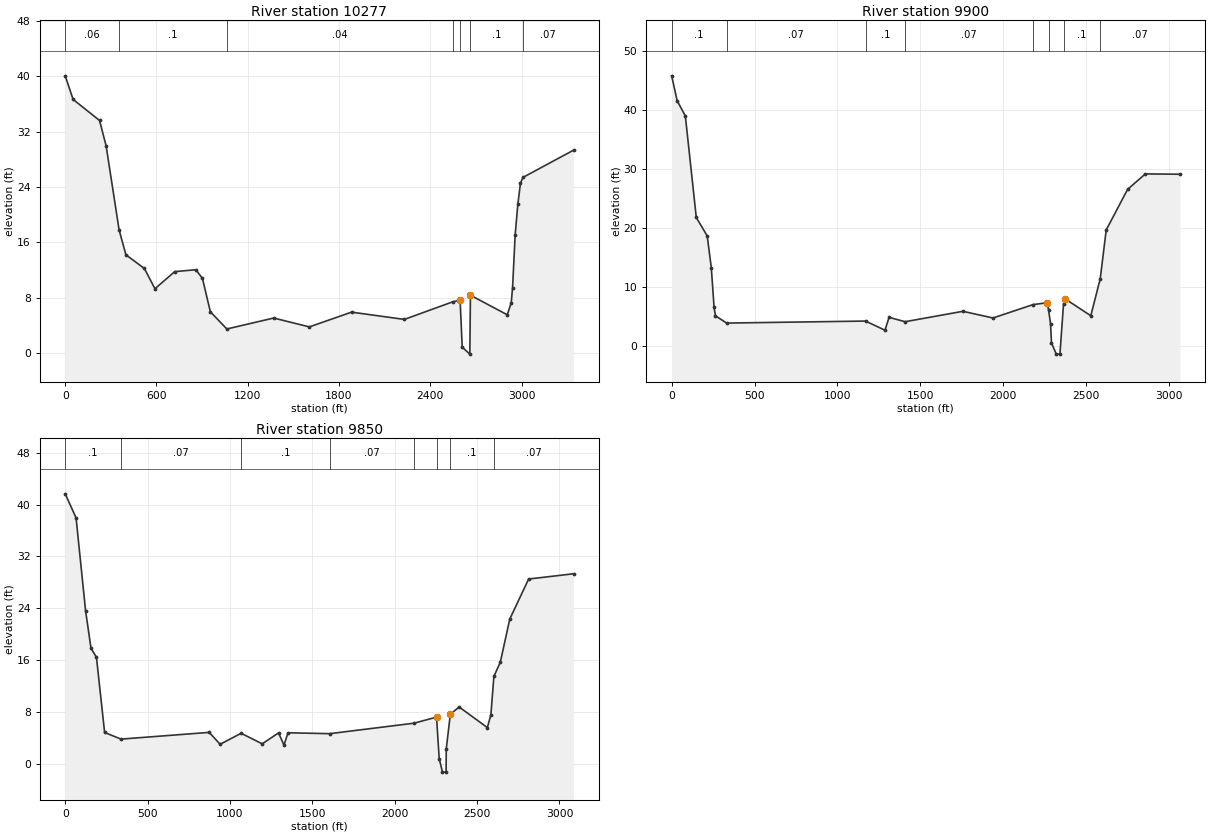
Type RM Length L Ch R = 1 ,10277   ,368.9,376.28,375.6
BEGIN DESCRIPTION:
underwater portion from baltimore dist hecras model xsec 2.16 adjusted vertically 1ft
END DESCRIPTION:
XS GIS Cut Line= 2
1645337.26237249706571.2240038511643363.43066598709267.715406179
#Sta/Elev= 30
       0   40.04   52.05   36.63  225.55    33.6  268.92   29.94  354.22   17.81
  399.05   14.21   520.5   12.23   589.9    9.31  720.02   11.78  858.82   12.05
   902.2    10.8  954.25    5.98 1062.67     3.5 1370.65    5.08 1604.87     3.8
 1882.47    5.93 2229.47    4.88 2546.39    7.41    2596    7.67    2610     .87
    2660    -.13    2664    8.37 2906.12    5.55 2932.14    7.27 2940.82    9.43
 2958.17   17.13 2975.52   21.47 2992.87   24.55 3009.55   25.38 3341.72   29.31
#Mann= 7 ,-1 , 0
       0     .06       0  354.22      .1       0 1062.67     .04       0
 2546.39     .12       0    2596     .04       0    2664      .1       0
 3009.55     .07       0
Bank Sta=2596,2664
XS Rating Curve= 0 ,0
Exp/Cntr=0.3,0.1

Type RM Length L Ch R = 1 ,9900    ,51.99,50.02,53.92
BEGIN DESCRIPTION:
underwater portion from baltimore district hecras model section 2.03
END DESCRIPTION:
XS GIS Cut Line= 4
1644708.64113741706551.4418530321643519.66585281708459.622426823
1643429.07810678708518.6571377661643282.15121563709213.054672778
#Sta/Elev= 30
       0   45.72   32.99   41.52   82.48   38.93  148.46   21.77  214.44   18.65
  239.18   13.25  255.68    6.62  263.93    5.15  331.46    3.92 1169.45    4.26
 1286.64    2.71 1311.38    4.89    1408    4.15 1756.76    5.91  1938.2    4.78
 2179.45    7.04    2265    7.36 2273.36    6.15 2285.23    3.81    2291     .57
    2320   -1.33    2342   -1.33 2363.57    7.13 2370.73    8.06 2528.14    5.16
 2585.11   11.42 2621.15   19.66 2749.94   26.52 2857.27   29.14 3066.19   29.08
#Mann= 8 ,-1 , 0
       0      .1       0  331.46     .07       0 1169.45      .1       0
    1408     .07       0 2179.45      .1       0 2273.36     .04       0
 2363.57      .1       0 2585.11     .07       0
Bank Sta=2265,2370.73
XS Rating Curve= 0 ,0
Exp/Cntr=0.5,0.3

Type RM Length L Ch R = 1 ,9850    ,45.69,40.08,43.13
BEGIN DESCRIPTION:
underwater portion from baltimore dist hecras model section 2.03
END DESCRIPTION:
XS GIS Cut Line= 4
 1644666.2049042706525.0001036521643483.08714223708423.779968172
1643384.44426626708488.0640896411643233.23423123709202.704376176
#Sta/Elev= 30
       0   41.66   65.98   37.95  123.72   23.58  156.71   17.79   189.7   16.41
  239.18     4.8  338.47    3.77  874.25    4.81  940.24    2.97 1067.86    4.67
 1195.91    3.04 1294.89    4.73 1327.88    2.84 1352.62    4.75 1605.04    4.61
 2117.53    6.23 2253.93    7.17    2270     .77    2290   -1.33    2312   -1.33
 2312.83    2.22 2337.48    7.59 2390.73    8.74 2562.45    5.55 2583.92    7.55
 2601.94   13.45 2641.16   15.67  2698.4   22.31 2812.88    28.5 3085.42   29.31
#Mann= 8 ,-1 , 0
       0      .1       0  338.47     .07       0 1067.86      .1       0
 1605.04     .07       0 2117.53      .1       0 2253.93     .04       0
 2337.48      .1       0 2601.94     .07       0
#XS Ineff= 2 , 0
       0    2210    3.03    2378       0    5.27
Permanent Ineff=
       F       F
Bank Sta=2253.93,2337.48
XS Rating Curve= 0 ,0
Exp/Cntr=0.5,0.3