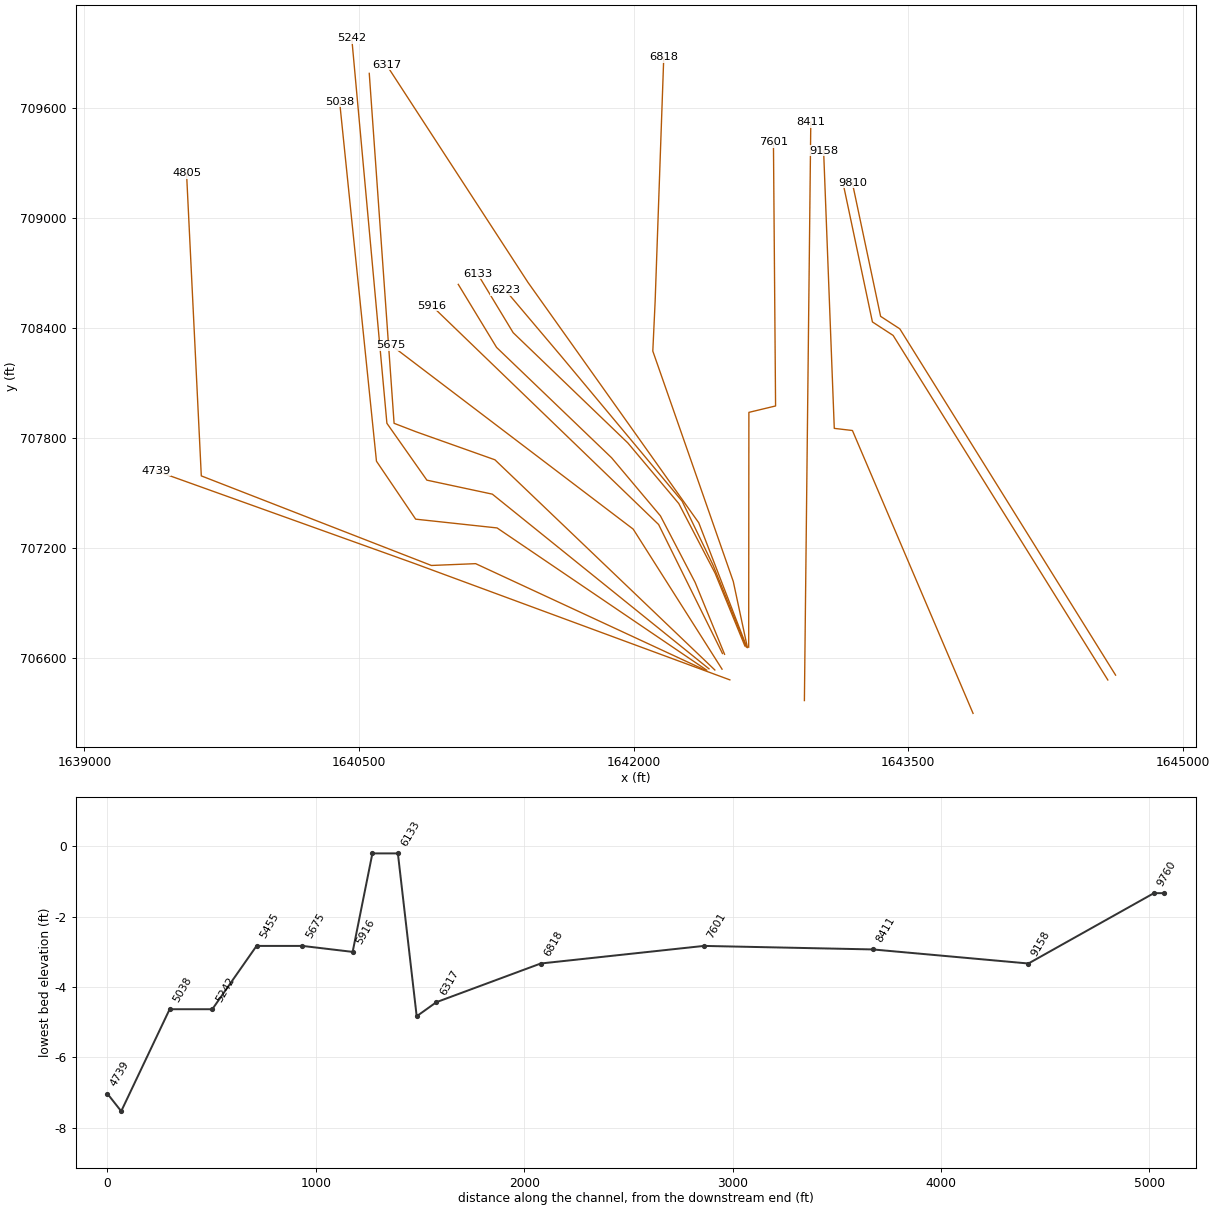
HEC-RAS study bigelkcreek.prj: Big Elk Creek

--- bigelkcreek.g23 (geometry) --- (continued)

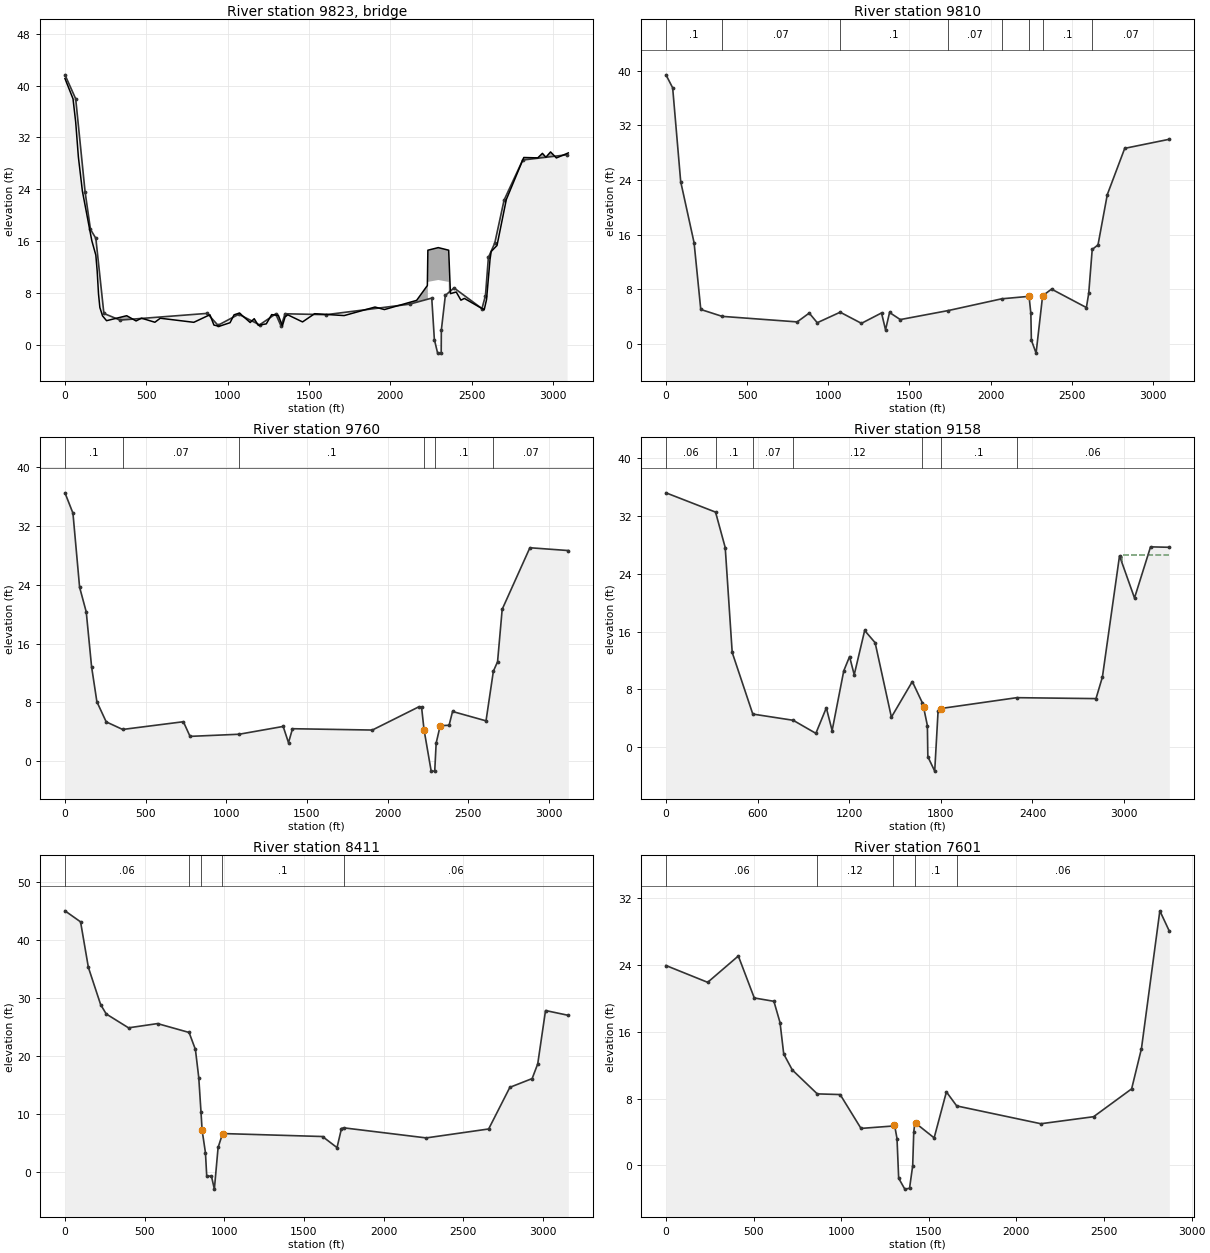
Type RM Length L Ch R = 3 ,9823    ,,,
BEGIN DESCRIPTION:
Pedestrian Bridge  Elevations for low chord and top of railing from Baltimore District 2000 survey data.
END DESCRIPTION:
Bridge Culvert--1,0,-1,-1, 0
Deck Dist Width WeirC Skew NumUp NumDn MinLoCord MaxHiCord MaxSubmerge Is_Ogee
22,10,2.6,0, 60, 60, , , 0.95, 0, 0,0,,
       0   49.49   65.98   82.48  107.22  164.95   189.7  197.94  206.19  214.44
  230.93  255.68  379.39  437.13  470.12  552.59  585.58  791.78  890.75  915.49
  948.48 1014.46 1039.21  1072.2 1138.18 1162.92 1187.67 1237.15 1270.14 1311.38
 1336.12 1352.62 1369.11 1459.84 1534.07 1715.52 1905.21 1962.95 2160.89 2226.87
    2230    2294    2358 2368.68 2404.46 2433.08 2454.54 2576.18 2590.49 2611.95
 2619.11 2654.88 2712.12 2819.45 2905.31 2933.93 2955.39 2984.01 3019.79 3093.12
   41.09   37.96   34.35   28.96   23.68   16.04   13.81   11.36     7.8    5.72
    4.42    3.68    4.45    3.64    4.07    3.44    4.06    3.43     4.6       3
    2.82    3.37    4.59    4.86     3.4    3.99    2.97    3.19    4.62     4.5
    2.88    4.26    4.59    3.49    4.76    4.47    5.79     5.4    6.82    9.11
   14.57   14.97   14.57    7.86    8.11    6.85    7.12    5.36    6.93   13.13
   14.37    15.3    22.4   28.89   28.83   29.53   28.93   29.75   28.82    29.6
                                                                                
                                                                                
                                                                                
                                                                                
    9.67    9.97    9.67
                                                                                
       0   49.49   65.98   82.48  107.22  164.95   189.7  197.94  206.19  214.44
  230.93  255.68  379.39  437.13  470.12  552.59  585.58  791.78  890.75  915.49
  948.48 1014.46 1039.21  1072.2 1138.18 1162.92 1187.67 1237.15 1270.14 1311.38
 1336.12 1352.62 1369.11 1459.84 1534.07 1715.52 1905.21 1962.95 2160.89 2226.87
    2230    2294    2358 2368.68 2404.46 2433.08 2454.54 2576.18 2590.49 2611.95
 2619.11 2654.88 2712.12 2819.45 2905.31 2933.93 2955.39 2984.01 3019.79 3093.12
   41.09   37.96   34.35   28.96   23.68   16.04   13.81   11.36     7.8    5.72
    4.42    3.68    4.45    3.64    4.07    3.44    4.06    3.43     4.6       3
    2.82    3.37    4.59    4.86     3.4    3.99    2.97    3.19    4.62     4.5
    2.88    4.26    4.59    3.49    4.76    4.47    5.79     5.4    6.82    9.11
   14.57   14.97   14.57    7.86    8.11    6.85    7.12    5.36    6.93   13.13
   14.37    15.3    22.4   28.89   28.83   29.53   28.93   29.75   28.82    29.6
                                                                                
                                                                                
                                                                                
                                                                                
    9.67    9.97    9.67
                                                                                
BR Coef=-1 , 0 , 0 ,, 0 ,,,0.8,0,,0,
WSPro=,,,, 1 ,,,, 0 ,,,, 0 ,,,,-1 ,-1 ,-1 , 0 , 0 , 0 , 0 , 0
BR U #Sta/Elev= 30
       0   41.66   65.98   37.95  123.72   23.58  156.71   17.79   189.7   16.41
  239.18     4.8  338.47    3.77  874.25    4.81  940.24    2.97 1067.86    4.67
 1195.91    3.04 1294.89    4.73 1327.88    2.84 1352.62    4.75 1605.04    4.61
 2117.53    6.23 2253.93    7.17    2270     .77    2290   -1.33    2312   -1.33
 2312.83    2.22 2337.48    7.59 2390.73    8.74 2562.45    5.55 2583.92    7.55
 2601.94   13.45 2641.16   15.67  2698.4   22.31 2812.88    28.5 3085.42   29.31
BR U #Mann= 8
       0      .1  338.47     .07 1067.86      .1 1605.04     .07 2117.53      .1
 2253.93    .038 2337.48      .1 2601.94     .07
BR D #Sta/Elev= 30
       0    39.4   41.24    37.5   90.72   23.77   173.2   14.83  214.44    5.06
  346.36    4.05  808.27    3.24   882.5    4.53  931.99    3.12 1073.19    4.66
 1204.16    3.03 1327.88    4.55 1352.62    2.08 1377.36    4.62 1443.34    3.58
 1738.93     4.9 2068.24    6.62 2236.71    6.98 2247.77    4.49    2251     .57
    2280   -1.33 2320.26    7.06 2375.25    8.04  2589.9    5.34 2604.21    7.41
 2625.76   13.84 2661.45   14.51 2718.69   21.87 2826.02   28.64 3100.81   29.97
BR D #Mann= 8
       0      .1  346.36     .07 1073.19      .1 1738.93     .07 2068.24      .1
 2236.71    .038 2320.26      .1 2625.76     .07
BC Design=,, 0 ,, 0 ,,,,,,
BC Use User HTab Curves=0
BC User HTab FreeFlow(D)= 0

Type RM Length L Ch R = 1 ,9810    ,60.53,50.08,53.92
BEGIN DESCRIPTION:
underwater portion from baltimore dist hecras model xsec 2.03
END DESCRIPTION:
XS GIS Cut Line= 4
1644632.25591759 706503.846704171643453.82417382708395.106001258
1643348.73719382708463.5896511671643194.10064371709194.424138904
#Sta/Elev= 30
       0    39.4   41.24    37.5   90.72   23.77   173.2   14.83  214.44    5.06
  346.36    4.05  808.27    3.24   882.5    4.53  931.99    3.12 1073.19    4.66
 1204.16    3.03 1327.88    4.55 1352.62    2.08 1377.36    4.62 1443.34    3.58
 1738.93     4.9 2068.24    6.62 2236.71    6.98 2247.77    4.49    2251     .57
    2280   -1.33 2320.26    7.06 2375.25    8.04  2589.9    5.34 2604.21    7.41
 2625.76   13.84 2661.45   14.51 2718.69   21.87 2826.02   28.64 3100.81   29.97
#Mann= 8 ,-1 , 0
       0      .1       0  346.36     .07       0 1073.19      .1       0
 1738.93     .07       0 2068.24      .1       0 2236.71     .04       0
 2320.26      .1       0 2625.76     .07       0
#XS Ineff= 2 , 0
       0    2210    4.12    2378       0    5.25
Permanent Ineff=
       F       F
Bank Sta=2236.71,2320.26
XS Rating Curve= 0 ,0
Exp/Cntr=0.5,0.3

Type RM Length L Ch R = 1 ,9760    ,677.29,602.22,243.23
BEGIN DESCRIPTION:
underwater portion from baltimore dist hecras model xsec 2.03
END DESCRIPTION:
XS GIS Cut Line= 4
1644589.81968439706477.404954836 1643417.2454633708359.263542607
1643304.10335335708432.9966030721643145.18365937709184.073842332
#Sta/Elev= 30
       0   36.47   49.49   33.71   90.72   23.65  131.96   20.29  164.95   12.86
  197.94    8.09  255.68    5.36  357.56    4.33  734.04    5.38  775.28    3.39
 1079.53    3.68 1352.62    4.74 1385.61    2.53 1410.35    4.43 1905.21    4.25
 2193.88    7.41 2210.38    7.36 2225.63    4.31    2270   -1.33    2292   -1.33
 2300.83    2.47  2325.9    4.84 2380.95     4.9 2402.41    6.77 2609.91     5.5
 2655.46   12.24 2681.46   13.53 2710.08   20.65  2881.8   29.01 3120.04   28.63
#Mann= 6 ,-1 , 0
       0      .1       0  357.56     .07       0 1079.53      .1       0
 2225.63     .04       0    2292      .1       0 2655.46     .07       0
Bank Sta=2225.63,2325.9
XS Rating Curve= 0 ,0
Exp/Cntr=0.3,0.1

Type RM Length L Ch R = 1 ,9158    ,584.69,746.51,120.27
BEGIN DESCRIPTION:
underwater portion from baltimore district hecras model xsec 1.89
END DESCRIPTION:
XS GIS Cut Line= 4
1643853.71475361706294.9152155371643194.87942812707839.971509844
1643095.76260926707851.6323120591643037.45859817709367.536600813
#Sta/Elev= 30
       0    35.2   324.7   32.53   388.1   27.62  433.76    13.1  568.64    4.57
  833.02    3.71  981.67     1.9 1050.16    5.43 1088.21    2.28 1164.31   10.55
 1202.36   12.53  1232.8   10.01 1301.28   16.14 1369.77   14.45 1476.31    4.14
 1613.29    9.07 1679.66     6.1 1686.71    5.56    1712    2.97    1715   -1.33
    1760   -3.33    1782    4.97 1800.48    5.34 2297.65    6.84 2816.22    6.71
 2858.25     9.7 2970.34   26.48 3068.41   20.64 3173.48   27.72 3296.48   27.66
#Mann= 7 ,-1 , 0
       0     .06       0   324.7      .1       0  568.64     .07       0
  833.02     .12       0 1679.66    .055       0 1800.48      .1       0
 2297.65     .06       0
#XS Ineff= 2 , 0
                         2984.66           26.65
Permanent Ineff=
       F       F
Bank Sta=1686.71,1800.48
XS Rating Curve= 0 ,0
Exp/Cntr=0.3,0.1

Type RM Length L Ch R = 1 ,8411    ,781.69,810.62,185.96
BEGIN DESCRIPTION:
underwater portion from baltimore district hecras model xsec 1.76
END DESCRIPTION:
XS GIS Cut Line= 2
1642932.51137814706364.880028874 1642967.4937848709524.957430795
#Sta/Elev= 30
       0      45   98.01    43.1  147.01   35.26  224.01   28.85  259.02   27.24
  399.02   24.85  581.04   25.58  779.33   24.05  819.05   21.12  840.05   16.28
  854.05   10.37  861.05    7.22  882.05    3.34     890    -.63     920    -.73
     938   -2.93  961.43    4.24  987.06    6.41  994.06    6.64  1617.1    6.13
 1708.11    4.22 1736.11    7.51  1748.9    7.63 2268.15    5.89 2660.18    7.43
 2793.19    14.6  2933.2   16.11  2968.2   18.64  3017.2   27.83 3160.29      27
#Mann= 5 ,-1 , 0
       0     .06       0  779.33     .12       0  854.05    .055       0
  987.06      .1       0  1748.9     .06       0
Bank Sta=861.05,994.06
XS Rating Curve= 0 ,0
Exp/Cntr=0.3,0.1

Type RM Length L Ch R = 1 ,7601    ,721.58,782.75,678.14
BEGIN DESCRIPTION:
underwater portion from baltimore district hecras model xsec 1.60
END DESCRIPTION:
XS GIS Cut Line= 4
1642628.19382957706656.6030888411642629.33052041707939.088328704
1642775.09054814 707974.070735381642763.42974591 709414.17980969
#Sta/Elev= 30
       0   23.91     238    21.9     413   25.05     504   20.03     616   19.63
     651   17.08     672   13.33     721   11.42  863.49    8.56     994    8.48
    1113    4.43 1296.88    4.72 1304.08    4.88 1318.48    3.22    1328   -1.53
    1363   -2.83    1390   -2.73    1408    -.03    1414    3.97 1419.26    4.96
 1426.46    5.03 1530.39     3.3 1600.39     8.8 1659.18    7.12 2139.41    4.99
 2440.42    5.83 2657.43    9.16 2713.43   13.97 2818.43   30.45 2872.54   28.02
#Mann= 5 ,-1 , 0
       0     .06       0  863.49     .12       0 1296.88    .055       0
 1419.26      .1       0 1659.18     .06       0
Bank Sta=1304.08,1426.46
XS Rating Curve= 0 ,0
Exp/Cntr=0.3,0.1

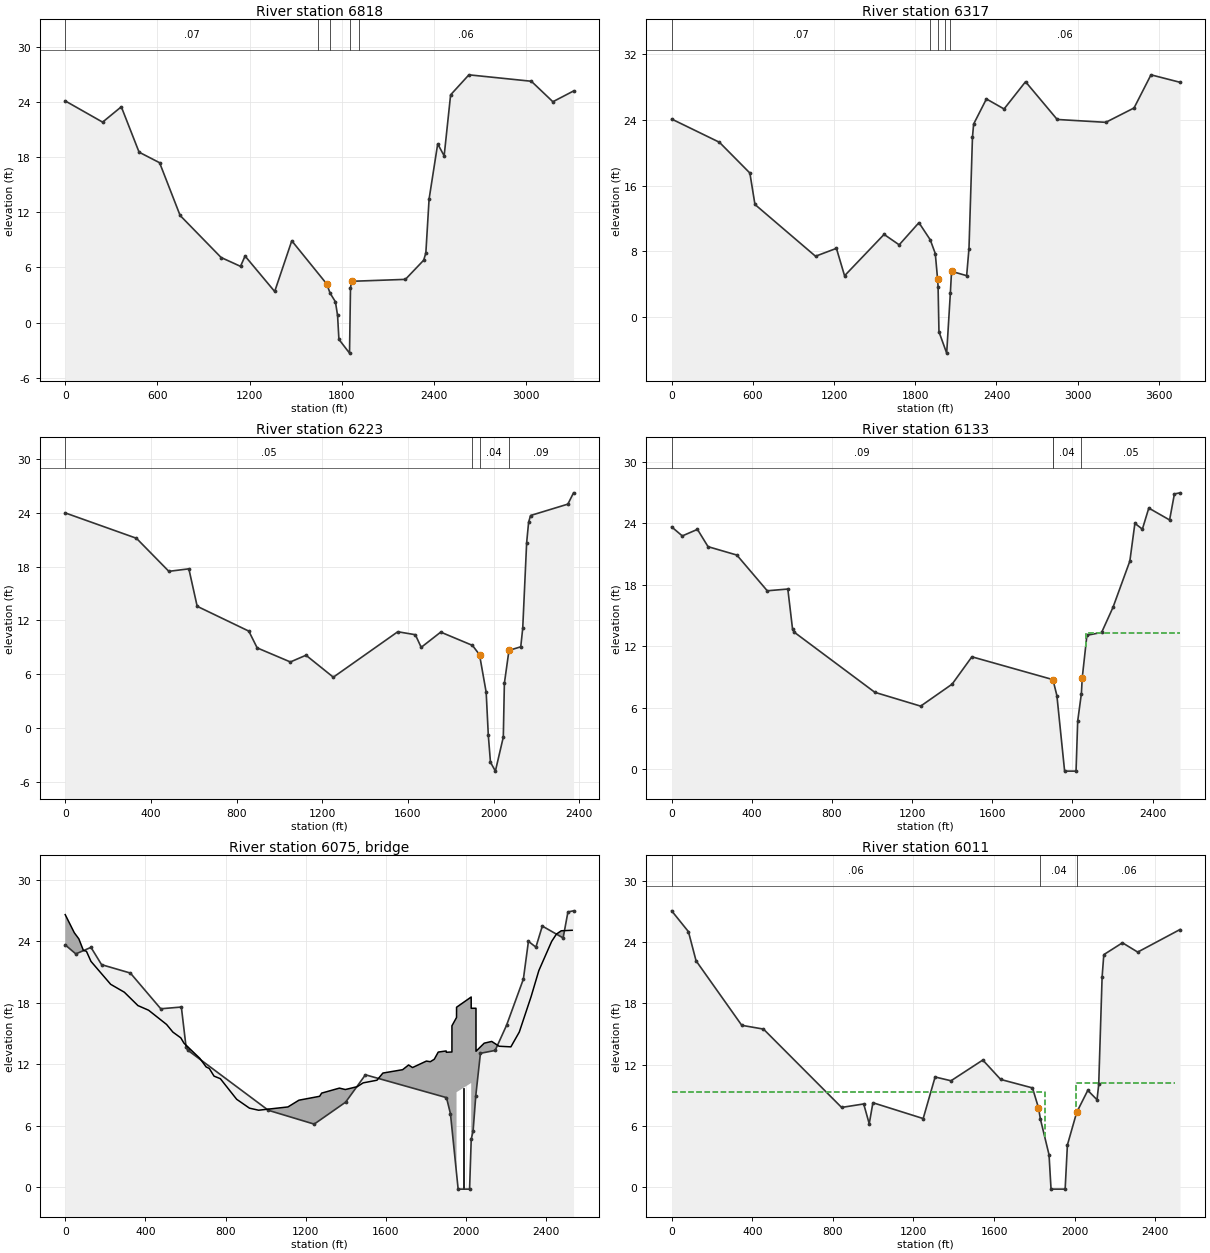
Type RM Length L Ch R = 1 ,6818    ,437.18,500.76,561.92
BEGIN DESCRIPTION:
underwater portion from baltimore district hecras model xsec 1.49
END DESCRIPTION:
XS GIS Cut Line= 5
1642621.26331119 706654.292916031642543.99588421707015.610023588
1642104.52632444708273.7688439041642117.28686918708546.742116466
1642164.31741884709878.066140428
#Sta/Elev= 30
       0   24.13  243.38   21.82  365.07   23.49  480.71   18.55  614.17    17.4
  747.64   11.66 1014.57    7.08 1140.62    6.12 1170.28    7.24 1363.06    3.38
 1474.29     8.9 1702.19    4.19 1723.22    3.21 1758.26    2.26 1772.27     .77
    1781   -1.83    1850   -3.33 1856.36    3.77 1863.37    4.49 2213.62     4.7
 2332.69    6.79  2346.7    7.58 2367.71   13.44 2423.75   19.45 2465.77   18.15
  2507.8   24.79 2626.88   26.97 3033.13   26.27 3173.22   24.04 3307.63   25.21
#Mann= 5 ,-1 , 0
       0     .07       0 1647.61      .1       0 1723.22     .04       0
 1856.36      .1       0 1911.74     .06       0
Bank Sta=1702.19,1863.37
XS Rating Curve= 0 ,0
Exp/Cntr=0.3,0.1

Type RM Length L Ch R = 1 ,6317    ,84.96,94.32,101.61
BEGIN DESCRIPTION:
underwater portion from baltimore district hecras model xsec 1.39
END DESCRIPTION:
XS GIS Cut Line= 5
1642617.87986791706656.7264679671642355.59343961707335.793890998
1641649.20550661708330.1976879541641422.41689922708649.239288151
1640649.93618661709836.947412461
#Sta/Elev= 30
       0    24.1  352.69   21.27  577.81   17.52  615.33   13.69 1062.83    7.38
 1217.39    8.34 1277.49       5 1569.43   10.04 1681.05    8.77 1827.02   11.47
 1910.67    9.38 1947.73    7.71  1964.9    4.58 1968.51    3.65    1975   -1.83
    2032   -4.43 2059.41    2.94 2067.96    5.54 2179.61    5.01 2196.79    8.32
 2222.55   21.89 2231.14   23.49 2325.62   26.55 2456.07   25.33 2614.72   28.65
 2848.53   24.05  3207.6    23.7 3416.36   25.45 3541.61   29.49 3755.99   28.58
#Mann= 5 ,-1 , 0
       0     .07       0 1910.67      .1       0 1968.51     .04       0
 2019.59      .1       0 2059.41     .06       0
Bank Sta=1964.9,2067.96
XS Rating Curve= 0 ,0
Exp/Cntr=0.3,0.1

Type RM Length L Ch R = 1 ,6223    ,79.54,90.19,103.27
BEGIN DESCRIPTION:
underwater portion from baltimore district hecras model xsec 1.36
END DESCRIPTION:
XS GIS Cut Line= 5
1642614.37775847706659.061207578 1642432.2680691707107.331212223
1642264.76111473707453.8277948651641605.97160007708243.729874894
 1641299.0108636708606.894689813
#Sta/Elev= 30
       0   23.98  332.45   21.15  483.85   17.46  577.15   17.74  616.03   13.56
  857.05   10.79  896.06    8.92 1051.01    7.35 1123.93     8.1 1251.54    5.65
 1552.34   10.72 1634.37   10.39 1661.72    8.98 1752.87   10.68 1900.84     9.2
 1933.94    8.16    1965    3.97    1975    -.83    1985   -3.83    2008   -4.83
    2045   -1.03    2050    4.97 2071.42    8.64 2126.41    9.04 2135.58   11.09
 2153.91   20.64 2163.08   22.93 2172.24   23.69 2346.39   24.96 2372.79   26.22
#Mann= 4 ,-1 , 0
       0     .05       0 1900.84      .1       0 1933.94     .04       0
 2071.42     .09       0
Bank Sta=1933.94,2071.42
XS Rating Curve= 0 ,0
Exp/Cntr=0.5,0.3

Type RM Length L Ch R = 1 ,6133    ,120.07,122.3,121.12
BEGIN DESCRIPTION:
underwater portion from Baltimore District hecras model xsec 1.35 and the deepest invert elevations adjusted to -0.2 feet as per MDE bridge inspection measurements (taken in 2007) to account for the sedimentation that is taking place within the channel.
END DESCRIPTION:
XS GIS Cut Line= 6
1642607.48577063706663.1624934971642444.72344613707060.767600581
1642246.34847671707440.9862920051641967.96725118707772.195866689
1641341.73109932708374.2926801151641147.00545423708696.121267274
#Sta/Elev= 30
       0   23.66   52.95   22.78  128.58   23.42  181.53   21.73  325.24   20.91
     477   17.42  579.64   17.59  603.33   13.66  611.23   13.38 1013.94     7.5
 1242.54    6.15 1399.65     8.3 1498.28   10.97 1902.68    8.74 1922.41    7.18
    1961     -.2    2018     -.2 2026.27    4.69 2044.64    7.37 2048.95    8.92
  2072.2   13.07  2145.7   13.35 2202.37    15.8 2286.49   20.32 2311.73   24.01
 2349.03   23.44    2381    25.5  2484.9   24.34 2508.88   26.88 2536.79   26.99
#Mann= 4 ,-1 , 0
       0     .09       0 1902.68      .1       0 1902.68     .04       0
 2044.64     .05       0
#XS Ineff= 2 , 0
       0    1913    7.86    2066       0   13.27
Permanent Ineff=
       F       F
Bank Sta=1902.68,2048.95
XS Rating Curve= 0 ,0
Exp/Cntr=0.5,0.3

Type RM Length L Ch R = 3 ,6075    ,,,
BEGIN DESCRIPTION:
Bridge Street.  CE050907PF-7  Top of road from LIDAR. Bridge and channel geometry taken directly from Baltimore District's HEC-RAS model .  The underclearance of the bridge as coded in Baltimore's RAS model (as surveyed in the year 2000)  is approx 4' deeper than the bridge inspection notes (surveyed 2007).  It is assumed that this large difference is due to the sedimenation problems this channel is experiencing.  The underclearance from the MDE 2007 survey was adopted.
END DESCRIPTION:
Bridge Culvert--1,0,-1,-1, 0
Deck Dist Width WeirC Skew NumUp NumDn MinLoCord MaxHiCord MaxSubmerge Is_Ogee
40,35,2.6,0, 60, 60, , , 0.95, 0, 0,0,,
       0   45.38   68.07   90.77  105.89  128.58  226.91  294.99  363.06  416.01
  505.81  537.39  576.87  592.66  671.62   703.2  718.99  742.68  774.26  855.52
  919.53  965.25 1111.55 1166.42 1269.76 1279.63  1368.4 1397.99 1457.17 1486.76
  1555.8 1585.39 1684.03 1713.62 1733.34 1802.39 1822.11 1841.84 1861.57 1901.02
    1902  1929.9    1930  1952.9    1953    2026  2026.1    2050  2050.1    2091
 2128.48 2165.22 2224.11 2266.17 2325.06 2363.62 2427.56 2451.54 2475.52 2529.94
   26.62   24.85   24.25   23.12   23.04   22.05   19.81   19.04   17.73   17.28
   15.89   15.14   14.58   14.06   12.58   11.74   11.59   10.84   10.59    8.58
    7.71    7.51    7.83    8.49    8.87    9.18    9.67    9.53    9.81   10.18
   10.44   11.14   11.47   11.93   11.68   12.31   12.25   12.49   13.19    13.3
   13.17    13.2   15.76   16.57   17.57   18.57   17.47   17.47   13.27   14.06
   14.23   13.76    13.7   15.15   18.61   21.15      24   24.72   25.04   25.09
                                                                                
                                                                                
                                                                                
                                                                                
       0               0       0    9.27   10.17       0       0       0
                                                                                
       0    7.56   15.13   45.38   68.07   90.77  105.89  128.58  226.91  294.99
  363.06  416.01  505.81  537.39  576.87  592.66  671.62   703.2  718.99  742.68
  774.26  829.53  855.52  919.53  965.25 1111.55 1166.42 1269.76 1279.63  1368.4
 1397.99  1555.8 1585.39 1684.03 1713.62 1733.34 1762.93 1802.39 1822.11 1841.84
 1861.57    1870    1870  1893.9    1894    1967  1967.1    1990  1990.1 1990.67
 2128.48 2165.22 2224.11 2266.17 2325.06 2363.62 2427.56 2451.54 2475.52 2529.94
   26.62   26.21   26.19   24.85   24.25   23.12   23.04   22.05   19.81   19.04
   17.73   17.28   15.89   15.14   14.58   14.06   12.58   11.74   11.59   10.84
   10.59    9.06    8.58    7.71    7.51    7.83    8.49    8.87    9.18    9.67
    9.53   10.44   11.14   11.47   11.93   11.68   11.79   12.31   12.25   12.49
   13.19   13.25   15.76   16.57   17.47   18.47   17.47   17.47   14.06   14.06
   14.23   13.76    13.7   15.15   18.61   21.15      24   24.72   25.04   25.09
                                                                                
                                                                                
                                                                                
                                                                                
                                    9.27   10.17       0       0       0
                                                                                
Pier Skew, UpSta & Num, DnSta & Num=  ,1989.65, 2 ,1930, 2 , 0 , 0 , 0 ,,
       5       5
   -6.83    9.67
       5       5
   -6.83    9.57
BR Coef=-1 , 1 , 0 ,, 0 ,,,0.8,0,1.2,1,
WSPro=,,,, 1 ,,,, 0 ,,,, 0 ,,,,-1 ,-1 ,-1 , 0 , 0 , 0 , 0 , 0
BR U #Sta/Elev= 30
       0   23.66   52.95   22.78  128.58   23.42  181.53   21.73  325.24   20.91
     477   17.42  579.64   17.59  603.33   13.66  611.23   13.38 1013.94     7.5
 1242.54    6.15 1399.65     8.3 1498.28   10.97 1902.68    8.74 1922.41    7.18
    1961     -.2    2018     -.2 2026.27    4.69 2035.45    5.44 2048.95    8.92
  2072.2   13.07  2145.7   13.35 2202.37    15.8 2286.49   20.32 2311.73   24.01
 2349.03   23.44    2381    25.5  2484.9   24.34 2508.88   26.88 2536.79   26.99
BR U #Mann= 3
       0     .09 1902.68    .035 2048.95     .05
BR D #Sta/Elev= 30
       0   27.05    83.2   25.01  121.02   22.16  347.93   15.84  455.67   15.47
  843.41     7.8  953.14    8.14  980.57     6.2  998.86    8.26 1248.38    6.71
 1307.56   10.78 1386.47   10.41 1544.28   12.44 1633.05   10.54 1790.86    9.71
 1820.46    7.78    1873    3.17    1883     -.2    1953     -.2 1964.25    4.13
 1982.64    6.22 2019.38    7.64 2065.32    9.47 2111.25    8.55 2119.65   10.05
 2136.48   20.57 2144.89   22.76 2237.43   23.92 2313.15   23.01 2523.08   25.22
BR D #Mann= 3
       0     .06 1820.46    .035 2019.38     .06
BR D Banks=1820.46,
BC Design=,, 0 ,, 0 ,,,,,,
BC Use User HTab Curves=0
BC User HTab FreeFlow(D)= 0

Type RM Length L Ch R = 1 ,6011    ,92.5,94.74,87.57
BEGIN DESCRIPTION:
underwater portion from baltimore district hecras model xsec 1.34   and the deepest invert elevations adjusted to -0.2 feet as per MDE bridge inspection measurements (taken in 2007) to account for the sedimentation that is taking place within the channel.
END DESCRIPTION:
XS GIS Cut Line= 6
1642496.43048395706617.7012650521642335.76861697707010.175254375
1642146.03455658707373.8322034481641879.58624373 707690.84435907
1641251.20768464 708293.744725631641041.90486345708638.208696842
#Sta/Elev= 30
       0   27.05    83.2   25.01  121.02   22.16  347.93   15.84  455.67   15.47
  843.41     7.8  953.14    8.14  980.57     6.2  998.86    8.26 1248.38    6.71
 1307.56   10.78 1386.47   10.41 1544.28   12.44 1633.05   10.54 1790.86    9.71
 1820.46    7.78 1830.32    6.65    1873    3.17    1883     -.2    1953     -.2
 1964.25    4.13  2010.2    7.31 2065.32    9.47 2111.25    8.55 2119.65   10.05
 2136.48   20.57 2144.89   22.76 2237.43   23.92 2313.15   23.01 2523.08   25.22
#Mann= 3 ,-1 , 0
       0     .06       0 1830.32     .04       0  2010.2     .06       0
#XS Ineff= 2 ,-1
       0    1854    9.27    2007    2500   10.17
Permanent Ineff=
       F       F
Bank Sta=1820.46,2010.2
XS Rating Curve= 0 ,0
Exp/Cntr=0.5,0.3

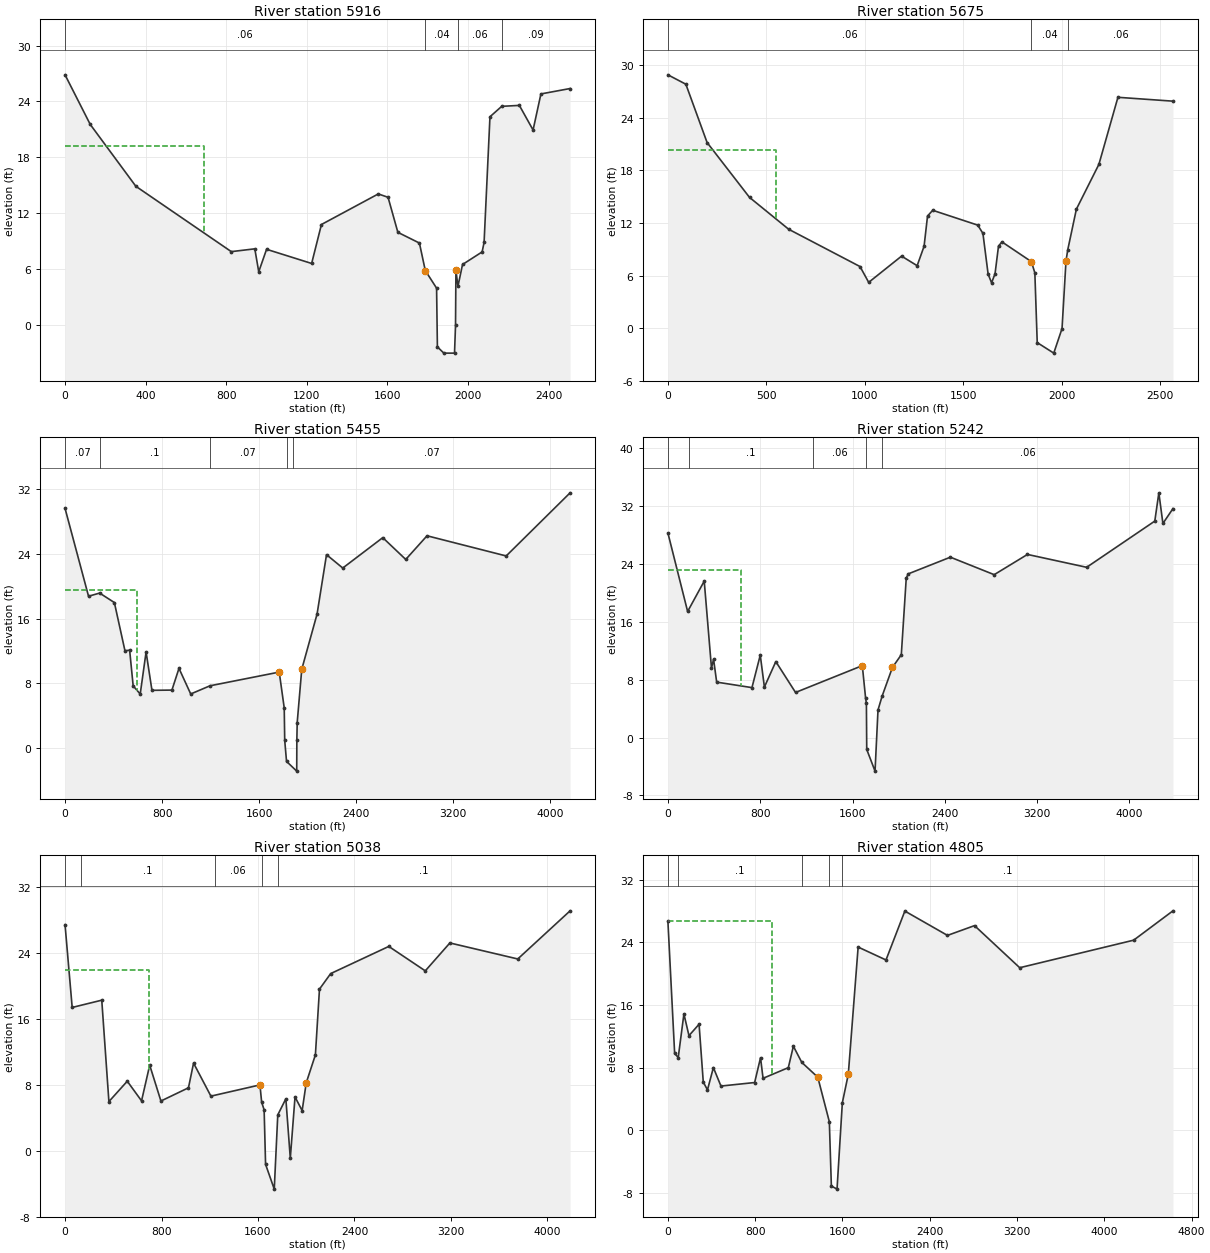
Type RM Length L Ch R = 1 ,5916    ,224.07,240.8,247.49
BEGIN DESCRIPTION:
underwater portion from baltimore district hecras model xsec 1.32.  The deepest underwater point were adjusted to -3 ft based on the sedimentation that is occuring withing the stream - as per Baltimore District comments pertaining Bridge Street immediately upstream.
END DESCRIPTION:
XS GIS Cut Line= 3
1642484.96311621706621.9504968971642136.12702391707326.553199813
  1640897.874405708520.912535608
#Sta/Elev= 30
       0   26.86  124.97   21.54  351.49    14.9  825.13    7.89  941.84    8.19
  961.29    5.73 1000.19    8.14 1223.88    6.62 1272.51    10.8 1554.55   14.08
 1603.18   13.72 1651.81    9.96 1758.79    8.81 1787.96    5.86    1844    3.97
    1848   -2.33    1880      -3    1933      -3    1938    -.03    1940    5.87
    1950    4.17 1972.75    6.51 2070.01    7.86 2079.73    8.88 2108.91   22.36
 2167.26   23.48 2254.79   23.58 2322.87   20.94 2361.77   24.81 2506.62   25.39
#Mann= 4 ,-1 , 0
       0     .06       0 1787.96     .04       0    1950     .06       0
 2167.26     .09       0
#XS Ineff= 2 , 0
          688.34   19.19
Permanent Ineff=
       F       F
Bank Sta=1787.96,1940
XS Rating Curve= 0 ,0
Exp/Cntr=0.3,0.1

Type RM Length L Ch R = 1 ,5675    ,184.17,220.25,246.45
BEGIN DESCRIPTION:
underwater portion from baltimore district hecras model xsec 1.27
END DESCRIPTION:
XS GIS Cut Line= 3
 1642482.6529434706536.4741034211641997.51665618707301.141299054
 1640675.9481879708305.524491936
#Sta/Elev= 30
       0   28.87   91.19    27.8  198.96   21.16   414.5   14.91  613.46   11.28
  975.92    7.03 1019.88    5.23 1186.93    8.22 1266.06    7.13 1301.23    9.34
 1318.81   12.79 1345.19   13.44 1573.78   11.75 1600.16   10.81 1626.53    6.17
 1644.12    5.18  1661.7    6.21 1679.29    9.36 1696.87    9.84 1846.34    7.59
 1863.92    6.31    1876   -1.63    1960   -2.83    2002    -.03 2022.18    7.67
 2030.97    8.93 2074.93   13.57 2189.23   18.67 2285.95   26.31  2565.5   25.87
#Mann= 3 ,-1 , 0
       0     .06       0 1846.34     .04       0 2030.97     .06       0
#XS Ineff= 1 ,-1
       0  550.5320.25864
Permanent Ineff=
       F
Bank Sta=1846.34,2022.18
XS Rating Curve= 0 ,0
Exp/Cntr=0.3,0.1

Type RM Length L Ch R = 1 ,5455    ,199.11,212.41,225
BEGIN DESCRIPTION:
underwater portion from baltimore district hecras model xsec 1.24
END DESCRIPTION:
XS GIS Cut Line= 5
1642443.38000588706531.8537578281641242.09015168707680.009637684
1640812.05130303707832.8124901211640691.36016136707879.272409439
1640555.72188118709790.796750143
#Sta/Elev= 30
       0   29.59  193.66   18.75  285.22   19.14  406.69   17.97  493.84   12.03
  532.57   12.09  561.62    7.69  619.71    6.68  668.13   11.87  716.55    7.14
  881.16    7.17  939.26    9.85 1036.09    6.69    1195     7.7 1765.73    9.39
    1807    4.97    1811     .97    1826   -1.63    1910   -2.83    1911     .97
    1914    3.17 1951.45    9.73 2077.74   16.55 2155.61   23.88 2289.54   22.23
 2619.36   25.98 2808.84   23.29 2984.28   26.21 3636.91   23.72 4163.76   31.51
#Mann= 5 ,-1 , 0
       0     .07       0  285.22      .1       0    1195     .07       0
 1826.64     .04       0 1877.02     .07       0
#XS Ineff= 1 ,-1
       0  595.9519.53613
Permanent Ineff=
       F
Bank Sta=1765.73,1951.45
XS Rating Curve= 0 ,0
Exp/Cntr=0.3,0.1

Type RM Length L Ch R = 1 ,5242    ,193.98,204.6,212.87
BEGIN DESCRIPTION:
underwater portion from baltimore district hecras model xsec 1.19
END DESCRIPTION:
XS GIS Cut Line= 5
 1642411.3815015706538.2731033411641228.02645859707492.353106678
1640870.46829803 707568.830824391640652.12008049707879.272409439
1640460.07284006709982.094832331
#Sta/Elev= 30
       0    28.3  170.84   17.45  314.71   21.65  377.65    9.62  395.64   10.85
  422.61    7.68  728.33    6.92  800.27   11.41  836.23       7  935.14   10.52
 1105.99    6.25 1684.71    9.96 1713.34    5.44 1720.09    4.75    1723   -1.63
    1795   -4.63 1820.72    3.83 1856.51    5.75 1945.62    9.71 2022.64   11.47
 2065.43   22.06 2082.55   22.65 2448.01   24.96 2827.58   22.54 3115.77   25.34
 3628.89   23.56 4219.33   29.95 4254.48   33.86 4289.63   29.62 4376.81   31.68
#Mann= 5 ,-1 , 0
       0     .06       0  182.17      .1       0  1258.3     .06       0
 1713.34     .04       0 1856.51     .06       0
#XS Ineff= 1 ,-1
 -224.54  631.7223.18325
Permanent Ineff=
       F
Bank Sta=1684.71,1945.62
XS Rating Curve= 0 ,0
Exp/Cntr=0.3,0.1

Type RM Length L Ch R = 1 ,5038    ,214.47,232.37,243.34
BEGIN DESCRIPTION:
underwater portion from baltimore district hecras model xsec 1.14.
END DESCRIPTION:
XS GIS Cut Line= 5
1642399.05488645706530.8771343231641253.75826743707307.839087948
1640809.17288138707355.7405436781640595.04359926707672.370164856
1640393.71522976 709637.07753785
#Sta/Elev= 30
       0   27.39   59.21   17.37  304.52   18.25  363.73    5.97  515.98    8.44
  634.41    6.06  702.08   10.38  795.12    6.04 1023.51    7.64  1065.8   10.63
  1209.6    6.63 1616.31    7.99 1630.39     5.9    1651    4.97    1663   -1.63
    1735   -4.63 1764.16    4.36 1831.13    6.31 1868.02    -.89 1907.18    6.53
 1966.33    4.88 2000.14    8.24 2076.19   11.63 2109.99   19.59 2202.95   21.47
 2684.82   24.76 2987.39    21.8 3191.46   25.18 3754.38   23.24 4188.35   29.07
#Mann= 5 ,-1 , 0
       0     .06       0  132.06      .1       0 1240.46     .06       0
 1630.39     .04       0 1764.16      .1       0
#XS Ineff= 1 ,-1
       0   692.721.89503
Permanent Ineff=
       F
Bank Sta=1616.31,2000.14
XS Rating Curve= 0 ,0
Exp/Cntr=0.3,0.1

Type RM Length L Ch R = 1 ,4805    ,108.7,66.37,24.75
BEGIN DESCRIPTION:
underwater portion was not adjusted.  baltimore district hecras model xsec 1.09 was higher than lidar surface.
END DESCRIPTION:
XS GIS Cut Line= 5
1642389.88066533706531.3344819841641136.80950734707112.693363741
1640895.20785277707102.8320717361639638.32110779707592.105720654
 1639557.6339612709246.906279191
#Sta/Elev= 30
       0   26.68   61.73    9.81   94.43    9.28  146.62   14.85  192.92   12.08
  285.52   13.54   324.1    6.15  362.68    5.15   416.7       8  486.15    5.64
  794.82    6.09  848.83    9.26  871.98    6.63 1103.48    7.99 1149.78   10.73
 1227.07    8.66 1373.57    6.77 1479.45    1.08    1498   -7.13    1550   -7.53
 1598.55     3.5 1653.21    7.14 1743.35    23.4 1998.75   21.75 2171.52      28
 2562.13   24.89 2810.02   26.14 3224.23   20.76 4268.47   24.28  4628.7   28.03
#Mann= 5 ,-1 , 0
       0     .07       0   94.43      .1       0 1227.07     .07       0
 1479.45     .04       0 1598.55      .1       0
#XS Ineff= 2 ,-1
       0  956.74  26.678    2500    4000      22
Permanent Ineff=
       F       F
Bank Sta=1373.57,1653.21
XS Rating Curve= 0 ,0
Exp/Cntr=0.5,0.3

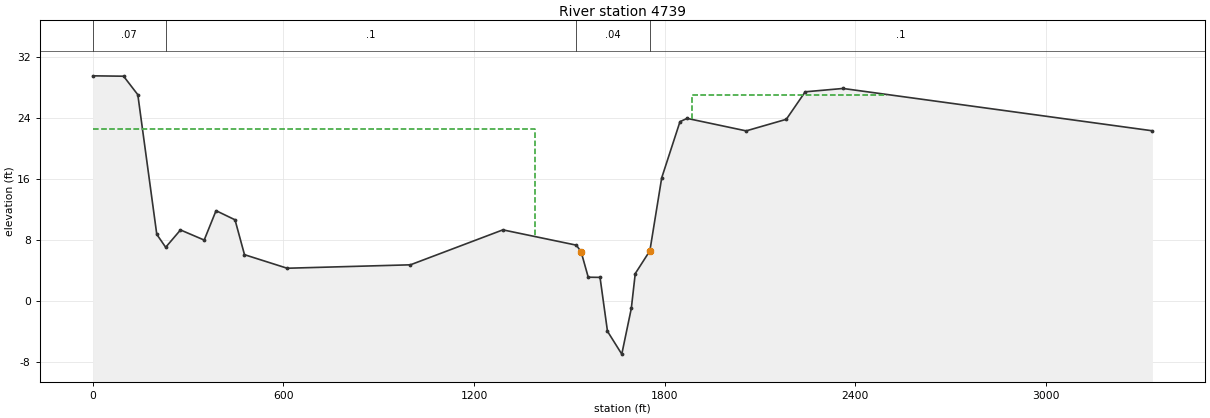
Type RM Length L Ch R = 1 ,4739    ,288.68,265.53,246.66
BEGIN DESCRIPTION:
underwater portion from baltimore district hecras model xsec 1.08
END DESCRIPTION:
XS GIS Cut Line= 3
1642525.34560004706477.9539189191640798.39347114 707115.18264918
1639391.62964863707619.488377467
#Sta/Elev= 30
       0   29.52      97   29.47  141.77   27.04  201.46     8.7  229.46       7
  276.07    9.28  350.68    7.95  387.99   11.81  447.68   10.61  477.53    6.03
  611.83    4.25  999.82     4.7 1290.81    9.29 1522.11    7.28 1537.03    6.41
 1559.42    3.07 1596.56    3.05    1620   -4.03    1665   -7.03    1695   -1.03
 1707.43    3.55 1753.41    6.54 1790.72   16.13  1848.2    23.5 1870.51   23.93
 2056.41   22.29 2182.83   23.81 2242.32   27.42  2361.3   27.86  3335.2    22.3
#Mann= 4 ,-1 , 0
       0     .07       0  229.46      .1       0 1522.11     .04       0
 1753.41      .1       0
#XS Ineff= 2 ,-1
   -1.56 1392.26 22.5801    1887    2500   26.98
Permanent Ineff=
       F       F
Bank Sta=1537.03,1753.41
XS Rating Curve= 0 ,0
Exp/Cntr=0.5,0.3