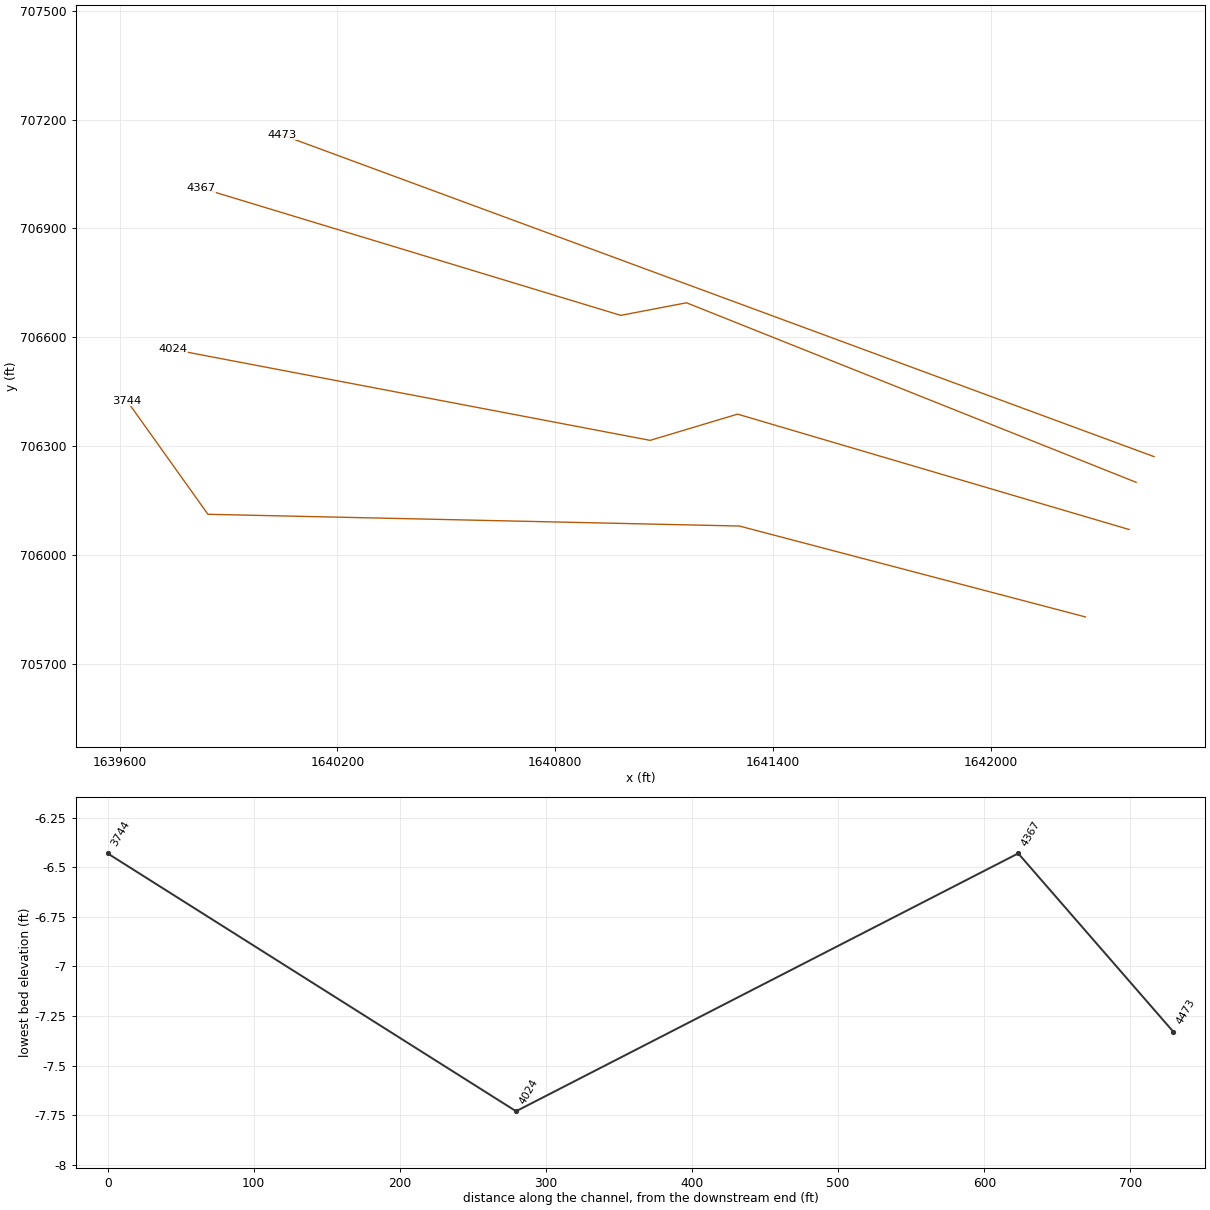
HEC-RAS study bigelkcreek.prj: Big Elk Creek

--- bigelkcreek.g23 (geometry) --- (continued)

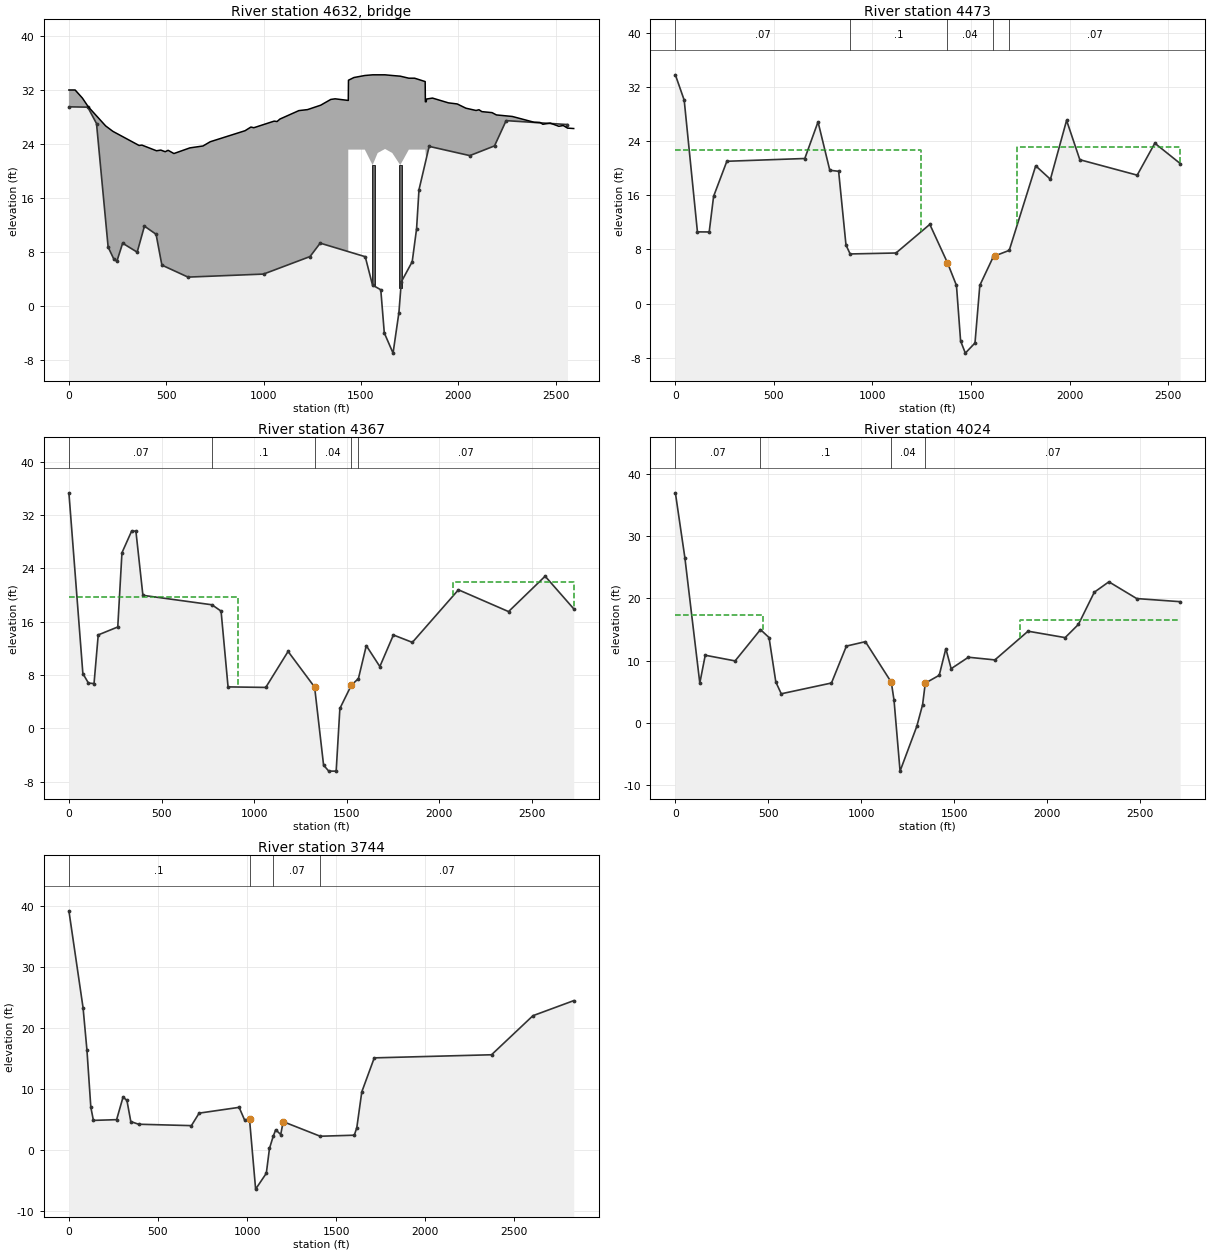
Type RM Length L Ch R = 3 ,4632    ,,,
BEGIN DESCRIPTION:
HWY 40  - Pulaski Hwy  CE050907PF-8  Geometry taken from Baltimore District's HEC-RAS model.  Top of road from LIDAR.
END DESCRIPTION:
Bridge Culvert--1,0,-1,-1, 0
Deck Dist Width WeirC Skew NumUp NumDn MinLoCord MaxHiCord MaxSubmerge Is_Ogee
57,100,2.6,0, 60, 60, , , 0.95, 0, 0,0,,
       0      32   69.31   99.15  188.69  225.99   360.3  375.22  449.83  472.22
   494.6  509.53  539.37  621.45   688.6   725.9  904.98  934.82  949.75  1054.2
 1069.13 1084.05 1181.05 1225.81 1292.97  1345.2 1367.58    1435    1436    1464
    1520    1560    1586    1624    1661    1702    1746 1775.72    1830    1831
    1835 1837.64 1867.49 1949.56 1994.33  2039.1 2091.33 2106.25 2121.17  2173.4
 2195.79 2277.86 2389.78 2419.63 2434.55 2471.86 2516.63 2539.01  2561.4 2592.93
   32.02   32.02   30.82   29.54   26.69   25.88   23.79   23.84      23    23.1
   22.86   23.07   22.59   23.43   23.71   24.34   25.98   26.52   26.42    27.4
   27.34   27.71   28.96   29.11   29.76   30.62   30.71   30.47   33.47   33.87
   34.17   34.27   34.27   34.27   34.17   34.07   33.77   33.77   33.27   30.27
   30.27   30.68   30.82   30.11   29.95   29.32   28.98   29.09   28.81   28.66
   28.32   28.09   27.23    27.2   26.93   27.11   26.63   26.75   26.36    26.3
                                                                                
                                                                                
                                                           23.17   23.17   23.17
   23.17   20.87   22.67   23.27   22.67   20.87   23.17   23.17   23.17   23.17
   20.37
                                                                                
    -111  -73.69  -43.85   45.69   82.99   217.3  232.22  306.83  329.22   351.6
  366.53  396.37  478.45   545.6   582.9  761.98  791.82  806.75   911.2  926.13
  941.05  963.43  978.36 1038.05 1052.97 1149.97  1202.2 1232.04  1239.5    1289
    1290    1369    1414    1445    1492    1520    1553    1595    1679    1680
    1684 1687.18 1724.49 1806.56 1851.33  1896.1 1948.33 1963.25 1978.17  2030.4
 2052.79 2149.78 2246.78 2276.63 2291.55 2328.86 2373.63 2396.01  2418.4 2560.93
   32.02   30.82   29.54   26.69   25.88   23.79   23.84      23    23.1   22.86
   23.07   22.59   23.43   23.71   24.34   25.98   26.52   26.42    27.4   27.34
   27.71   27.86   28.22   28.96   28.88   29.76   30.62   30.72   30.57   30.17
   33.17   33.77   33.97   34.17   34.27   34.27   34.17   34.17   33.57   30.57
   30.57   30.77   30.82   30.11   29.95   29.32   28.98   29.09   28.81   28.66
   28.32      28   27.23    27.2   26.93   27.11   26.63   26.75   26.36    26.3
                                                                                
                                                                                
                                                                           23.17
   23.27   23.27   20.77   22.57   23.27   22.67   20.77   23.27   23.17   23.17
   23.17
                                                                                
Pier Skew, UpSta & Num, DnSta & Num=  ,1565, 2 ,1414, 2 , 0 , 0 , 0 ,,
   13.92   13.92
   -5.83   20.87
   13.92   13.92
   -5.83   20.85
Pier Skew, UpSta & Num, DnSta & Num=  ,1705, 2 ,1554, 2 , 0 , 0 , 0 ,,
   13.92   13.92
   -5.83   20.87
   13.92   13.92
   -5.83   20.77
BR Coef=-1 , 1 , 0 ,, 0 ,,,0.8,-1,0.5,0,
WSPro=,,,, 1 ,,,, 0 ,,,, 0 ,,,,-1 ,-1 ,-1 , 0 , 0 , 0 , 0 , 0
BR U #Sta/Elev= 30
       0   29.52      97   29.47  141.77   27.04  201.46     8.7  229.46       7
  246.22    6.58  276.07    9.28  350.68    7.95  387.99   11.81  447.68   10.61
  477.53    6.03  611.83    4.25  999.82     4.7 1238.58     7.3 1290.81    9.29
 1522.11    7.28 1559.42    3.07    1602    2.37    1620   -4.03    1665   -7.03
    1695   -1.03 1707.43    3.55 1763.41    6.54  1785.8   11.42 1798.18   17.21
 1850.41   23.65 2059.33   22.28 2186.17   23.72 2245.86   27.47 2560.93   26.89
BR U #Mann= 4
       0     .07  229.46      .1 1522.11     .04 1763.41      .1
BR U Banks=,1763.41
BC Design=,, 0 ,, 0 ,,,,,,
BC Use User HTab Curves=0
BC User HTab FreeFlow(D)= 0

Type RM Length L Ch R = 1 ,4473    ,70.16,106.24,162.14
BEGIN DESCRIPTION:
underwater portion from baltimore district hecras model section 1.06
END DESCRIPTION:
XS GIS Cut Line= 2
1642449.18696575706271.5565777871640046.60725734707158.085388452
#Sta/Elev= 30
       0   33.78   44.77   30.04  111.92   10.58  171.61   10.57  193.99   15.84
  261.15   21.01   656.6   21.42  723.75   26.83  783.44   19.68  828.21   19.53
  865.52    8.64  886.59    7.32  1119.2    7.46 1290.81   11.69 1380.35    6.02
    1426    2.67    1447   -5.53    1471   -7.33    1520   -5.83  1544.5    2.68
 1611.65    6.83 1619.11    7.01 1693.72    7.85 1828.03   20.34 1902.64   18.35
 1984.71   27.05 2051.86   21.24 2342.86   18.96  2432.4   23.68 2560.93   20.68
#Mann= 5 ,-1 , 0
       0     .07       0  886.59      .1       0 1380.35     .04       0
 1611.65     .09       0 1693.72     .07       0
#XS Ineff= 2 ,-1
       0    1245    22.7    1734 2560.93   23.17
Permanent Ineff=
       F       F
Bank Sta=1380.35,1619.11
XS Rating Curve= 0 ,0
Exp/Cntr=0.5,0.3

Type RM Length L Ch R = 1 ,4367    ,323.13,343.68,335.15
BEGIN DESCRIPTION:
underwater portion from baltimore district hecras model xsec 1.02
END DESCRIPTION:
XS GIS Cut Line= 4
1642399.74825855706200.8512772171641161.30865474706695.360403627
 1640980.2614965706660.6917988661639824.64133741707011.229913786
#Sta/Elev= 30
       0   35.33   75.37    8.21  105.52    6.78  135.67    6.71  158.29   14.01
  263.81    15.2  286.42   26.34  339.18   29.62   361.8   29.57  399.48   19.95
   772.4   18.53  821.58   17.58  859.27    6.21 1062.78    6.13 1183.37   11.53
 1326.58    6.18    1375   -5.53    1403   -6.43    1443   -6.43    1463    2.97
 1525.17    6.48 1563.06    7.45 1605.63    12.4 1678.78    9.26 1751.93      14
 1854.34   12.89 2103.05   20.78  2373.7   17.51  2571.2   22.82 2725.47   17.93
#Mann= 5 ,-1 , 0
       0     .07       0   772.4      .1       0 1326.58     .04       0
 1525.17     .09       0 1563.06     .07       0
#XS Ineff= 2 ,-1
 -145.73  913.6819.62698    2074    3000      22
Permanent Ineff=
       F       F
Bank Sta=1326.58,1525.17
XS Rating Curve= 0 ,0
Exp/Cntr=0.3,0.1

Type RM Length L Ch R = 1 ,4024    ,329.67,279.54,255.69
BEGIN DESCRIPTION:
underwater portion from baltimore hecras model xsec 0.92
END DESCRIPTION:
XS GIS Cut Line= 4
1642380.48792258706070.8440093251641301.90910742 706388.63955307
1641061.15490761706316.4132931231639746.63697666706566.797660932
#Sta/Elev= 30
       0   36.96   51.08   26.54  131.36    6.41  160.55   10.88  321.09    9.97
  457.57      15  503.53   13.72  540.02    6.59  569.21    4.69  839.22    6.42
  919.49   12.35 1021.65   13.06 1160.96    6.54 1175.58    3.65    1208   -7.73
    1298    -.53 1329.05    2.93 1343.67     6.4 1418.53    7.66 1454.16   11.94
 1482.67    8.72  1575.3   10.56 1717.82   10.13 1895.97   14.74 2095.49   13.71
 2166.75   15.83 2252.26      21 2330.64   22.67 2480.28   19.98 2713.92   19.48
#Mann= 4 ,-1 , 0
       0     .07       0  457.57      .1       0 1160.96     .04       0
 1343.67     .07       0
#XS Ineff= 2 ,-1
       0  469.1817.32508 1852.38 2713.9216.59948
Permanent Ineff=
       F       F
Bank Sta=1160.96,1343.67
XS Rating Curve= 0 ,0
Exp/Cntr=0.3,0.1

Type RM Length L Ch R = 1 ,3744    ,4707.57,4392.22,3862.93
BEGIN DESCRIPTION:
underwater portion from baltimore district hec ras model xsec 0.88
END DESCRIPTION:
XS GIS Cut Line= 4
1642260.11082265705830.0898095221641306.72419143706080.474177316
1639843.16750668706112.7924637351639620.34005634706425.131997779
#Sta/Elev= 30
       0   39.24   79.61    23.3  101.32   16.35  123.04       7  137.51    4.85
  267.78    4.97  303.97    8.68  325.68    8.12  347.39    4.66  390.82    4.22
  687.55    3.99  730.97    6.04  955.33    6.99  985.72    4.94 1013.72    5.03
    1048   -6.43    1108   -3.83 1125.75     .25 1146.76    2.24 1160.76    3.31
 1188.77    2.53 1202.77    4.64 1410.42    2.25 1601.87    2.42 1615.87    3.65
 1643.88    9.53 1713.89   15.11 2372.05   15.62 2604.41   22.03 2833.31    24.5
#Mann= 4 ,-1 , 0
       0      .1       0 1013.72     .04       0 1146.76     .07       0
 1410.42     .07       0
Bank Sta=1013.72,1202.77
XS Rating Curve= 0 ,0
Exp/Cntr=0.3,0.1
Stream Node=BigElkCreek     ,One             , 0 , 0 ,Upstream end
Stream Node=BigElkCreek     ,One             , 0 , 1 ,Downstream end

Chan Stop Cuts=-1
Use User Specified Reach Order=0
User Specified Reach Order=BigElkCreek     ,One