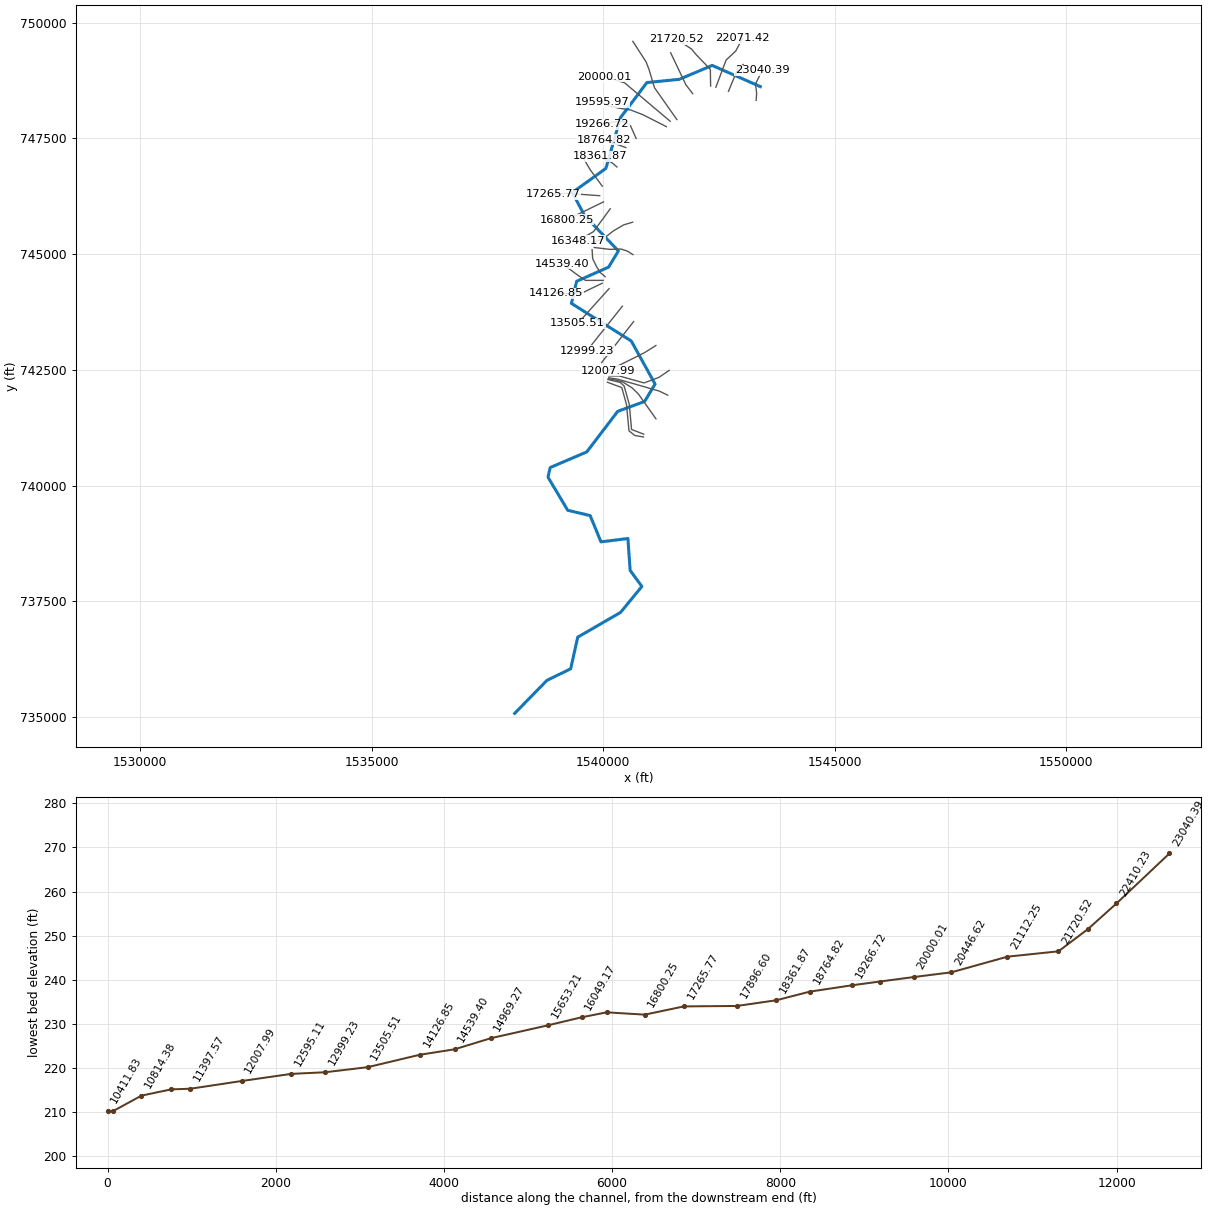
--- Conowingo_Creek.prj (project) ---

Proj Title=Conowingo_Creek
Current Plan=p01
Default Exp/Contr=0.3,0.1
English Units
Geom File=g01
Flow File=f01
Plan File=p01
Y Axis Title=Elevation
X Axis Title(PF)=Main Channel Distance
X Axis Title(XS)=Station
BEGIN DESCRIPTION:
Conowingo Creek - Georeferenced HEC-RAS model.  This was formerly an approximate method stream.  Projection:  MD Stateplane.  Horizontal datum:  NAD83.  Vertrial datum: NAVD88.  Units:Feet.  Created by: Aaron W. Buesing, USACE- St Paul District as part of FEMA Map Modernization study for Cecil County, MD.
END DESCRIPTION:
DSS Export Rating Curves= 0
DSS Export Rating Curve Sorted= 0
DSS Export Volume Flow Curves= 0
DXF OffsetX= 0
DXF OffsetY= 0
DXF ScaleX= 1
DXF ScaleY= 10

--- Conowingo_Creek.p01 (plan) ---

Plan Title=Conowingo_100yr
Program Version=4.00
Short Identifier=Conowingo100
Geom File=g01
Flow File=f01
Subcritical Flow
K Sum by GR= 0
Std Step Tol= 0.01
Critical Tol= 0.01
Num of Std Step Trials= 20
Max Error Tol= 0.3
Flow Tol Ratio= 0.001
Split Flow NTrial= 30
Split Flow Tol= 0.02
Split Flow Ratio= 0.02
Log Output Level= 0
Friction Slope Method= 1
Unsteady Friction Slope Method= 2
Unsteady Bridges Friction Slope Method= 1
Parabolic Critical Depth
Global Vel Dist= 0 , 0 , 0
Global Log Level= 0
CheckData=True
Encroach Param=-1 ,0,0, 0
Computation Interval=1HOUR
Output Interval=1HOUR
Run HTab= 0
Run UNet= 0
Run PostProcess= 0
Run WQNet= 0
UNET Theta= 1
UNET Theta Warmup= 1
UNET ZTol= 0.02
UNET ZSATol= 0.05
UNET MxIter= 20
UNET MaxInSteps= 0
UNET DtIC= 0
UNET DtMin= 0
UNET MaxCRTS= 20
UNET WFStab= 2
UNET SFStab= 1
UNET WFX= 1
UNET SFX= 1
UNET DSS MLevel= 4
UNET DZMax Abort= 100
UNET Convert EG Bridges= 0
UNET Use Existing IB Tables=-1
UNET Froude Reduction=False
UNET Froude Limit= 1
UNET Froude Power= 10
UNET Time Slicing=0,0, 5
Instantaneous Interval=1HOUR
Write IC File= 0
Echo Input=False
Echo Output=False
Write Detailed= 0
Detailed Automatic Start=False, 10
WQ ULTIMATE=-1
WQ Max Comp Step=1HOUR
WQ Output Interval=15MIN
WQ Output Selected Increments= 0
WQ Output face flow=0
WQ Output face velocity=0
WQ Output face area=0
WQ Output face dispersion=0
WQ Output cell volume=0
WQ Output cell surface area=0
WQ Output cell continuity=0
WQ Output face conc=0
WQ Output face dconc_dx=0
WQ Output face courant=0
WQ Output face peclet=0
WQ Output face adv mass=0
WQ Output face disp mass=0
WQ Output cell mass=0
WQ Output cell source sink temp=0
WQ Output cell source sink nsm=0
WQ Output MaxMinRange=-1
WQ Create Restart=0
WQ Fixed Restart=0
Sorting and Armoring Iterations= 10
XS Update Threshold= 0.02
Hydraulics Update Threshold= 0.02
Energy Slope Method= 0
Volume Change Method= 0
XS Weighting Method= 0
Number of US Weighted Cross Sections= 1
Number of DS Weighted Cross Sections= 1
Upstream XS Weight=0.25
Main XS Weight=0.5
Downstream XS Weight=0.25
Number of DS XS's Weighted with US Boundary= 1
Upstream Boundary Weight= 1
Weight of XSs Associated with US Boundary= 0
Number of US XS's Weighted with DS Boundary= 1
Downstream Boundary Weight= 0.5
Weight of XSs Associated with DS Boundary= 0.5
Sediment Output Level= 4
Mass or Volume Output= 0
Output Increment Type= 1
Profile and TS Output Increment= 10
XS Output Flag= 0
XS Output Increment= 10
Disregard all LS=0
Disregard all Conn=0
Disregard all Breaches=0
Disregard all Pumps=0

--- Conowingo_Creek.f01 (steady flow) ---

Flow Title=ConowingoCreek_100yr
Program Version=4.00
Number of Profiles= 2
Profile Names=100CUR,100ULT
River Rch & RM=Conowingo_Creek,Reach1          ,23040.39
     780     780
River Rch & RM=Conowingo_Creek,Reach1          ,21720.52
   13600   13700
Boundary for River Rch & Prof#=Conowingo_Creek,Reach1          , 1
Up Type= 0
Dn Type= 3
Dn Slope=0.0001
Boundary for River Rch & Prof#=Conowingo_Creek,Reach1          , 2
Up Type= 0
Dn Type= 3
Dn Slope=0.0001
DSS Import GetInterval= 0
DSS Import GetPeak= 0
DSS Import FillOption= 0

--- Conowingo_Creek.g01 (geometry) ---

Geom Title=ConowingoCreek
Program Version=4.00

River Reach=Conowingo_Creek ,Reach1
Reach XY= 30
1543392.49880803748619.1611349581542353.33395162 749076.18540442
1541641.46458121748775.9004696311540942.57083102748706.100581646
1540374.32815316747950.829998836 1540056.3508857746850.736037776
 1539333.1687969746331.1489919421539594.59778057745836.549631178
1540327.19831429745069.3474435811540117.20207009744720.944583908
1539425.16899262 744413.109180481539313.01190768743935.844989136
1540605.20470576743124.4958638251541119.45687191742193.830690712
1540893.94954152741817.9851400111540312.88038856741604.409414396
 1539643.5173602740727.4364627751538854.83828397740390.965207875
1538805.91870433740183.3552846611539233.07015564739467.458997622
1539717.49330983739352.9155916871539951.35276358738784.971203998
1540532.42191659738857.7539931681540581.34149617738168.107236683
1540834.29151759737822.0906979441540373.73157294737261.305273131
1539449.03220221736726.7693788111539296.30766095736043.088424712
1538785.33060914735794.6742909551538086.75358754735080.652715579

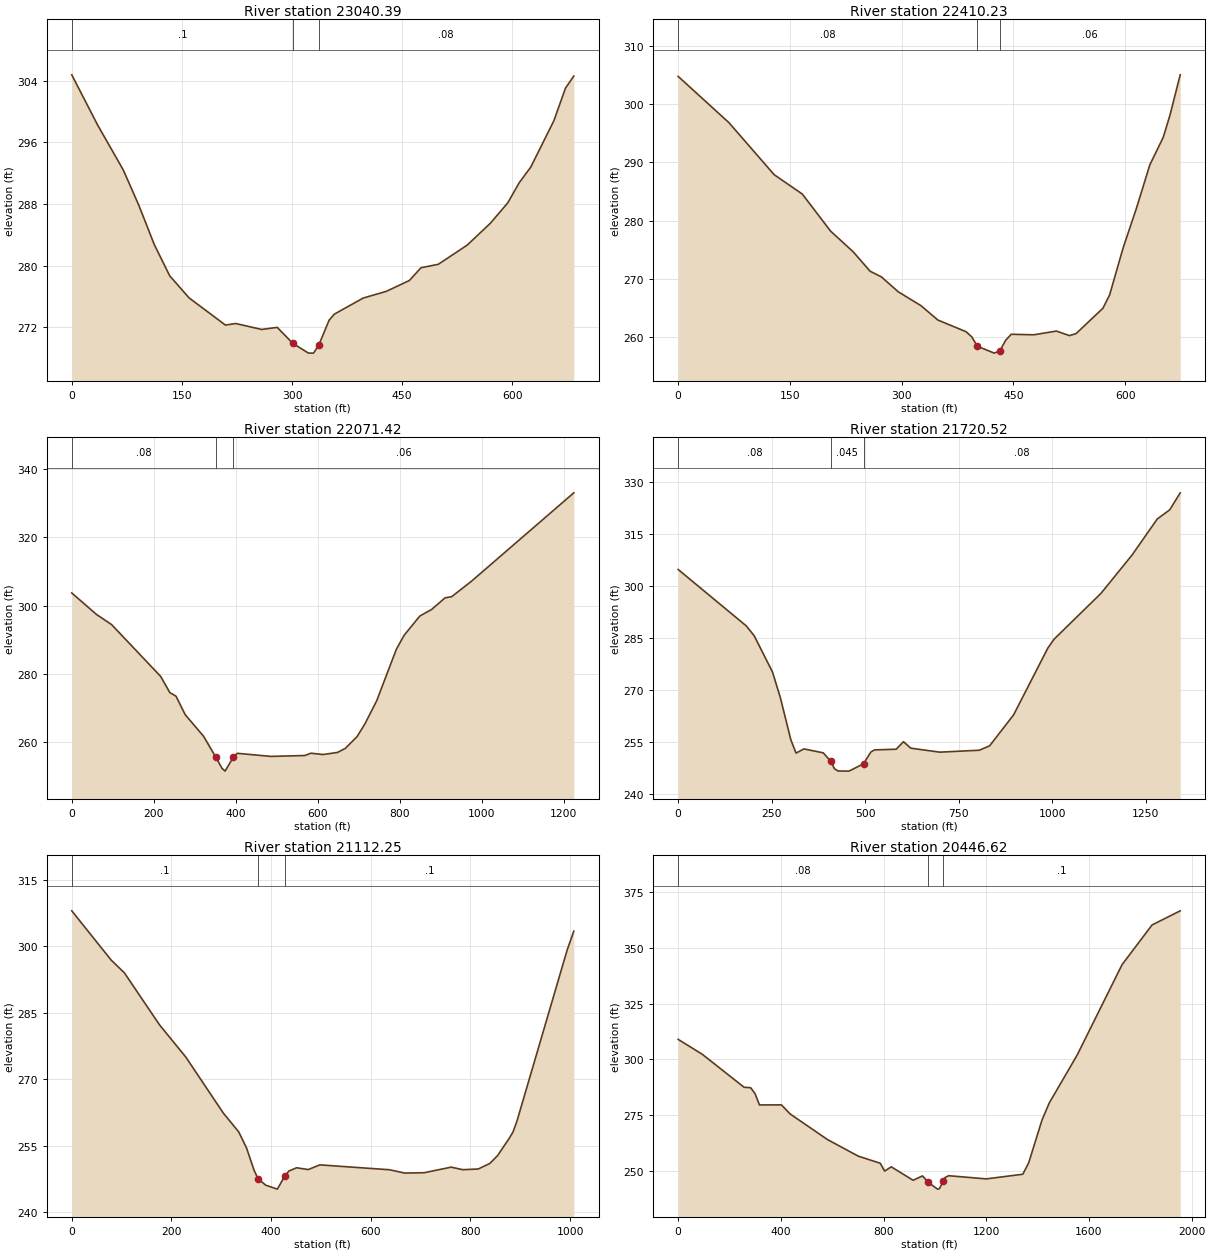
Type RM Length L Ch R = 1 ,23040.39,588.53,630.16,531.58
XS GIS Cut Line= 5
1543302.01271851748322.6611345561543314.19313687 748474.91636394
1543287.80223042748677.9233364161543435.99732035748966.193237334
1543435.99732035748968.223307043
#Sta/Elev= 30
       0  304.74   35.11  298.25   70.22  292.39   91.29  287.83  112.36  282.73
  133.42  278.67   159.8  275.81  209.21  272.29  223.33  272.49  258.63  271.72
   279.8  271.99  300.98  269.92  322.16  268.66  329.21  268.65  336.27  269.67
  350.39  272.91  357.46   273.7  396.81  275.79  428.29  276.66  459.78  278.07
  475.52  279.72  499.13  280.17  538.49  282.66  569.97  285.49  593.58  288.12
  609.32  290.75  625.07  292.78  656.55   298.8  672.29  303.01  683.62  304.58
#Mann= 3 , 0 , 0
       0      .1       0  300.98    .045       0  336.27     .08       0
Bank Sta=300.98,336.27
XS Rating Curve= 0 ,0
Exp/Cntr=0.3,0.1

Type RM Length L Ch R = 1 ,22410.23,325.02,338.81,301.88
XS GIS Cut Line= 3
1542705.17221941748517.5478281381542906.14912215749002.734492362
1543021.86309648749096.117699713
#Sta/Elev= 30
       0  304.71   68.19  296.78  128.81  287.88  166.69  284.55  204.57  278.21
  234.88  274.67  257.61  271.34  272.76  270.37  295.49  267.81   325.8  265.45
  348.53  262.98  386.42  260.98  393.99  260.11  401.57  258.49   424.3  257.31
  431.88  257.71  439.45  259.49  447.03  260.54  477.34  260.45  507.64  261.09
  525.16  260.31  534.16  260.66  570.14     265  579.14  267.29  597.13  275.29
  615.12  282.13  633.11  289.57   651.1  294.28  660.09  298.06  673.86  304.98
#Mann= 3 , 0 , 0
       0     .08       0  401.57    .045       0  431.88     .06       0
Bank Sta=401.57,431.88
XS Rating Curve= 0 ,0
Exp/Cntr=0.3,0.1

Type RM Length L Ch R = 1 ,22071.42,246.04,350.9,463.45
XS GIS Cut Line= 4
1542432.69814064748604.562795922 1542654.2169821749193.386382908
1542860.32844861749385.4766612351543009.70291314749661.474703804
#Sta/Elev= 30
       0  303.69   59.83  297.45   97.23  294.42  216.89  279.25  239.33   274.5
  254.29  273.47  276.72  268.05   321.6  261.71  351.51  255.57  366.47  252.34
  373.95  251.51   394.1  255.58  403.86  256.73  486.13  255.82   568.4  256.08
  583.36  256.76  613.28  256.37  648.25  256.99  667.39  258.17  696.09  261.63
  715.23  265.37  743.94  272.14  791.78  287.19  810.92  291.33  849.19  296.94
   877.9  298.86  910.86  302.28  926.78   302.6  974.54  307.07 1224.69  333.02
#Mann= 3 , 0 , 0
       0     .08       0  351.51    .045       0   394.1     .06       0
Bank Sta=351.51,394.1
XS Rating Curve= 0 ,0
Exp/Cntr=0.3,0.1

Type RM Length L Ch R = 1 ,21720.52,614.64,608.26,562.77
XS GIS Cut Line= 5
1542319.45897172748631.2317327411542313.36876252748990.554074034
1542010.88837355749305.2148813611541903.29467811749433.109274015
1541585.83360976 749639.65295203
#Sta/Elev= 30
       0  304.72  182.03  288.42  203.03   285.6  252.04  275.12  273.04  267.71
  301.04  255.54  315.05  251.68  336.05  252.89  387.75  251.75  407.92  249.29
  417.63  247.17  427.34  246.51  456.47  246.47  495.31  248.59  514.73  251.96
  524.44   252.6   582.7   252.8  602.12  254.98  621.54   253.1  699.22  251.95
  804.99  252.51  832.43  253.79  896.47  262.73  988.03  282.04 1004.73   284.6
    1130  297.83 1213.51  308.97 1280.32  319.31 1313.72  321.96 1341.71  326.87
#Mann= 3 , 0 , 0
       0     .08       0  407.92    .045       0  495.31     .08       0
Bank Sta=407.92,495.31
XS Rating Curve= 0 ,0
Exp/Cntr=0.3,0.1

Type RM Length L Ch R = 1 ,21112.25,653.31,665.63,641.55
XS GIS Cut Line= 3
1541931.71709916748466.8075535451541785.04055166748659.116804674
1541455.83318956749350.126317203
#Sta/Elev= 30
       0  308.01   79.23  296.88  105.64  294.02  176.07   282.3   228.9  275.02
  303.89  262.43  334.91  258.17  350.41  254.61  365.92  249.48  373.68   247.6
  389.18  246.14  412.45  245.25  427.95  248.29  435.71  249.34  451.21  250.07
  474.48  249.66  497.74  250.72  637.31  249.62  668.32  248.87  707.09  248.95
  761.37  250.21  784.63  249.63  815.64  249.79   838.9  251.05  854.41  252.82
  877.67  256.69  885.43  258.17  893.18  260.57  993.98  299.18 1007.28  303.43
#Mann= 3 , 0 , 0
       0      .1       0  373.68    .045       0  427.95      .1       0
Bank Sta=373.68,427.95
XS Rating Curve= 0 ,0
Exp/Cntr=0.3,0.1

Type RM Length L Ch R = 1 ,20446.62,347.3,446.62,549.92
XS GIS Cut Line= 5
  1541590.463614747907.1325150131541106.56850639748595.951173529
1540986.34396391748996.1145036371540925.01576379 749153.84296833
1540639.31512654749596.009448484
#Sta/Elev= 30
       0  308.91    94.1   302.2  256.64  287.43   282.3  287.22  299.41  284.56
  316.52  279.49  402.07  279.52  436.29  275.42  581.71  263.94  701.48  256.51
  787.03  253.32  804.14   249.8   829.8  251.72  914.89  245.69  951.43  247.64
  973.36  244.85 1009.91  241.71 1017.22  241.89 1031.83  245.15 1039.14   246.9
 1053.76  247.73 1199.94   246.3 1342.25  248.39 1364.78  253.41 1417.35  272.83
 1445.53  280.43 1553.87  301.85 1728.89  342.45 1845.57  360.26  1955.3   366.6
#Mann= 3 , 0 , 0
       0     .08       0  973.36    .045       0 1031.83      .1       0
Bank Sta=973.36,1031.83
XS Rating Curve= 0 ,0
Exp/Cntr=0.3,0.1

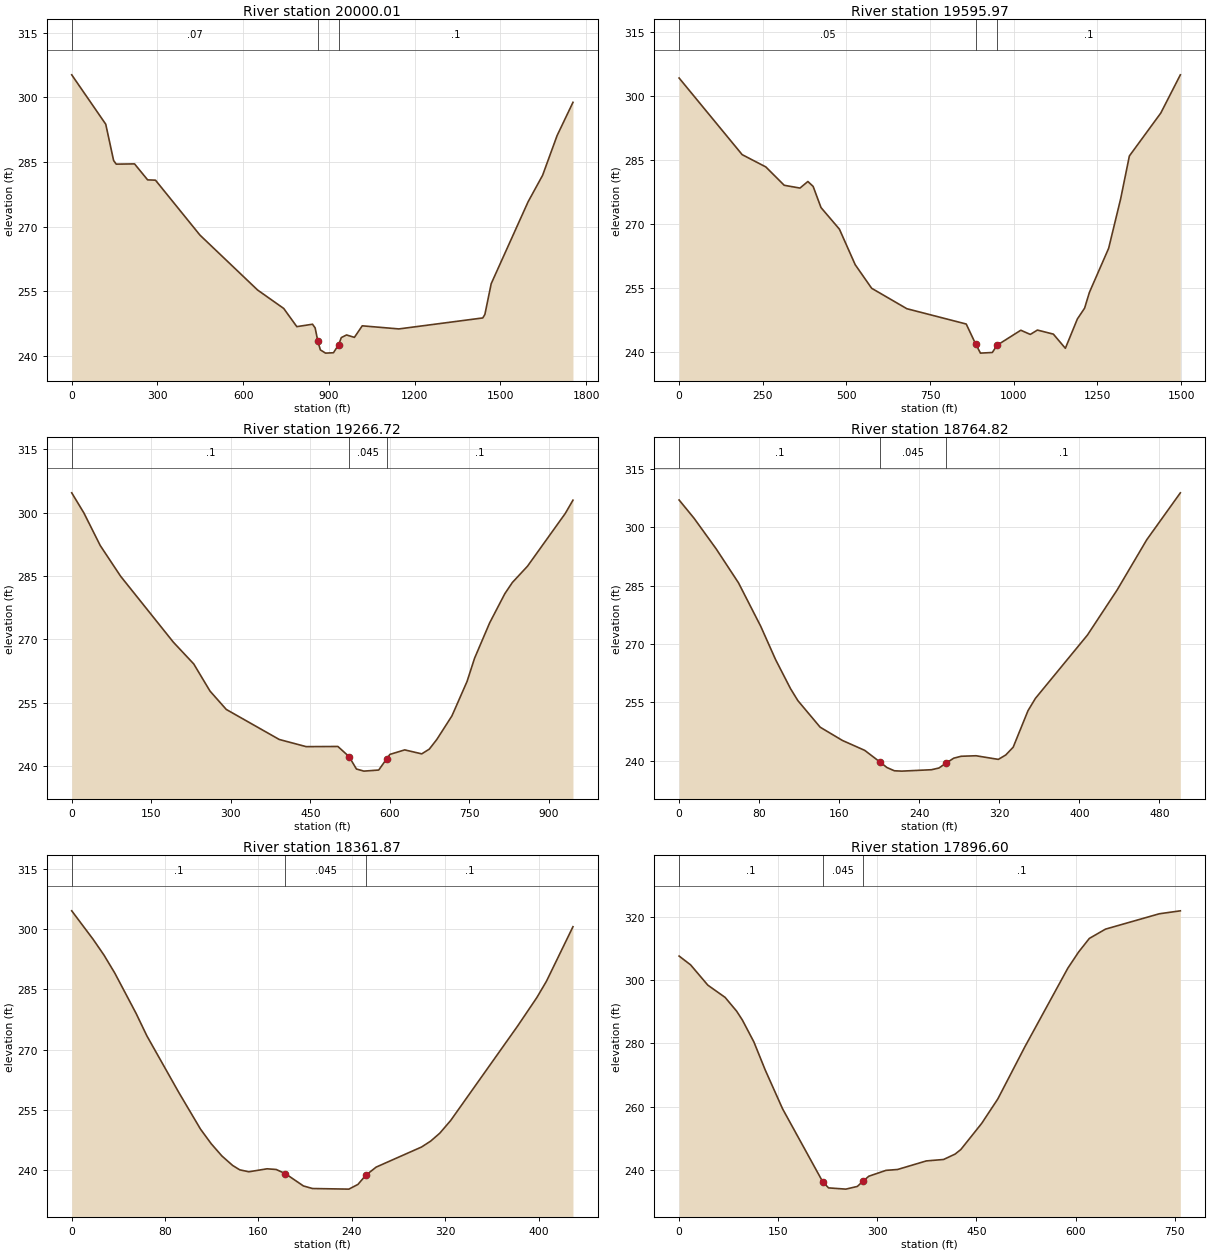
Type RM Length L Ch R = 1 ,20000.01,345.29,404.04,517.79
XS GIS Cut Line= 4
1541446.05475308747870.3229271621540464.95162444748698.230550677
1540187.89592363748789.4959579861540015.14354549748835.128661633
#Sta/Elev= 30
       0  305.26  119.07  293.79  146.55  285.37  155.71  284.52  219.82  284.58
  265.62  280.87   293.1   280.8   448.8  268.04  650.31   255.3   741.9  251.01
   787.7  246.79  842.65  247.35  851.81   246.5  861.27  243.42  870.13  241.39
  888.45  240.64  915.93  240.73  934.25  242.61  943.41  244.25  961.73  244.86
   989.2   244.3 1016.68  246.98 1144.91  246.26 1438.51  248.81 1445.88  249.63
 1467.99  256.77 1597.16  275.79 1647.85  281.93 1698.53  291.15 1754.12  298.87
#Mann= 3 , 0 , 0
       0     .07       0  861.27    .045       0  934.25      .1       0
Bank Sta=861.27,934.25
XS Rating Curve= 0 ,0
Exp/Cntr=0.3,0.1

Type RM Length L Ch R = 1 ,19595.97,302.83,329.25,304.95
XS GIS Cut Line= 6
1541363.29613133 747754.241611631540863.89897905748008.000327215
1540599.98991479748111.5338831841540336.08085057748154.165347412
1540122.92352949748202.8870207971539972.69836986748277.999600619
#Sta/Elev= 30
       0  304.17  188.44  286.19  259.11  283.31  314.07     279  361.19  278.35
  384.74  279.89  400.44  278.74     424  273.77  478.96  268.71  526.07  260.38
  575.21  254.84  680.48  250.04  857.84  246.45  886.21  241.73  900.39  239.62
  935.84  239.77  950.02  241.47 1020.93  244.99 1049.29  244.01 1070.57  245.03
 1118.17  244.08 1154.08  240.75 1189.98  247.64 1211.52  250.17 1225.88  253.87
 1283.33  264.21 1319.23  275.82  1345.3  285.88 1439.22  295.96 1497.61  304.92
#Mann= 3 , 0 , 0
       0     .05       0  886.21    .045       0  950.02      .1       0
Bank Sta=886.21,950.02
XS Rating Curve= 0 ,0
Exp/Cntr=0.3,0.1

Type RM Length L Ch R = 1 ,19266.72,507.02,501.9,464.3
XS GIS Cut Line= 5
1540711.64374964747498.4528263061540589.83956616 747770.48216942
1540461.94517353747857.7751675991540269.08854969747861.835307032
1539974.72843955747807.023424476
#Sta/Elev= 30
       0   304.7   23.01  299.92   53.69  292.23   92.04  284.97  191.74  269.31
  230.09  264.17  260.77  257.74  291.45  253.39  391.28  246.28  442.13  244.58
  501.91  244.62  522.91  242.23  536.92  239.28  550.92  238.78  578.93  239.04
  594.26  241.75  599.93  242.74  627.94  243.81  660.04  242.87  674.28  243.99
  688.52  246.29     717  251.87  745.48  260.02  759.72  265.54   788.2  273.92
  816.69   280.8  830.93  283.46  859.41  287.31  930.61   299.8  945.22  302.96
#Mann= 3 , 0 , 0
       0      .1       0  522.91    .045       0  594.26      .1       0
Bank Sta=522.91,594.26
XS Rating Curve= 0 ,0
Exp/Cntr=0.3,0.1

Type RM Length L Ch R = 1 ,18764.82,413.46,402.95,391.54
XS GIS Cut Line= 2
1540487.76797625747303.1736102551540015.14354549747469.407030731
#Sta/Elev= 30
       0  307.02   14.84  302.36    37.1  294.44   59.36  285.73   81.62  274.54
   96.46  265.99  111.31  258.56  118.73  255.45  140.99  248.63  163.25  245.22
  185.51  242.68  200.35  239.77  207.77  238.26  215.19  237.43  222.61  237.34
  252.29   237.7  259.71  238.14  267.13  239.45  274.55  240.67  281.97  241.16
  296.81  241.29  319.08  240.36   326.5  241.49  333.92  243.49  348.76  252.89
  356.18  256.05  408.12   272.3   437.8  283.89  467.48  296.82  501.01  308.86
#Mann= 3 , 0 , 0
       0      .1       0  200.35    .045       0  267.13      .1       0
Bank Sta=200.35,267.13
XS Rating Curve= 0 ,0
Exp/Cntr=0.3,0.1

Type RM Length L Ch R = 1 ,18361.87,486.72,465.27,414.25
XS GIS Cut Line= 4
1540295.47945608 746883.341699691540185.85569096746976.724907041
1540023.45011298747055.8976263111539934.12704505747110.709508881
#Sta/Elev= 30
       0  304.53   18.39  297.43   27.59  293.55   36.78  289.12   55.17  279.03
   64.37  273.47   91.95  259.29  110.35  250.28  119.54  246.64  128.74  243.59
  137.93  241.24  144.01  240.16  151.79  239.68  167.37  240.42  175.16  240.25
  182.94  239.24  198.52  236.16  206.31  235.52  237.46  235.37  245.24  236.54
  251.98  238.82  260.82  240.84  299.76  245.84  307.54   247.3  315.33  249.26
  324.68  252.42  382.17  275.95   398.6  283.01  406.81  287.06  429.48  300.58
#Mann= 3 , 0 , 0
       0      .1       0  182.94    .045       0  251.98      .1       0
Bank Sta=182.94,251.98
XS Rating Curve= 0 ,0
Exp/Cntr=0.3,0.1

Type RM Length L Ch R = 1 ,17896.60,484.44,630.82,704.08
XS GIS Cut Line= 3
1539979.28927836746468.7470290811539721.79045057746817.511264175
1539555.62310731747096.900292501
#Sta/Elev= 30
       0  307.55    17.4  304.77   43.51  298.37   69.61  294.52   87.01  290.19
   95.71   287.4  113.12   280.5  130.52  271.55  156.62  259.39  217.53  236.34
  226.23  234.48  252.33  234.09  269.74  234.94  278.44  236.61  287.14  238.16
  313.24  240.01  330.64  240.28  374.15  242.98  400.25  243.43  417.66  245.13
  426.36  246.57  457.96  254.82  482.39  262.53  523.11  278.88  588.27  303.71
  604.56  308.81  620.85   313.1  645.28  316.03  726.72  320.87  758.59   321.8
#Mann= 3 , 0 , 0
       0      .1       0  217.53    .045       0  278.44      .1       0
Bank Sta=217.53,278.44
XS Rating Curve= 0 ,0
Exp/Cntr=0.3,0.1

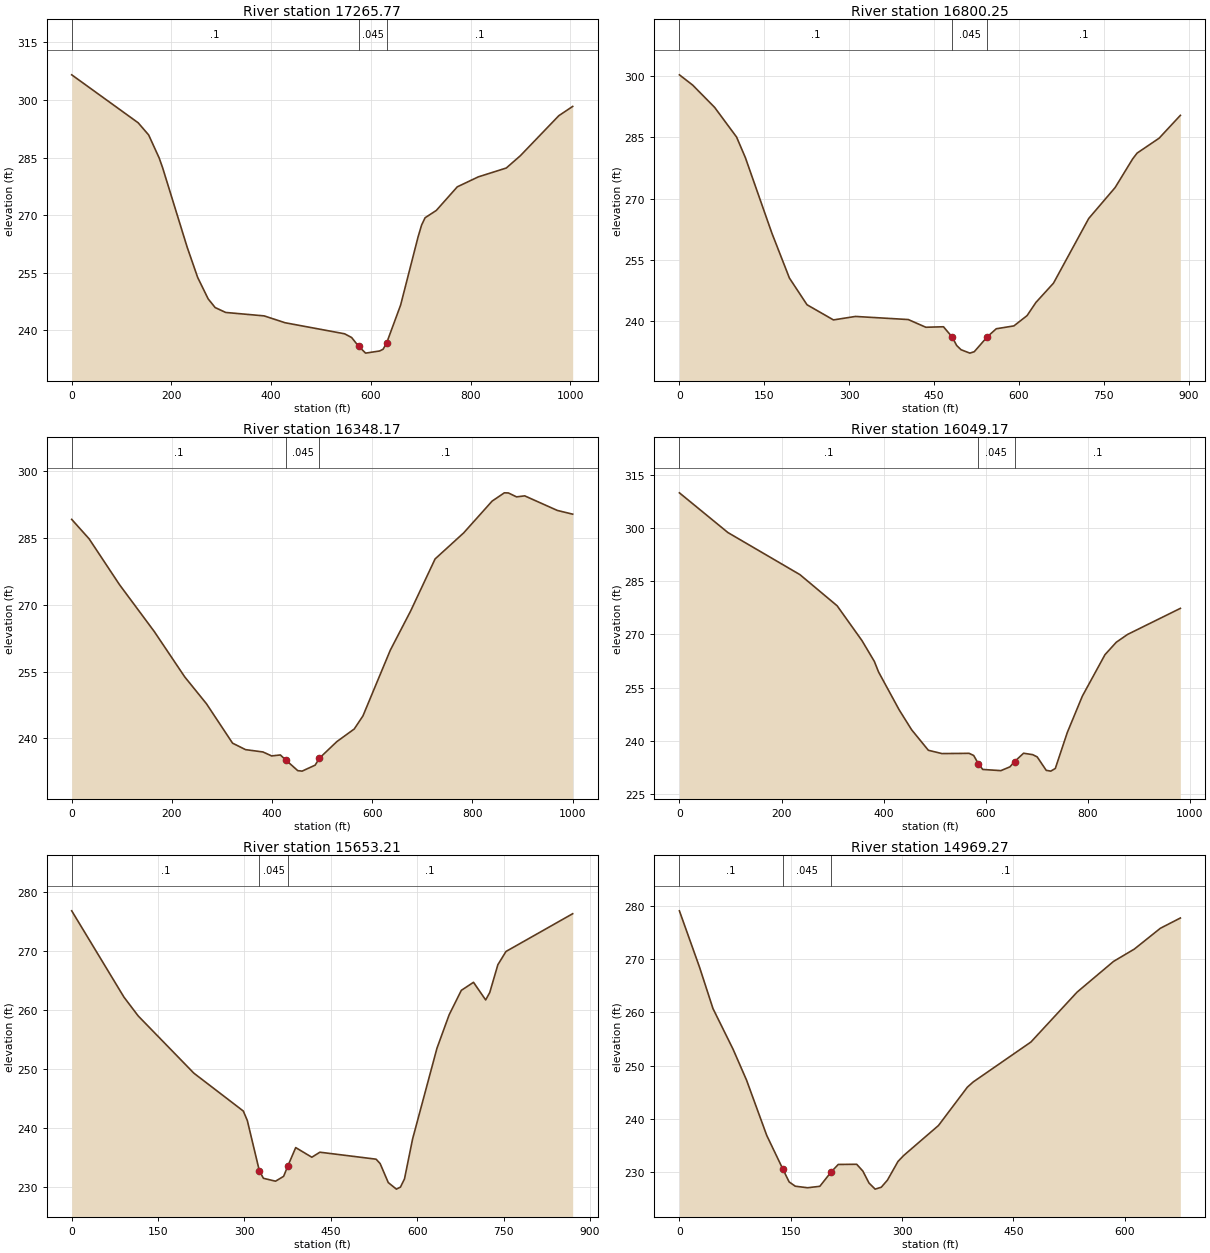
Type RM Length L Ch R = 1 ,17265.77,367.26,465.53,485.86
XS GIS Cut Line= 3
 1539922.5837664746262.8739581561539193.22274393746314.971174046
1538920.47849597746293.519379258
#Sta/Elev= 30
       0  306.56  133.34  294.05  154.39  290.87  175.45  284.87  182.46  282.28
  231.59  261.61  252.64  253.73   273.7  248.13  287.73  245.87  308.78   244.6
  385.98   243.7  428.09  241.91  547.39  239.03  561.43  238.06  575.46  235.77
   589.5  233.99  617.57  234.55  624.59  235.01   631.6  236.62  659.68  246.51
  694.76  264.32  701.78  267.39   708.8  269.29  731.22  271.19  773.35  277.35
  815.48  279.95  871.65  282.26  899.74  285.45  976.97   295.9  1004.8  298.32
#Mann= 3 , 0 , 0
       0      .1       0  575.46    .045       0   631.6      .1       0
Bank Sta=575.46,631.6
XS Rating Curve= 0 ,0
Exp/Cntr=0.3,0.1

Type RM Length L Ch R = 1 ,16800.25,395.04,452.08,487.7
XS GIS Cut Line= 2
1540005.32640345746128.0341052561539208.54545447745741.901799202
#Sta/Elev= 30
       0  300.32   23.34  297.82   62.23  292.35  101.12  285.06  116.68     280
  163.35  261.56  194.47  250.51  225.58  243.97  272.25  240.26  311.15  241.11
  404.49  240.35  435.61  238.46  466.72  238.58  482.28  236.03  490.06  233.99
  497.84  232.95  513.39  232.12  521.17  232.47  544.51  236.17  560.06  238.09
  591.18  238.79  614.52  241.32  630.07  244.53  661.19  249.27  723.42  265.11
  770.09  272.69   801.2  279.74  808.98  281.14  847.88  284.79  885.42  290.39
#Mann= 3 , 0 , 0
       0      .1       0  482.28    .045       0  544.51      .1       0
Bank Sta=482.28,544.51
XS Rating Curve= 0 ,0
Exp/Cntr=0.3,0.1

Type RM Length L Ch R = 1 ,16348.17,327.58,299,273.24
XS GIS Cut Line= 3
1540151.34450562745979.9606721551539789.99209465745486.653729051
1539455.56525876 745288.95847781
#Sta/Elev= 30
       0  289.15   34.71  284.79   95.45  274.49  164.86  263.97   225.6   253.8
  268.99  247.77  321.05  238.93  347.08  237.47  381.79  236.95  399.15  236.06
   416.5  236.28  428.29  235.05  451.21  232.76  459.89  232.65  485.92  233.99
  494.59  235.57   529.3  239.28  564.01  242.11  581.37  245.05  635.89  259.78
  676.55  268.59  725.34  280.27  782.26   286.1  839.18  293.25  863.58  295.11
  871.71  295.08  887.97   294.2  904.23  294.43  969.29  291.16  999.99  290.32
#Mann= 3 , 0 , 0
       0      .1       0  428.29    .045       0  494.59      .1       0
Bank Sta=428.29,494.59
XS Rating Curve= 0 ,0
Exp/Cntr=0.3,0.1

Type RM Length L Ch R = 1 ,16049.17,431.53,395.95,302.24
XS GIS Cut Line= 5
1540637.28295256745690.9150072191540442.15745649745632.577832803
1540219.84435123745502.8675145211539996.13277708 745328.18861419
1539772.42120297745251.575061411
#Sta/Elev= 30
       0  309.88   94.98   298.7  236.08  286.85  309.02  278.07  357.64  268.27
  381.96  262.39  390.06  259.46  430.58  248.76  454.89  243.17  487.69  237.39
  514.33  236.46  567.62  236.53   576.5  235.92  585.38  233.66  594.26  231.99
  629.79  231.66  647.55  232.73  656.43  234.19  674.19  236.56  691.96  236.16
  700.84  235.53   718.6  231.74  727.48  231.52  736.36  232.26  759.67  242.33
  789.27  252.62  833.67  264.31  855.86  267.82  878.06  270.02  981.34  277.35
#Mann= 3 , 0 , 0
       0      .1       0  585.38    .045       0  656.43      .1       0
Bank Sta=585.38,656.43
XS Rating Curve= 0 ,0
Exp/Cntr=0.3,0.1

Type RM Length L Ch R = 1 ,15653.21,715.63,683.95,522.86
XS GIS Cut Line= 5
1540642.62137902 744989.28664647 1540518.7871258745066.429296017
1540380.74238454745111.0908299541540143.22422673745102.970551044
1539804.20258269745143.571945563
#Sta/Elev= 30
       0  276.75   90.72  262.17  115.46  258.99  212.11  249.32  297.99  242.92
  304.99  241.32  326.01  232.78  333.01  231.55  354.02  231.06  368.03  231.88
  375.04  233.55  389.04  236.74  417.06  235.11  431.07  235.96  528.64  234.78
  535.69  234.04  549.79  230.83  563.89  229.72  570.94  230.06  577.99  231.45
  592.09  238.21  634.39  253.53  655.54  259.18  676.69  263.31  697.84  264.67
  718.99  261.69  726.04  262.94  740.15  267.64  754.25  269.88  870.09  276.26
#Mann= 3 , 0 , 0
       0      .1       0  326.01    .045       0  375.04      .1       0
Bank Sta=326.01,375.04
XS Rating Curve= 0 ,0
Exp/Cntr=0.3,0.1

Type RM Length L Ch R = 1 ,14969.27,391.16,429.87,445.82
XS GIS Cut Line= 5
 1540041.7207405 744514.250330881539940.21725427744597.483189568
1539852.92425607744735.5279308561539771.72146708744901.993648306
1539759.54104878745096.880341887
#Sta/Elev= 30
       0   279.1   27.16  268.49   45.26  260.72   72.42  253.05   90.52  247.26
  117.68  236.88  139.55  230.51  147.83  228.14  156.11  227.33  172.68  227.04
  189.24  227.31  204.55  230.02  214.09  231.42  238.93  231.45  247.22  230.17
   255.5  227.93  263.78  226.78  272.06  227.14  280.34  228.47  294.59  231.99
  302.38  233.12  349.11  238.74  388.06  245.95  395.84  246.92  473.73  254.44
  535.92  263.82  585.02  269.59  613.07  271.91  648.14  275.82  675.08  277.75
#Mann= 3 , 0 , 0
       0      .1       0  139.55    .045       0  204.55      .1       0
Bank Sta=139.55,204.55
XS Rating Curve= 0 ,0
Exp/Cntr=0.3,0.1

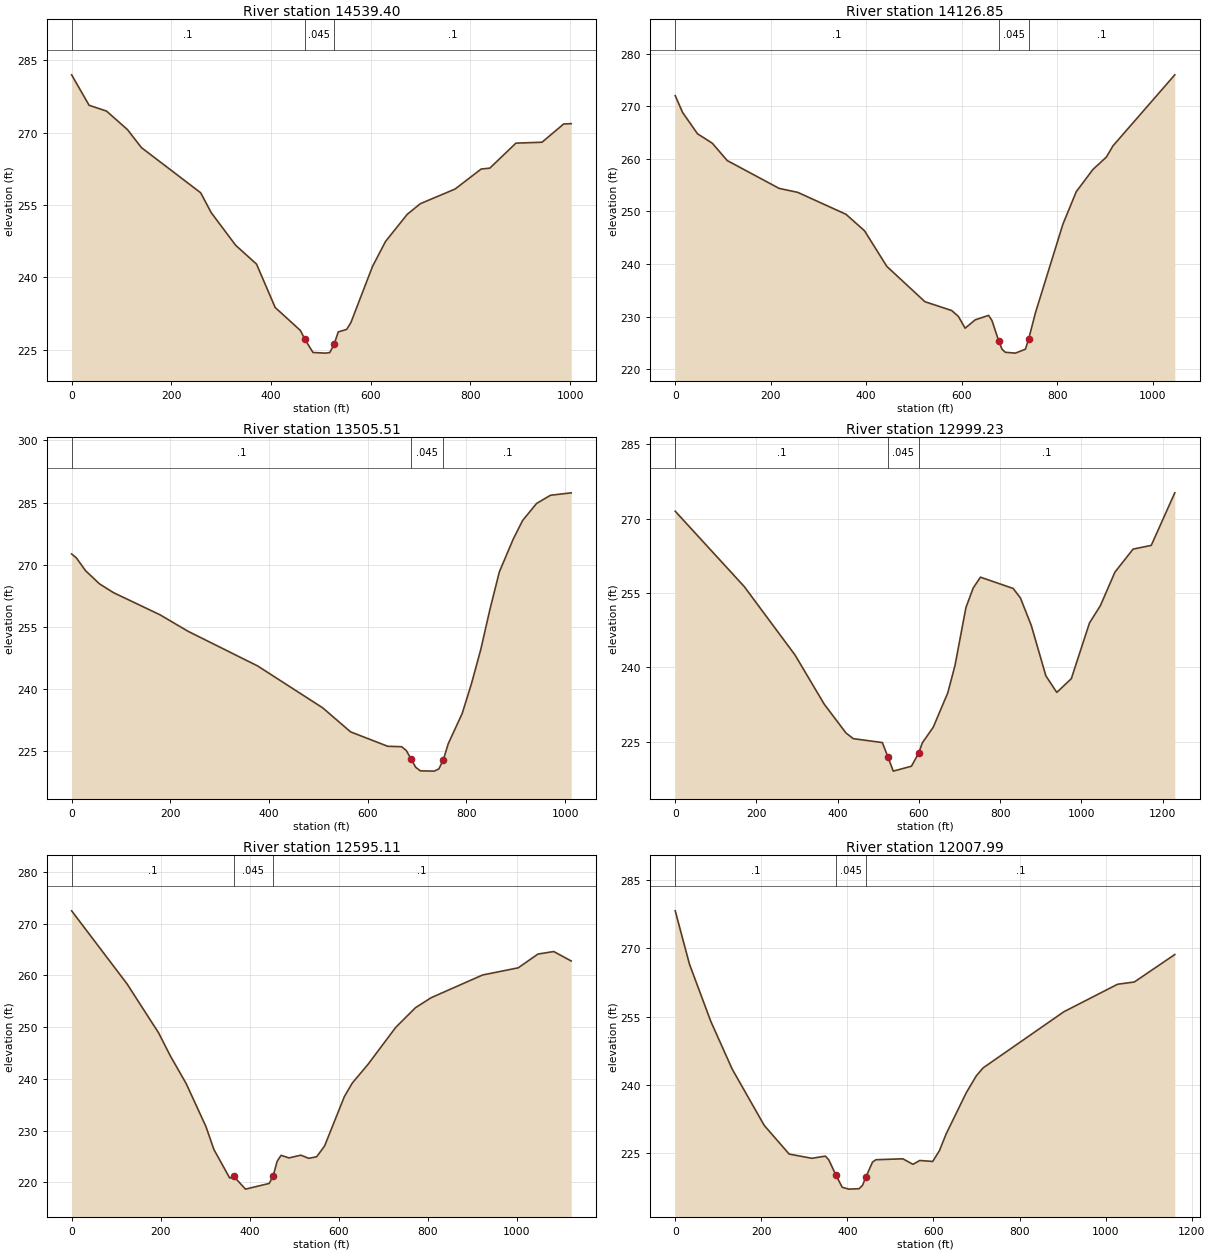
Type RM Length L Ch R = 1 ,14539.40,332.53,412.55,448.4
XS GIS Cut Line= 4
1539999.19731921744433.3423176561539616.12955526744433.342317656
1539447.57973914744546.7303757821539113.54464902744794.958286807
#Sta/Elev= 30
       0  281.99      35  275.68      70  274.47     112  270.63     140   266.9
     259  257.52     280  253.42     329  246.65     371  242.73  408.38  233.74
     459  228.97  467.43  227.24  484.31   224.4  509.62  224.27  518.05  224.39
  526.49  226.06  534.93  228.67   551.8  229.19  560.24  230.58  603.65  242.24
  629.81  247.43  673.42  253.06  699.58  255.26  769.35   258.3  821.68  262.45
  839.12  262.64  891.45  267.82  943.78  268.01  987.38   271.8 1002.38  271.86
#Mann= 3 , 0 , 0
       0      .1       0  467.43    .045       0  526.49      .1       0
Bank Sta=467.43,526.49
XS Rating Curve= 0 ,0
Exp/Cntr=0.3,0.1

Type RM Length L Ch R = 1 ,14126.85,493.49,621.34,644.03
XS GIS Cut Line= 4
 1539977.4512955744371.4730276471539563.40119174744171.577292666
1539233.13675143744149.1710838381538977.80775243744152.481854394
#Sta/Elev= 30
       0  272.01   15.55   268.8   46.64  264.76   77.73  262.96  108.82  259.67
  217.65  254.37  256.51  253.62  357.56  249.45  396.43  246.31  443.07  239.54
  522.92  232.82  579.05  231.14  593.08  230.01  607.12  227.78  628.16  229.37
  656.23  230.22  663.24  229.26  677.28  225.41  684.29   223.8  691.31   223.2
  712.36  223.04  733.41  223.79  740.42  225.82  754.45  230.74   811.8  247.55
  839.81  253.74  874.81  257.98  902.81  260.32  916.81  262.47 1046.15  275.97
#Mann= 3 , 0 , 0
       0      .1       0  677.28    .045       0  740.42      .1       0
Bank Sta=677.28,740.42
XS Rating Curve= 0 ,0
Exp/Cntr=0.3,0.1

Type RM Length L Ch R = 1 ,13505.51,499.67,506.28,507.7
XS GIS Cut Line= 2
1540125.84061351744254.4829704021539448.33701058743502.315705106
#Sta/Elev= 30
       0   272.6    9.42  271.69   28.26  268.57   56.53  265.39   84.79  263.28
     179  257.94  235.52  253.98  376.84   245.6  508.73  235.49  565.26  229.69
  640.63  226.21  668.89  226.11  678.31  225.16  687.73  223.19  697.15  221.15
  706.57  220.29  734.84  220.22  744.26  220.77  753.26     223   763.1  226.82
  791.36  234.11   810.2  241.33  829.05  249.56  847.89  259.38  866.73   268.3
  894.99  276.24  913.83  280.68   942.1  284.79  970.36  286.77 1012.31  287.36
#Mann= 3 , 0 , 0
       0      .1       0  687.73    .045       0  753.26      .1       0
Bank Sta=687.73,753.26
XS Rating Curve= 0 ,0
Exp/Cntr=0.3,0.1

Type RM Length L Ch R = 1 ,12999.23,400.8,404.13,402.89
XS GIS Cut Line= 2
1540413.43397965743875.6340169311539647.44011021742913.302368715
#Sta/Elev= 30
       0  271.49  169.99  256.29  295.24  242.46  366.82  232.58   420.5  226.76
  438.39  225.62  509.97  224.83  523.35  222.01  536.81  219.07  581.54  220.06
  599.44   222.7  608.38  224.77  635.22  227.92  671.01  234.85   688.9  240.41
  715.75  252.06  733.64     256  751.53  258.19  832.05  255.91  849.95     254
  876.79  248.42  912.58  238.29  939.42  234.95   975.2  237.71 1019.94  248.95
 1046.78  252.44 1082.57   259.2  1127.3  263.85 1172.03   264.6 1229.97   275.2
#Mann= 3 , 0 , 0
       0      .1       0  523.35    .045       0  599.44      .1       0
Bank Sta=523.35,599.44
XS Rating Curve= 0 ,0
Exp/Cntr=0.3,0.1

Type RM Length L Ch R = 1 ,12595.11,603.7,587.12,517.99
XS GIS Cut Line= 2
1540656.78221253743543.7955175491539965.45200546742658.892852515
#Sta/Elev= 30
       0  272.45  124.36  258.36  195.43  248.89  222.07   244.4  257.61  239.06
  302.02  230.76  319.79  226.35  355.32  220.84   364.2  221.18  390.85   218.7
  444.15   219.8  453.03  221.26  461.91  224.07   470.8  225.23  488.56  224.73
  515.21  225.26  532.98  224.65  550.74  224.95  568.51  227.02  612.93  236.56
  630.69  239.17  666.22   242.8   728.4  249.93  772.82  253.74  808.35  255.68
  923.83  260.06 1003.78  261.44 1048.19   264.1 1083.72  264.59 1122.94  262.76
#Mann= 3 , 0 , 0
       0      .1       0   364.2    .045       0  453.03      .1       0
Bank Sta=364.2,453.03
XS Rating Curve= 0 ,0
Exp/Cntr=0.3,0.1

Type RM Length L Ch R = 1 ,12007.99,618.6,610.42,565.87
XS GIS Cut Line= 4
 1541137.1280251743026.5899210721540888.25981571742869.893853799
1540616.23047261 742733.879182221540112.01400933742484.677640319
#Sta/Elev= 30
       0  278.22   33.09  266.51   82.72  253.93  132.35  243.46   206.8  231.09
   264.7  224.79  317.57  223.86  348.87  224.34   356.7  223.54  372.81  220.28
     388  217.49  403.66  217.09  427.14  217.18  434.96   217.9  442.79  219.71
  458.44  223.04  466.27  223.55  528.88  223.75  552.36  222.54  568.01  223.38
  598.23  223.17  613.84  225.54  629.46  229.22  676.31  238.29  699.74     242
  715.35  243.72  902.75  256.04 1027.68  262.09 1066.73  262.59 1160.67  268.62
#Mann= 3 , 0 , 0
       0      .1       0  372.81    .045       0  442.79      .1       0
Bank Sta=372.81,442.79
XS Rating Curve= 0 ,0
Exp/Cntr=0.3,0.1

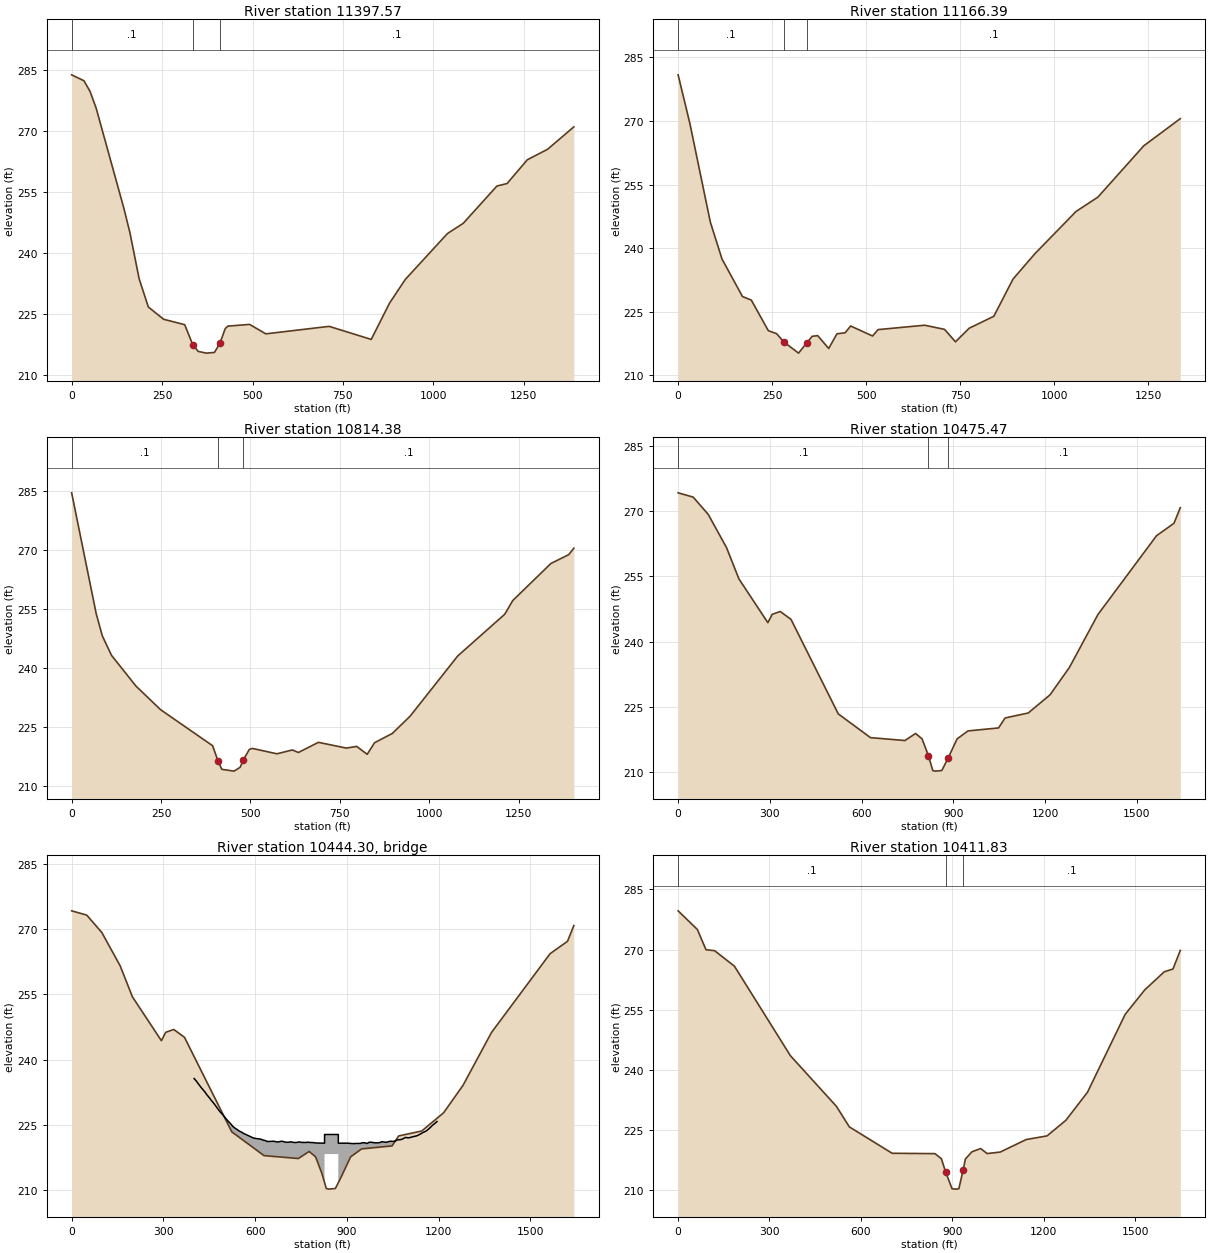
Type RM Length L Ch R = 1 ,11397.57,293.82,231.18,78.68
XS GIS Cut Line= 5
1541423.94465819742489.0638544861541202.92062309742338.015585884
1540882.16960657 742218.241472141540344.20112947742368.466631755
1540124.64533623742369.265243679
#Sta/Elev= 30
       0  283.75   33.91   282.3   50.87  279.68   67.83  275.53  144.13  251.02
  161.09  244.95  186.53  233.63  211.96  226.68  254.35  223.66  312.54  222.33
  334.96  217.36   349.9  215.76  372.32  215.34  394.73  215.51  409.68  217.74
  424.62  221.38  432.09  221.98  491.87   222.4   536.7  220.08  711.84  221.92
  828.13  218.71     879  227.67  922.61  233.49 1038.89  244.74  1082.5  247.25
 1175.64  256.42 1203.64  257.03 1259.64  262.87 1315.64  265.45  1388.2  270.96
#Mann= 3 , 0 , 0
       0      .1       0  334.96    .045       0  409.68      .1       0
Bank Sta=334.96,409.68
XS Rating Curve= 0 ,0
Exp/Cntr=0.3,0.1

Type RM Length L Ch R = 1 ,11166.39,408.88,352,176.56
XS GIS Cut Line= 5
 1541394.1282739741952.9495468881541211.04090197742041.625406072
1540754.27521387742173.579938173 1540305.6298047742301.474330857
1540118.49292322 742328.99490425
#Sta/Elev= 30
       0   280.9   31.11  269.48   85.56  246.15  116.67   237.4  171.11  228.55
  194.45  227.72  239.86  220.48  261.72  219.79  280.92  217.83  320.01  215.19
  341.87  217.61  356.44  219.17  371.02  219.32  400.16  216.28  422.02  219.75
  443.88     220  458.45   221.6  516.74  219.23  531.31  220.74  655.18  221.78
  707.99   220.8  737.11  217.86   773.5  221.07  839.01  223.89  889.96  232.67
  948.19  238.67 1057.38  248.63 1115.61  252.03 1237.37  264.13 1334.54  270.56
#Mann= 3 , 0 , 0
       0      .1       0  280.92    .045       0  341.87      .1       0
Bank Sta=280.92,341.87
XS Rating Curve= 0 ,0
Exp/Cntr=0.3,0.1

Type RM Length L Ch R = 1 ,10814.38,386.62,338.91,228.5
XS GIS Cut Line= 6
1541138.80931629741441.7512220591540757.30788846741981.653827533
1540623.44773833742111.0519726721540427.11951818742235.988112777
1540293.25936805742276.1461578161540111.22188975 742308.85973452
#Sta/Elev= 30
       0  284.41   68.57  253.79   85.71  248.12  111.43  243.17     180  235.35
  248.57  229.38  394.28  220.22  409.33  216.39  419.99  214.23  454.27  213.77
  471.42  214.76  479.99   216.6  497.13  219.29   505.7  219.53  574.27  218.17
  617.13  219.14  634.27   218.5   690.3  221.08  768.18  219.62  797.39  220.04
   826.6  218.04  847.27  220.98  897.05  223.34  946.83  227.73 1079.98  243.01
 1211.53   253.6 1233.96  257.08 1340.64  266.48 1390.42  268.72 1404.69  270.36
#Mann= 3 , 0 , 0
       0      .1       0  409.33    .045       0  479.99      .1       0
Bank Sta=409.33,479.99
XS Rating Curve= 0 ,0
Exp/Cntr=0.5,0.3

Type RM Length L Ch R = 1 ,10475.47,61.34,63.65,61.37
BEGIN DESCRIPTION:
Elevations below 212 were lowered 1.5 feet based on bridge channel surveys
END DESCRIPTION:
XS GIS Cut Line= 6
1540874.98653339 741111.261868791540611.68743487741212.454466969
1540562.24048255 741757.563981981540450.76375897742151.219442636
1540369.75515753742228.7799950991540100.89237712742292.412311539
#Sta/Elev= 30
       0   274.2   49.25  273.22   98.51  269.24  158.53  261.58  198.78  254.43
  293.39  244.36  307.68  246.28  333.97  246.93   369.1  245.12  523.65   223.4
  629.03  217.94  741.44  217.27  776.56  218.89  797.64  217.66  818.71  213.76
  832.76  210.37  840.91  210.24  862.32  210.38     883  213.26  912.28  217.65
  947.97  219.48 1047.88  220.17 1069.29  222.46 1144.89   223.6 1216.28  227.78
 1279.65  234.08 1372.83  246.23 1564.38  264.34 1621.49   267.2 1642.17   270.8
#Mann= 3 , 0 , 0
       0      .1       0  818.71    .045       0     883      .1       0
Bank Sta=818.71,883
XS Rating Curve= 0 ,0
Exp/Cntr=0.5,0.3

Type RM Length L Ch R = 3 ,10444.30,,,
BEGIN DESCRIPTION:
Pilot Town Road, MDE Bridge #: CE040507PF-3
CE0001
Top of road obtained from DEM.
Opening from MDE2 bridge/culvert surveys.
END DESCRIPTION:
Bridge Culvert--1,0,-1,-1, 0
Deck Dist Width WeirC Skew NumUp NumDn MinLoCord MaxHiCord MaxSubmerge Is_Ogee
11,25,2.6,0, 104, 104, , , 0.95, 0, 2,2,,
  400.49  407.52  414.54  421.57  428.59  435.62  442.64  449.67  456.69  463.72
  470.74  477.77  484.79  491.82  498.85  505.87   512.9  519.92  526.95  533.97
     541  548.02  555.05  562.07   569.1  576.12  583.15  590.17   597.2  604.22
  611.25  618.27   625.3  632.33  639.35  646.38   653.4  660.43  667.45  674.48
   681.5  688.53  695.55  702.58   709.6  716.63  723.65  730.68   737.7  744.73
  751.76  758.78  765.81  772.83  779.86  786.88  793.91  800.93     827     827
     872     872  901.26   908.4  915.54  922.67  929.81  936.95  944.08  951.22
  958.36  965.49  972.63  979.77  986.91  994.04 1001.18 1008.32 1015.45 1022.59
 1029.73 1036.86    1044 1051.14 1058.28 1065.41 1072.55 1079.69 1086.82  1092.7
 1100.07 1107.45 1114.83 1122.21 1129.59 1136.97 1144.35 1151.72  1159.1 1166.48
 1173.86 1181.24 1186.72 1194.68
  235.65   235.1  234.41  233.76  233.16  232.59  231.87   231.3  230.63  230.06
   229.4  228.71  228.05  227.53  226.93  226.34  225.77  225.28  224.66  224.27
  223.95  223.58  223.36  223.04  222.83  222.57  222.37  222.12  221.94  221.86
   221.8  221.73  221.53  221.42  221.19   221.2  221.22  221.26  221.14  221.07
  221.19  221.25   221.1  221.01  221.02  221.13  220.99  220.95  220.99  221.09
  220.98  220.97  220.96  221.03  220.95  220.95   220.9  220.84   220.8   222.8
   222.8   220.8   220.8  220.77  220.72   220.7  220.74  220.74  220.74  220.91
  220.89  220.72     221  221.01  220.93  220.88  220.88  220.96  221.15  221.05
  221.01  221.17  221.25  221.19  221.32  221.55   221.6  221.67  221.95  222.12
  222.02   222.1  222.27  222.38  222.51  222.77  223.08  223.34  223.59     224
  224.48  224.99  225.28  225.77
                                                                                
                                                                                
                                                                                
                                                                                
                                                                                
                                                                           218.3
   218.3
                                                                                
                                                                                
                                                                                
                                
  457.49  464.52  471.54  478.57  485.59  492.62  499.64  506.67  513.69  520.72
  527.74  534.77  541.79  548.82  555.85  562.87   569.9  576.92  583.95  590.97
     598  605.02  612.05  619.07   626.1  633.12  640.15  647.17   654.2  661.22
  668.25  675.27   682.3  689.33  696.35  703.38   710.4  717.43  724.45  731.48
   738.5  745.53  752.55  759.58   766.6  773.63  780.65  787.68   794.7  801.73
  808.76  815.78  822.81  829.83  836.86  843.88  850.91  857.93     884     884
     929     929  958.26   965.4  972.54  979.67  986.81  993.95 1001.08 1008.22
 1015.36 1022.49 1029.63 1036.77 1043.91 1051.04 1058.18 1065.32 1072.45 1079.59
 1086.73 1093.86    1101 1108.14 1115.28 1122.41 1129.55 1136.69 1143.82  1149.7
 1157.07 1164.45 1171.83 1179.21 1186.59 1193.97 1201.35 1208.72  1216.1 1223.48
 1230.86 1238.24 1243.72 1251.68
  235.65   235.1  234.41  233.76  233.16  232.59  231.87   231.3  230.63  230.06
   229.4  228.71  228.05  227.53  226.93  226.34  225.77  225.28  224.66  224.27
  223.95  223.58  223.36  223.04  222.83  222.57  222.37  222.12  221.94  221.86
   221.8  221.73  221.53  221.42  221.19   221.2  221.22  221.26  221.14  221.07
  221.19  221.25   221.1  221.01  221.02  221.13  220.99  220.95  220.99  221.09
  220.98  220.97  220.96  221.03  220.95  220.95   220.9  220.84   220.8   222.8
   222.8   220.8   220.8  220.77  220.72   220.7  220.74  220.74  220.74  220.91
  220.89  220.72     221  221.01  220.93  220.88  220.88  220.96  221.15  221.05
  221.01  221.17  221.25  221.19  221.32  221.55   221.6  221.67  221.95  222.12
  222.02   222.1  222.27  222.38  222.51  222.77  223.08  223.34  223.59     224
  224.48  224.99  225.28  225.77
                                                                                
                                                                                
                                                                                
                                                                                
                                                                                
                                                                           218.3
   218.3
                                                                                
                                                                                
                                                                                
                                
BR Coef=-1 , 0 , 0 ,, 0 ,,,0.8,0,,0,
WSPro=,,,, 1 ,,,, 0 ,,,, 0 ,,,,-1 ,-1 ,-1 , 0 , 0 , 0 , 0 , 0
BC Design=,, 0 ,, 0 ,,,,,,
BC Use User HTab Curves=0
BC User HTab FreeFlow(D)= 0

Type RM Length L Ch R = 1 ,10411.83,260.11,340.72,408.61
BEGIN DESCRIPTION:
Elevations below 212 were lowered 1.5 feet based on bridge channel surveys
END DESCRIPTION:
XS GIS Cut Line= 6
1540868.91614726741051.5697385521540680.34308881 741083.11506331
1540556.14816602741184.5205340681540502.73971039741749.147028387
1540400.68912371742117.705384687 1540089.1114067742233.580273196
#Sta/Elev= 30
       0  279.64   63.32  274.98   91.47  269.95  119.79  269.71  184.93  265.85
  368.55  243.56  519.99  230.91  562.14  225.82  702.64  219.24  843.15  219.15
  864.23   217.9  878.28  214.57  899.35   210.4   913.4  210.31   921.7  210.42
  935.97  215.15  943.11  217.81  964.52  219.61  993.07  220.42 1014.48  219.17
  1057.3  219.54 1142.94  222.67 1211.18  223.57 1272.92  227.45 1344.07  234.46
 1467.51  253.83 1531.76  259.93 1596.01  264.45 1624.57  265.14 1648.66  269.78
#Mann= 3 , 0 , 0
       0      .1       0  878.28    .045       0  935.97      .1       0
Bank Sta=878.28,935.97
XS Rating Curve= 0 ,0
Exp/Cntr=0.5,0.3