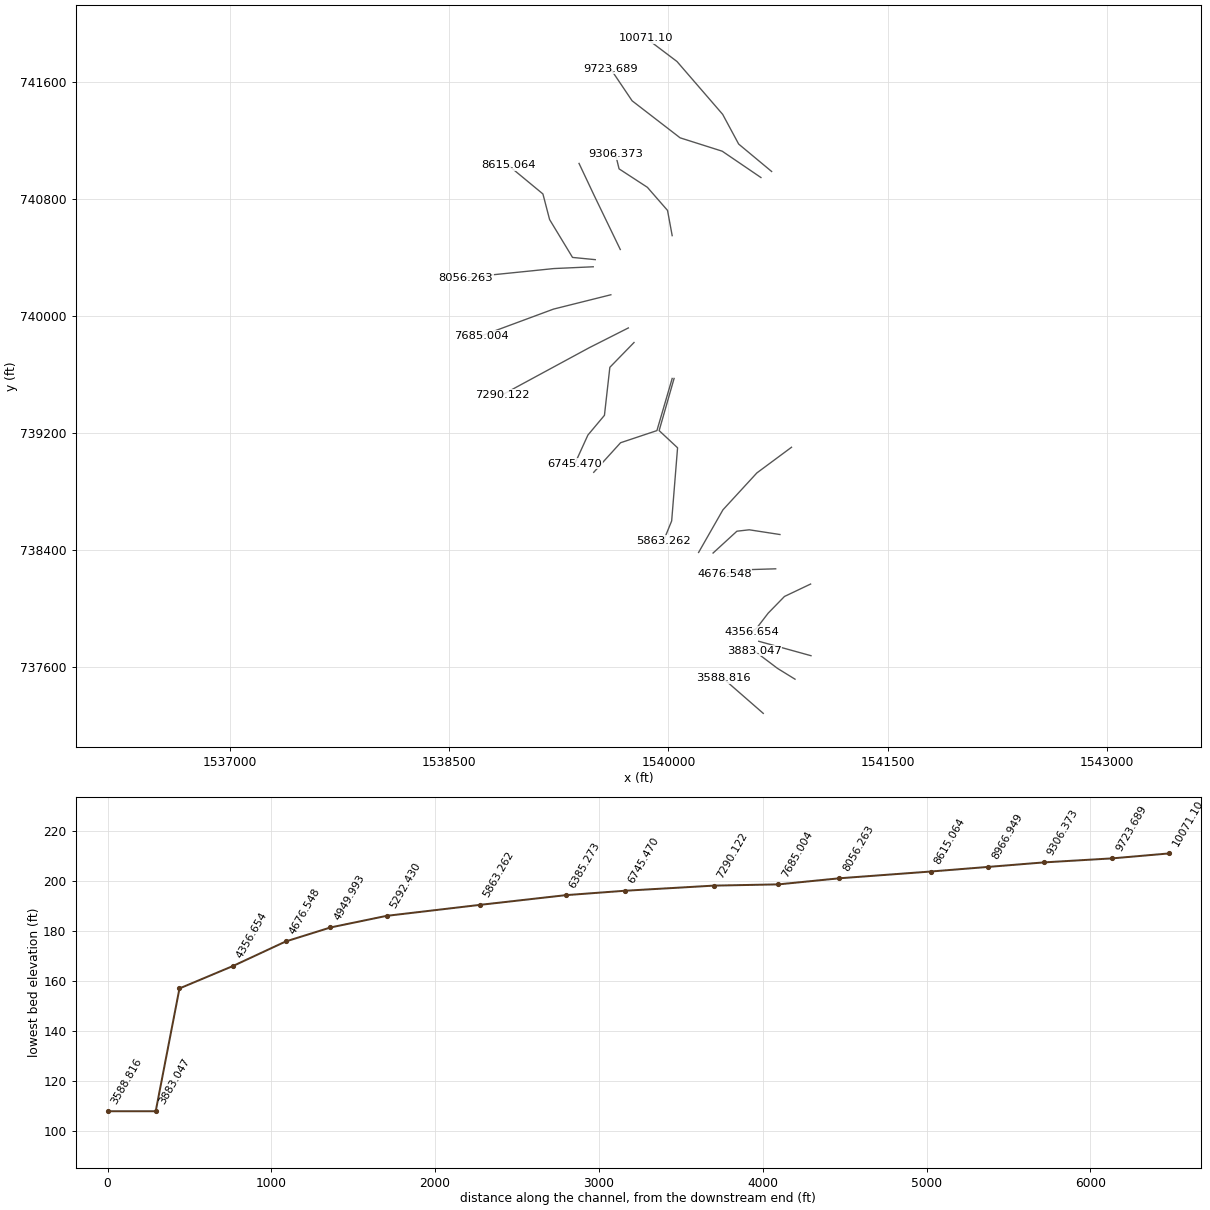
HEC-RAS study Conowingo_Creek.prj: Conowingo_Creek

--- Conowingo_Creek.g01 (geometry) --- (continued)

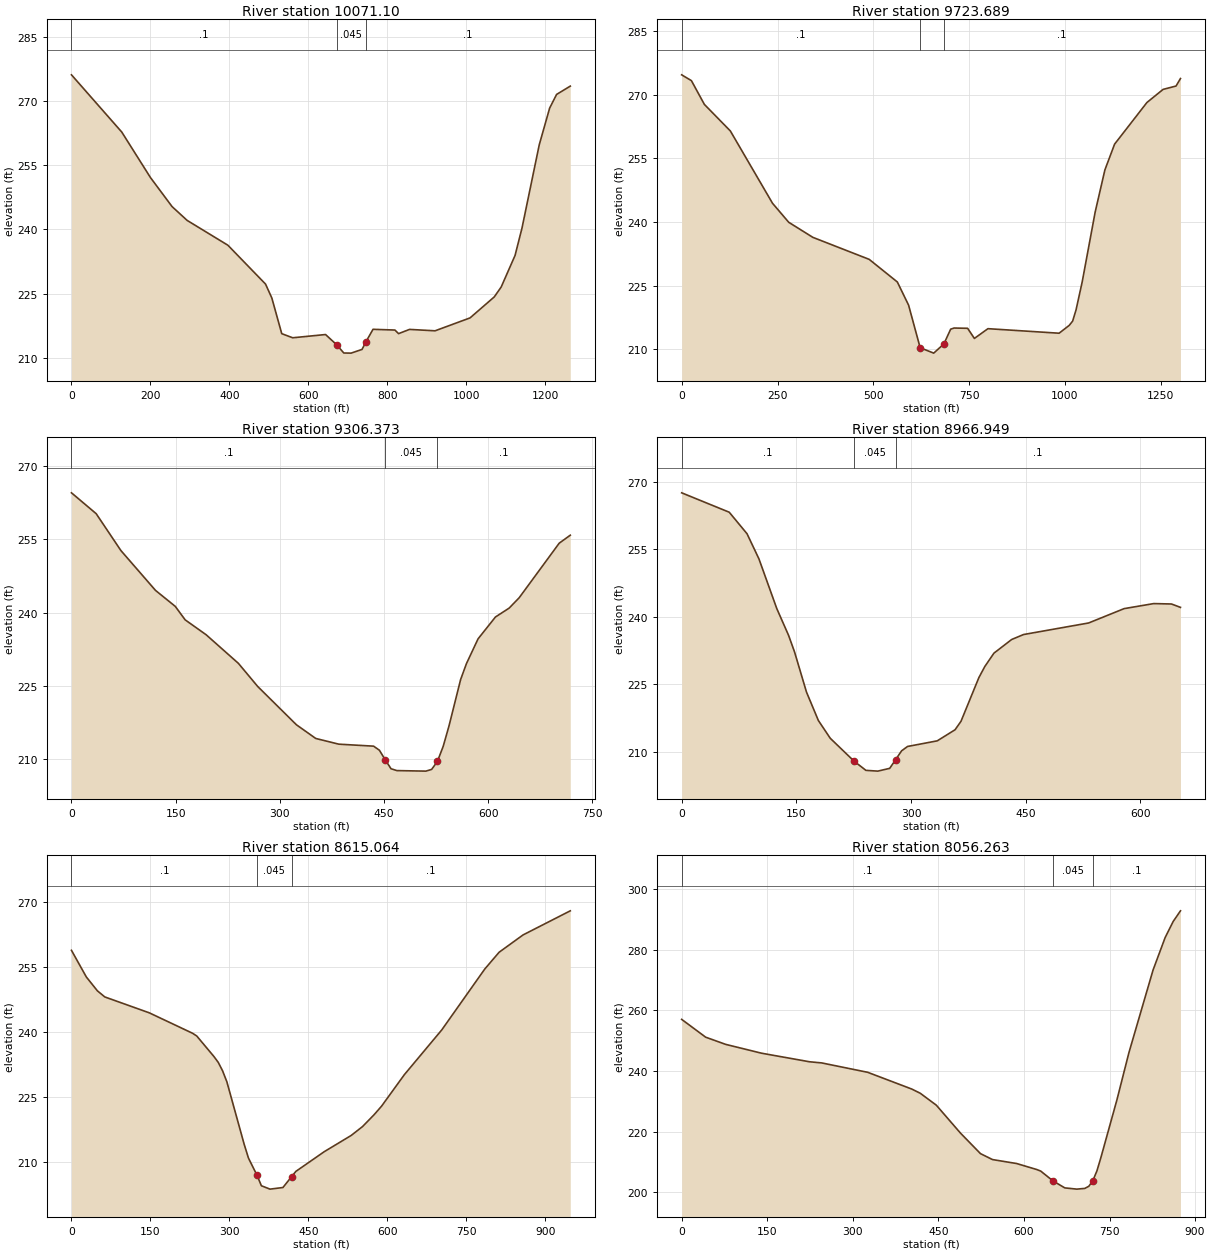
Type RM Length L Ch R = 1 ,10071.10,314.8,347.42,369.78
XS GIS Cut Line= 5
1540705.99483094740988.8577141311540480.66357824741176.261924312
1540371.34445564741379.2831519991540059.00410536741740.705557317
1539849.28987014741899.106734961
#Sta/Elev= 30
       0  276.16  127.46  262.77   200.3  252.11  254.93  245.34  293.08  242.11
  396.43   236.3  491.83  227.21  507.74  223.97  532.91  215.61  560.67  214.65
  643.93  215.41  671.69  213.05  690.19  211.09   708.7  211.06  736.45  211.93
   745.7  213.62  764.21  216.63  819.72  216.46  828.97  215.62  856.72  216.61
  921.49  216.28 1010.12   219.3 1071.52  224.21 1089.07  226.53 1124.16   233.9
  1141.7  240.28 1185.56  259.81 1211.88  268.38 1229.43  271.57 1264.16  273.52
#Mann= 3 , 0 , 0
       0      .1       0  671.69    .045       0   745.7      .1       0
Bank Sta=671.69,745.7
XS Rating Curve= 0 ,0
Exp/Cntr=0.3,0.1

Type RM Length L Ch R = 1 ,9723.689,418.97,417.32,420.57
XS GIS Cut Line= 5
1540632.92029375740947.5090756711540368.05444874741127.586512491
1540080.29206525741218.9396501031539752.16985132741472.045032173
1539604.32502273741691.638086393
#Sta/Elev= 30
       0  274.64   25.39  273.27   59.25  267.67  126.97  261.42  237.01  244.38
  279.33   239.9  342.32  236.35   489.2  231.17  562.64  225.84  592.02  220.38
   622.2  210.35  657.56  209.08  684.08  211.25  701.76  214.72   710.6  214.99
  745.97  214.93  763.65  212.54  799.01  214.84  984.66  213.77 1011.18  215.62
 1020.02  216.63 1028.87  219.26 1045.04  225.91 1078.79  242.32 1104.11  252.23
 1129.42  258.31 1213.81  268.12    1256  271.21 1289.76     272 1301.32  273.77
#Mann= 3 , 0 , 0
       0      .1       0   622.2    .045       0  684.08      .1       0
Bank Sta=622.2,684.08
XS Rating Curve= 0 ,0
Exp/Cntr=0.3,0.1

Type RM Length L Ch R = 1 ,9306.373,385.79,339.42,295.08
XS GIS Cut Line= 5
1540026.11762194740550.1890420911539994.29666133740722.640293449
1539856.53090683740880.6657177811539663.02811642  741006.7686598
1539638.75190014 741106.27078037
#Sta/Elev= 30
       0  264.55   35.59  260.27   71.18  252.71  121.01  244.54  149.48  241.26
  163.72   238.5  193.94  235.44  240.37  229.58  268.23  224.83  323.95  216.98
  351.81  214.17  385.01     213  435.14  212.59   443.5  211.75  451.85   209.8
  460.21  207.96  468.56  207.58  510.34  207.47  518.69  207.82  527.05  209.46
   535.4  212.57  543.76  216.76  560.47  226.26  568.82  229.51  585.53  234.59
   610.6  239.08  630.38  240.91   644.8  243.03  702.44  254.22  718.39  255.86
#Mann= 3 , 0 , 0
       0      .1       0  451.85    .045       0  527.05      .1       0
Bank Sta=451.85,527.05
XS Rating Curve= 0 ,0
Exp/Cntr=0.3,0.1

Type RM Length L Ch R = 1 ,8966.949,346.97,351.89,354.14
XS GIS Cut Line= 3
1539671.29131329740455.5666571111539493.54787079740823.311710477
1539389.35343902741043.958742514
#Sta/Elev= 30
       0  267.53    62.2  263.22   85.52  258.43  101.07  252.85   124.4  241.81
  139.95  235.81  147.72  232.12  163.27  223.24  178.82  216.92  194.37  212.97
  225.47  207.89  241.02  205.84  256.57  205.67  272.12  206.29  279.89  208.22
  287.67  210.18  295.44  211.15  334.31   212.4  357.64  214.87  365.41  216.76
  388.74  226.45  396.51  228.92  408.45  231.89  431.67  234.93  447.15  236.03
  532.31   238.6  578.75  241.79  617.46  242.91  640.68  242.82  652.46  242.07
#Mann= 3 , 0 , 0
       0      .1       0  225.47    .045       0  279.89      .1       0
Bank Sta=225.47,279.89
XS Rating Curve= 0 ,0
Exp/Cntr=0.3,0.1

Type RM Length L Ch R = 1 ,8615.064,434.27,558.8,637.82
XS GIS Cut Line= 5
1539500.19964144740386.1035455021539344.89930744740401.329068437
1539188.07642123740660.1629583541539142.39985242740835.256472111
 1538905.2470919741031.324509636
#Sta/Elev= 30
       0  258.89   28.13  252.76   49.23  249.55    63.3  248.14   147.7  244.48
  229.71  239.78  237.89  239.14  270.63  234.39  278.81  233.04     287   231.1
  295.18  228.55  327.92  214.19  336.11  210.99  352.48  206.98  360.66   204.6
  377.03  203.82  401.58  204.19  417.95  206.68  426.14  207.91  480.38  212.48
  531.02  216.18  552.73  218.24  574.43  220.94   588.9  222.95   632.3  230.23
  703.21  240.53  784.96  254.58   812.2  258.45  857.62  262.44  947.34     268
#Mann= 3 , 0 , 0
       0      .1       0  352.48    .045       0  417.95      .1       0
Bank Sta=352.48,417.95
XS Rating Curve= 0 ,0
Exp/Cntr=0.3,0.1

Type RM Length L Ch R = 1 ,8056.263,343.26,371.26,379.19
XS GIS Cut Line= 4
1539486.49667078740337.3818721181539217.00491482 740325.20145376
1539069.31734233740309.9759308251538615.55956201740263.911200136
#Sta/Elev= 30
       0  257.07   42.04   251.2   77.08  248.83  140.14  245.91  224.23  243.09
  245.25  242.72  326.06  239.62  403.47  234.09  418.24  232.71  446.38  228.78
   488.6   219.6  523.78  212.81  544.88  210.85   587.1  209.55  622.28  207.58
  629.32  207.06  650.94  203.81  671.53  201.52  692.64  201.11  706.71  201.35
  713.75  202.06  720.78  203.93  727.82  207.09  734.86  211.52     763  230.58
  784.11   246.2  826.32  273.36  847.43  284.02   861.5  289.32  874.33  292.85
#Mann= 3 , 0 , 0
       0      .1       0  650.94    .045       0  720.78      .1       0
Bank Sta=650.94,720.78
XS Rating Curve= 0 ,0
Exp/Cntr=0.3,0.1

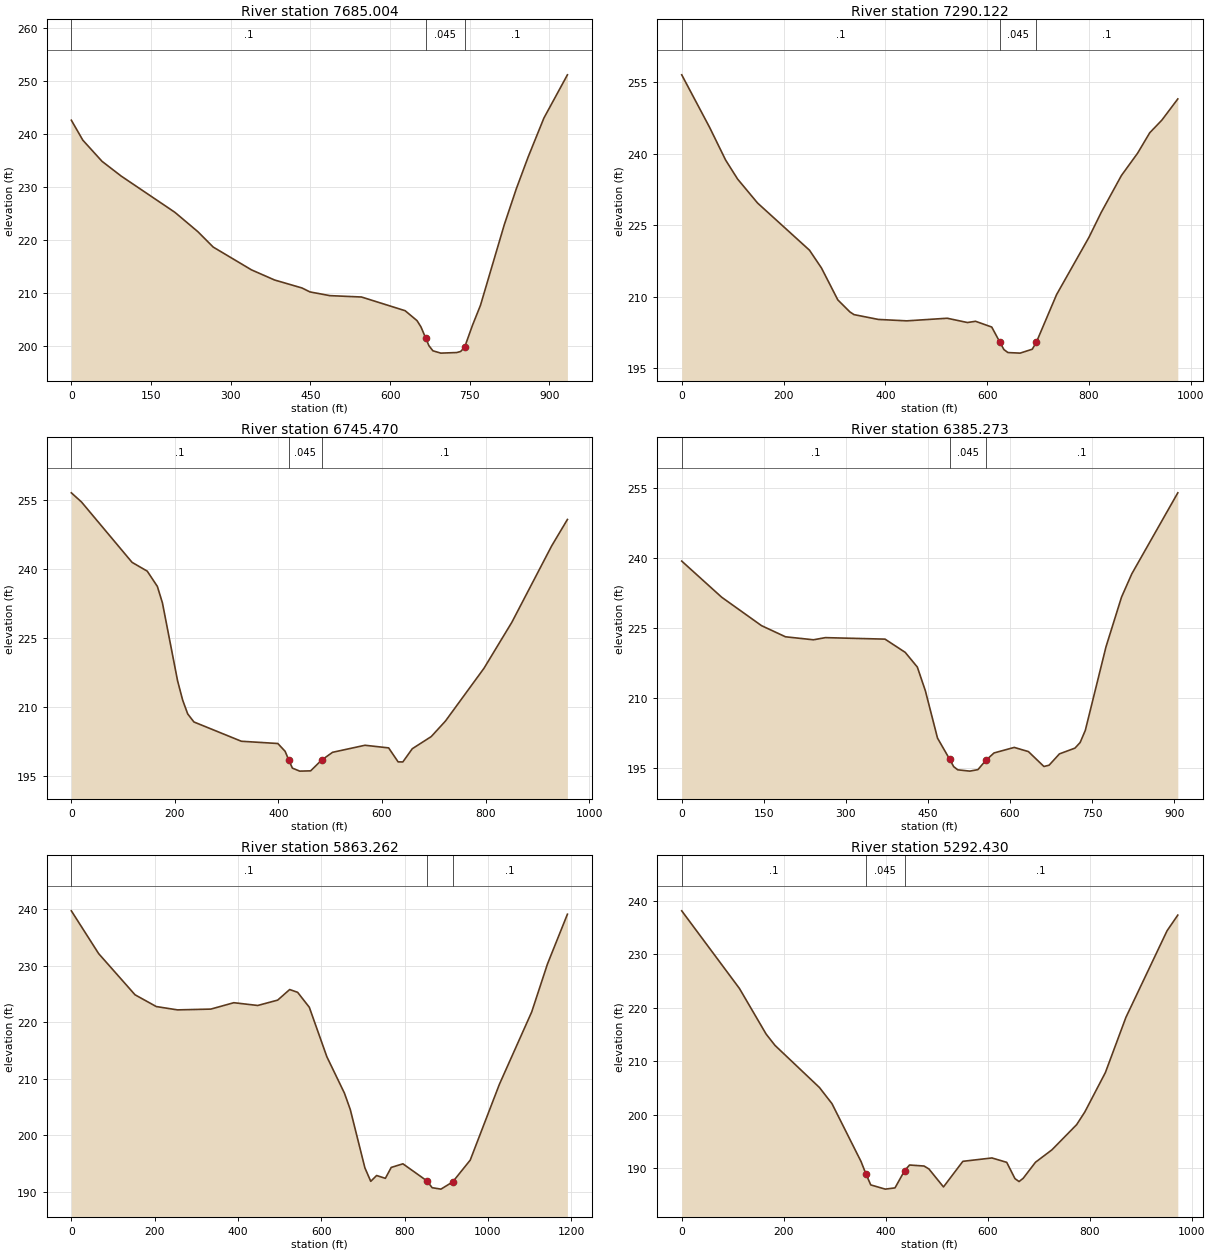
Type RM Length L Ch R = 1 ,7685.004,380.75,394.88,402.46
XS GIS Cut Line= 3
1539606.93592894 740146.047903881539214.67453872740047.982556313
1538718.21871665739864.110029638
#Sta/Elev= 30
       0  242.55   21.65  238.79   57.72  234.81    93.8  232.03  194.82  225.21
  238.11  221.56  266.97  218.66  339.13  214.36  382.42  212.46  434.19  210.95
  449.12  210.21  486.45  209.51  546.16  209.25  628.27  206.67  650.67   204.8
  658.13  203.61  666.97  201.52  673.06  200.08  680.53  199.12  695.46  198.68
  725.31  198.79  732.78  198.99  740.24  199.79  755.17  203.96   770.1  207.69
  814.89  222.86  837.28  229.56  859.68  235.59  889.54  242.97  933.74   251.1
#Mann= 3 , 0 , 0
       0      .1       0  666.97    .045       0  740.24      .1       0
Bank Sta=666.97,740.24
XS Rating Curve= 0 ,0
Exp/Cntr=0.3,0.1

Type RM Length L Ch R = 1 ,7290.122,338.21,544.65,573.94
XS GIS Cut Line= 3
1539726.45307127739919.271787643 1539459.8379076739784.431934729
1538865.31673799 739462.65501304
#Sta/Elev= 30
       0  256.57   54.91  245.52   86.29  238.68  109.82   234.7  149.04  229.67
  251.02  219.78  274.55  216.05  306.73  209.35  330.61  206.81  338.57  206.26
  386.33  205.25  442.04  204.95  521.64   205.5  561.44   204.6  577.36  204.86
   609.2  203.65  625.11  200.49  633.07  198.93  641.03   198.3  664.91  198.18
  688.79     199  696.75  200.44  736.55  210.45  800.22  222.48   824.1  227.66
   863.9  235.43  895.74  240.12  919.62  244.41   943.5  247.07  974.79  251.51
#Mann= 3 , 0 , 0
       0      .1       0  625.11    .045       0  696.75      .1       0
Bank Sta=625.11,696.75
XS Rating Curve= 0 ,0
Exp/Cntr=0.3,0.1

Type RM Length L Ch R = 1 ,6745.470,456.05,360.2,228.19
XS GIS Cut Line= 5
1539765.21498325739819.6616537271539599.97664544739650.074938565
1539563.01543827739321.7724515351539449.95762813739186.972754896
1539360.81589328738991.295775846
#Sta/Elev= 30
       0  256.48   19.55   254.5  117.28   241.4   146.6  239.49  166.15  236.18
  175.92  232.61  205.24  215.69  215.01  211.52  224.79  208.52  236.78  206.78
  328.35   202.6  398.79  202.11  412.88  200.42  419.65   198.6  426.97  196.77
  441.06  196.12  462.19  196.18  483.32  198.51  504.46   200.2  567.15  201.73
  612.83  201.16  631.11  198.13  640.24  198.11  658.51  200.98  695.06  203.61
  722.47  206.97  796.93  218.42  850.78   228.4   927.7  244.97  958.11   250.7
#Mann= 3 , 0 , 0
       0      .1       0  419.65    .045       0  483.32      .1       0
Bank Sta=419.65,483.32
XS Rating Curve= 0 ,0
Exp/Cntr=0.3,0.1

Type RM Length L Ch R = 1 ,6385.273,416.27,522.01,609.01
XS GIS Cut Line= 4
1540026.11762194739573.9783356041539921.75656651739217.411396071
1539673.19964579739134.3942730431539489.72476605738932.226374581
#Sta/Elev= 30
       0  239.28   72.94  231.56  145.87  225.47  189.64  223.09  240.69  222.45
  262.57  222.91  371.53  222.59  408.43  219.76  430.57  216.62  445.33  211.52
  467.47  201.42  489.61  196.91  496.99  195.32  504.37  194.64  526.51  194.36
  541.27  194.68  556.03  196.69  570.79  198.25  607.69  199.43  633.58  198.54
  661.94  195.35  671.39  195.63   690.3  198.05  718.66  199.28  728.11  200.48
  737.56  203.07  775.37  220.95  803.73  231.57  822.64  236.58  906.59  253.88
#Mann= 3 , 0 , 0
       0      .1       0  489.61    .045       0  556.03      .1       0
Bank Sta=489.61,556.03
XS Rating Curve= 0 ,0
Exp/Cntr=0.3,0.1

Type RM Length L Ch R = 1 ,5863.262,582.77,570.83,357.04
XS GIS Cut Line= 5
1540039.16275388739573.9783356041539936.97588703739217.411396071
1540062.95037919739099.8401742581540022.62539716738599.978417993
1539967.32122362738464.621474698
#Sta/Elev= 30
       0  239.74   65.54  232.17  152.92  224.88  203.89   222.8  254.86  222.21
  334.96  222.35  390.07  223.48  447.52  222.99   495.4  223.94  524.12  225.81
  543.24  225.32  571.33  222.67  613.46  213.91   655.6  207.48  669.65  204.58
  704.76  194.25  718.81  191.87  732.85   192.9  753.92   192.4  767.96  194.33
  796.06  194.97  853.43  191.96  866.28  190.74  887.35  190.49  915.44  191.76
  957.58  195.62 1027.81  209.07 1105.22  221.85 1143.03  230.33 1190.94  239.14
#Mann= 3 , 0 , 0
       0      .1       0  853.43    .045       0  915.44      .1       0
Bank Sta=853.43,915.44
XS Rating Curve= 0 ,0
Exp/Cntr=0.3,0.1

Type RM Length L Ch R = 1 ,5292.430,377.27,342.44,181.06
XS GIS Cut Line= 4
1540841.83520527739103.462664828 1540605.0835301 738928.09105356
 1540373.1216931738675.7729743721540206.73944165738384.439058647
#Sta/Elev= 30
       0  238.14  113.25  223.61  165.51  215.09  182.94  212.97  270.05   205.1
  294.63  202.08  351.68  191.25  361.19  188.95   370.7  186.88  399.22  186.09
  418.24  186.32  437.26  189.57  446.77   190.6  475.29  190.41   484.8  189.86
  513.33   186.5  551.36  191.29  608.41  191.92  637.37   191.1  653.49  188.06
  661.55  187.51  669.61  188.11   693.8  191.12  726.04  193.44  774.41  198.14
  790.53  200.52  830.84  207.89  871.14  218.22  951.75   234.4  972.87  237.34
#Mann= 3 , 0 , 0
       0      .1       0  361.19    .045       0  437.26      .1       0
Bank Sta=361.19,437.26
XS Rating Curve= 0 ,0
Exp/Cntr=0.3,0.1

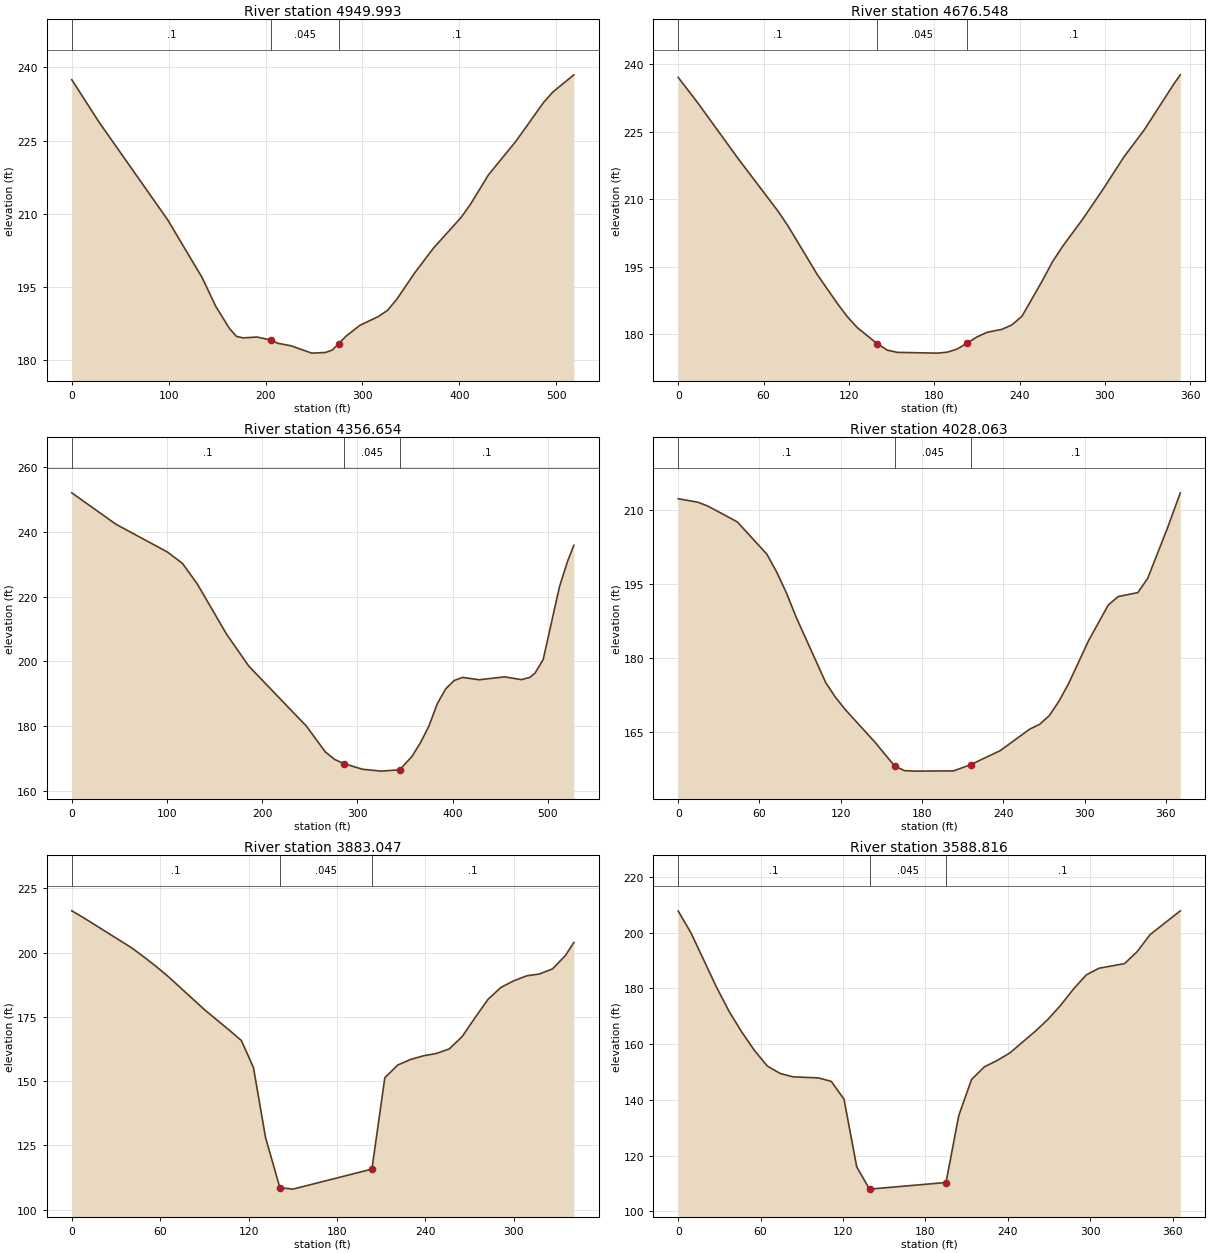
Type RM Length L Ch R = 1 ,4949.993,265.25,273.45,265.05
XS GIS Cut Line= 4
1540762.91798022 738506.948655651540552.97318281738539.278540239
1540468.66779698738529.6436389831540305.69913657738380.430564687
#Sta/Elev= 30
       0  237.46   28.33  228.72   99.16  208.71  134.57  196.91  148.73     191
   162.9  186.46  169.98  184.88  177.06  184.57  191.23  184.75  205.39  184.13
  212.42  183.48  226.51  182.94  247.65  181.45  261.74  181.58  268.78  182.07
  275.83  183.42  282.88  184.89  297.27  187.13  316.26  188.93  325.75  190.18
  335.24  192.42  354.22  197.95   373.2  202.93  401.67   209.2  411.16  211.82
  430.15  217.98  458.62   224.9  487.09  232.83  496.58  234.94  518.23  238.46
#Mann= 3 , 0 , 0
       0      .1       0  205.39    .045       0  275.83      .1       0
Bank Sta=205.39,275.83
XS Rating Curve= 0 ,0
Exp/Cntr=0.3,0.1

Type RM Length L Ch R = 1 ,4676.548,285.07,319.89,367.45
XS GIS Cut Line= 3
1540733.73155254738272.5625325591540506.40449351738265.486763537
1540383.36370726738240.133275658
#Sta/Elev= 30
       0  237.01   14.01  231.25   42.02  219.04   70.03   207.4   77.04  204.14
   98.05  193.15  112.05   186.8  119.06  183.87  126.06  181.47  140.07   177.9
  147.07  176.51  154.07  176.02  182.09  175.85  189.09  176.05  196.09  176.75
   203.1  178.05   210.1  179.45  217.11  180.46  227.44  181.11  234.58   182.1
  241.73  184.03  256.03   191.9  263.17  196.11  270.32  199.54  284.61  205.65
  298.91  212.29   313.2  219.27   327.5  225.28  348.94  235.75  353.06  237.58
#Mann= 3 , 0 , 0
       0      .1       0  140.07    .045       0   203.1      .1       0
Bank Sta=140.07,203.1
XS Rating Curve= 0 ,0
Exp/Cntr=0.3,0.1

Type RM Length L Ch R = 1 ,4356.654,381.14,328.59,264.02
XS GIS Cut Line= 5
  1540972.430461738168.4194038211540793.76026067738083.509582713
1540682.24144097737969.2135506121540603.49965763737866.760419026
1540570.00920781737843.668168768
#Sta/Elev= 30
       0  252.06    46.5  242.34  100.75  233.73  116.25  230.27  131.75  223.95
  162.76  208.33  186.01  198.52  246.72  179.91  266.28  172.06  276.06  169.72
  285.84  168.43   305.4  166.68  324.96   166.1  344.52  166.51  357.51  170.71
  366.34   174.9  375.16  180.03  383.99  186.94  392.82  191.52  401.65  194.08
  410.48  195.05  428.14  194.32  454.62  195.22  472.28  194.36  481.11  195.04
  486.72  196.42  495.23  200.61  512.23  222.97  520.73  230.86   527.4  235.85
#Mann= 3 , 0 , 0
       0      .1       0  285.84    .045       0  344.52      .1       0
Bank Sta=285.84,344.52
XS Rating Curve= 0 ,0
Exp/Cntr=0.3,0.1

Type RM Length L Ch R = 1 ,4028.063,155.65,145.02,129.22
BEGIN DESCRIPTION:
DEM shows very abrupt rise in channel between this cross-section and the cross-section downstream.  It appears there's an error in the DEM.  Because this is an approximate study with limited funds, and because it appears that the local vicinity is wooded with no structures, the DEM is being used, as delivered.
END DESCRIPTION:
XS GIS Cut Line= 3
1540975.14086029 737678.495388151540773.97372979737734.162105948
1540617.74576424737777.118962795
#Sta/Elev= 30
       0  212.37   14.53  211.66   21.79  210.89   43.58  207.68   65.37  201.14
   72.63  197.52   79.89  193.26   87.16  188.27  108.95  175.03  116.21  172.02
  123.47  169.53  145.26  162.95  159.79  158.11  167.05  157.17  174.31  157.07
  203.37  157.12  215.99  158.39  237.77  161.23  259.55   165.6  266.81  166.56
  274.07  168.35  281.33  171.35  288.58  175.02   303.1  183.62  317.62  190.81
  324.88  192.51   339.4  193.32  346.66  196.21  361.18  206.35  370.75  213.57
#Mann= 3 , 0 , 0
       0      .1       0  159.79    .045       0  215.99      .1       0
Bank Sta=159.79,215.99
XS Rating Curve= 0 ,0
Exp/Cntr=0.3,0.1

Type RM Length L Ch R = 1 ,3883.047,296.32,294.23,292.6
XS GIS Cut Line= 4
1540865.93490773737517.9802982961540745.67120743737592.047312766
 1540702.9163332 737624.565104441540586.35713725737712.151804656
#Sta/Elev= 30
       0  216.28    8.22  213.53   41.11   201.7   49.33  198.18   57.55  194.51
   65.77  190.55   90.43  177.64  106.87  169.86  115.09  165.82  123.32  155.27
  131.54     128  141.24  108.56  150.04  107.98  203.71  115.77  212.47  151.32
  221.23  156.27  229.98  158.44  238.74  159.87  247.49  160.78  256.25  162.56
  265.01  167.38  273.76  174.75  282.52  181.83  291.27  186.47  300.03  189.06
  308.79  190.99  317.54  191.72   326.3   193.7  335.05  198.89  340.76  203.97
#Mann= 3 , 0 , 0
       0      .1       0  141.24    .045       0  203.71      .1       0
Bank Sta=141.24,203.71
XS Rating Curve= 0 ,0
Exp/Cntr=0.3,0.1

Type RM Length L Ch R = 1 ,3588.816,261.23,258.45,252.99
XS GIS Cut Line= 2
 1540648.7537393737284.2614883181540373.12106408737524.556641042
#Sta/Elev= 30
       0  207.71    9.29  199.88   27.86  180.43   37.15  171.63   46.43  164.21
   55.72  157.58   65.01  152.08   74.29  149.46   83.58  148.26  102.15  147.87
  111.44  146.63  120.73  140.25  130.01  115.95   139.3  107.98  195.02  110.35
  204.31  134.36  213.59  147.28  222.88  151.81  232.17   154.1  241.45   156.8
  260.03  164.59  269.31  168.88   278.6  173.98  287.89  179.76  297.17  184.81
  306.46  187.22  325.03  188.86  334.32   193.2   343.6  199.24  365.67   207.8
#Mann= 3 , 0 , 0
       0      .1       0   139.3    .045       0  195.02      .1       0
Bank Sta=139.3,195.02
XS Rating Curve= 0 ,0
Exp/Cntr=0.3,0.1