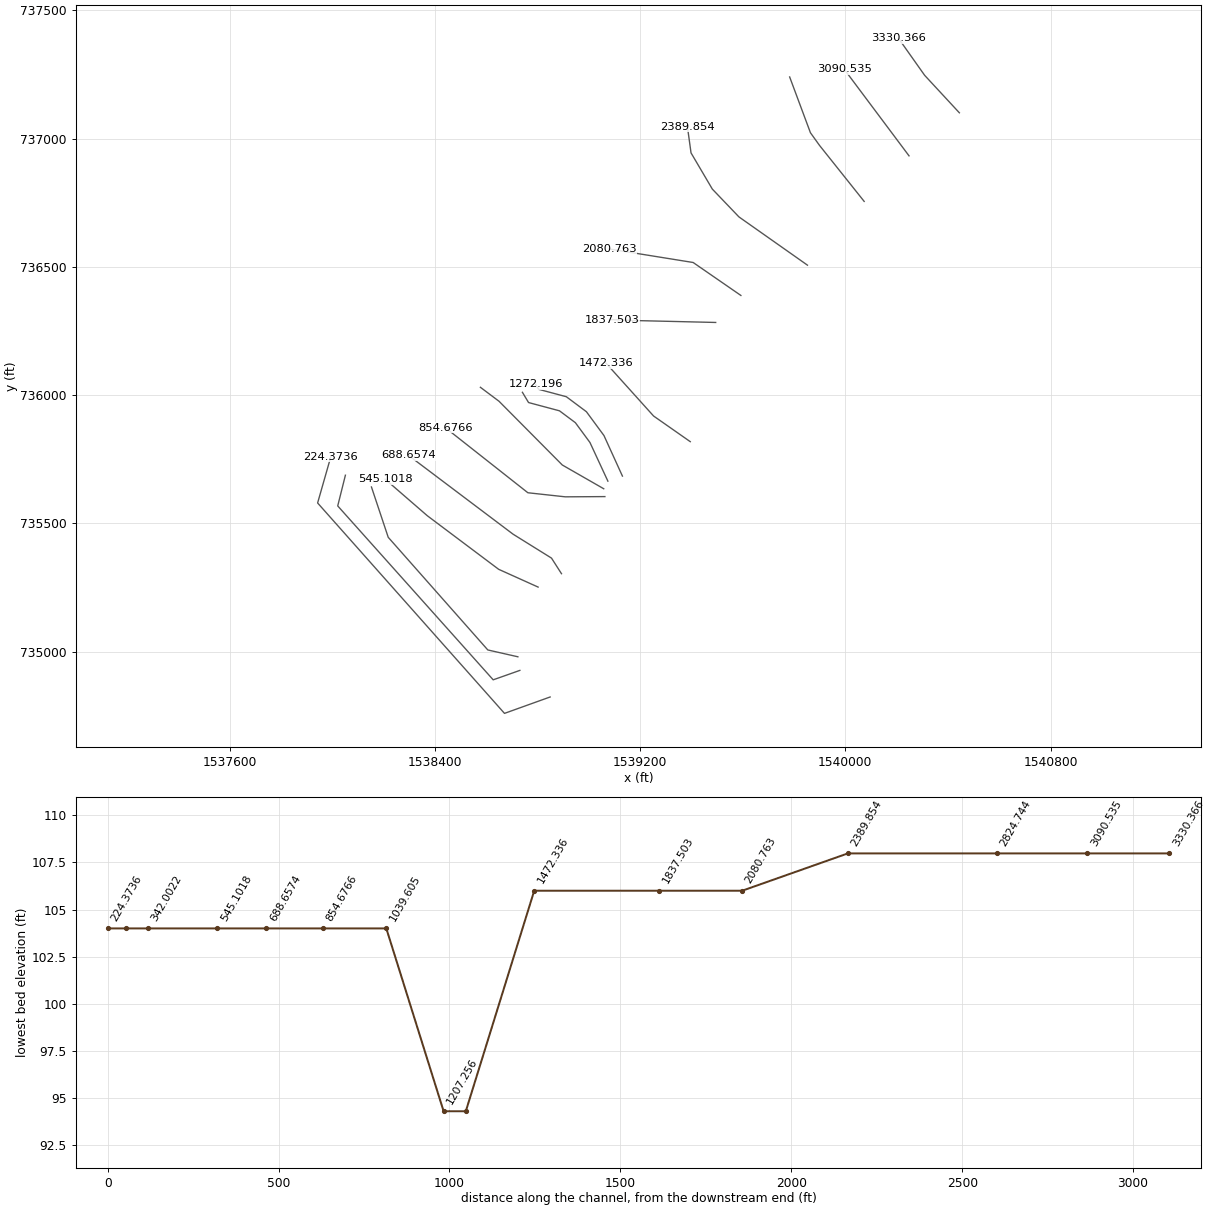
HEC-RAS study Conowingo_Creek.prj: Conowingo_Creek

--- Conowingo_Creek.g01 (geometry) --- (continued)

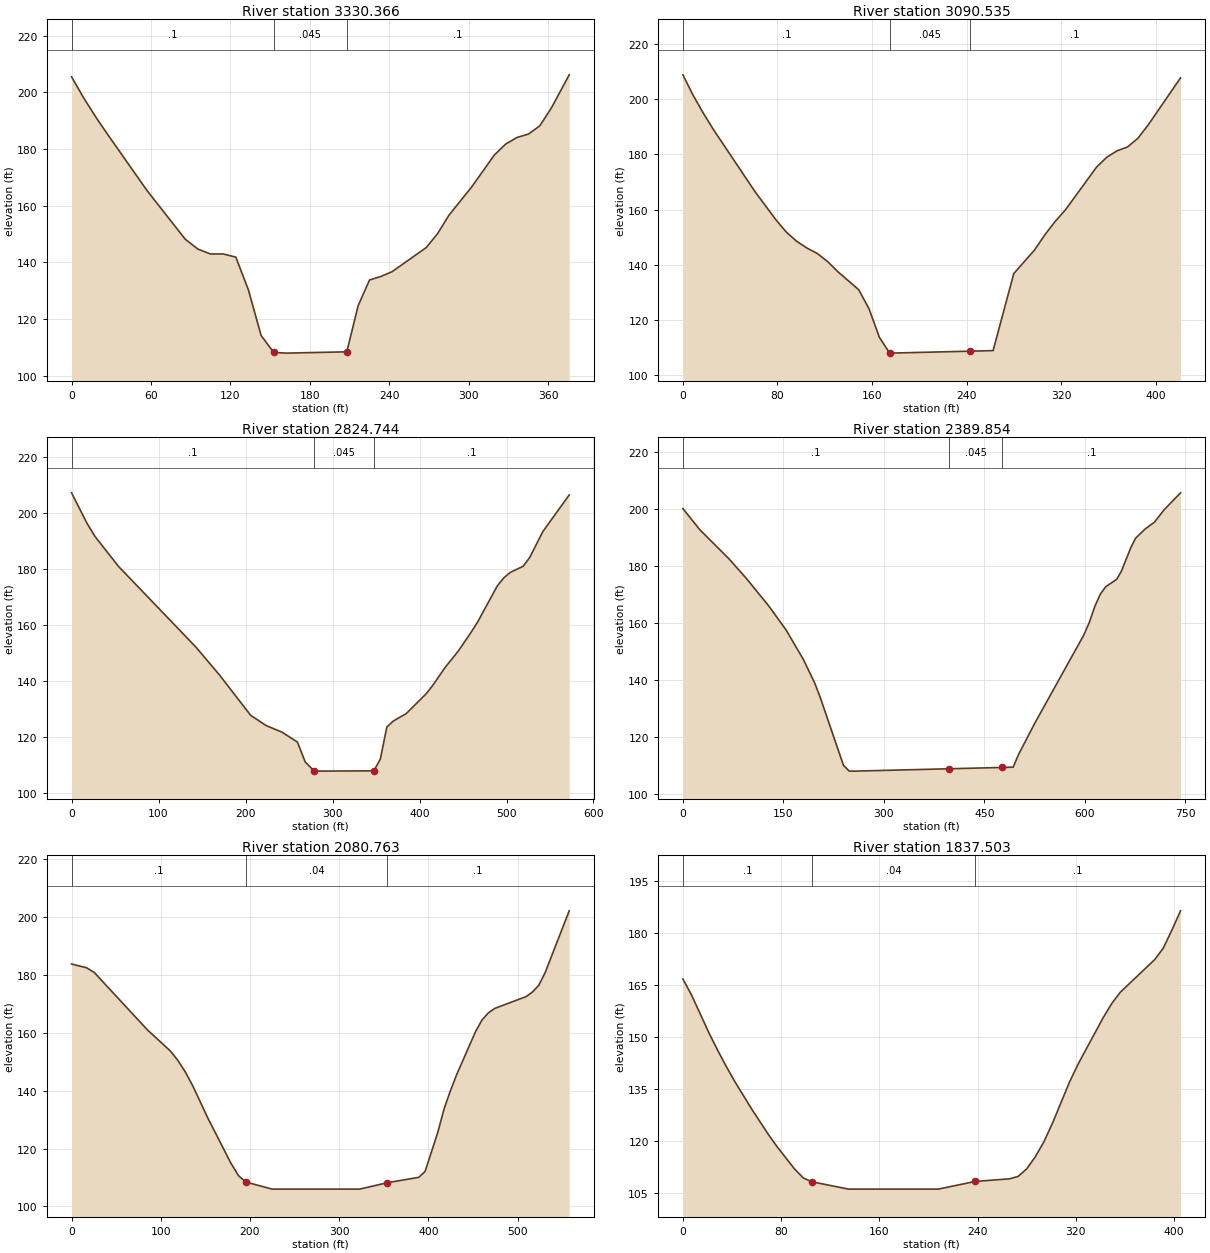
Type RM Length L Ch R = 1 ,3330.366,242.41,239.83,238.21
XS GIS Cut Line= 3
1540444.48537737737101.1155230851540309.08974531737247.298503026
1540207.20249407737391.414601475
#Sta/Elev= 30
       0  205.48    9.54  197.76   19.08  190.75   28.62  184.26   57.25   165.2
   85.87  148.18   95.41  144.69  104.95  142.97  114.49  142.98  124.04  141.86
  133.58  130.24  143.12  114.21  152.66  108.22   162.2  107.98  207.82  108.44
   216.4  124.72  224.97  133.79  233.54  135.03  242.12  136.75  267.83  145.25
  276.41  150.18  284.98  156.67  302.12  166.64  319.27  177.93  327.84  181.78
  336.42   184.1  344.99  185.29  353.56  188.21  362.13  194.37  375.75   206.2
#Mann= 3 , 0 , 0
       0      .1       0  152.66    .045       0  207.82      .1       0
Bank Sta=152.66,207.82
XS Rating Curve= 0 ,0
Exp/Cntr=0.3,0.1

Type RM Length L Ch R = 1 ,3090.535,264.95,265.79,259.63
XS GIS Cut Line= 2
1540248.26181805736933.2420985251539996.18749116737270.126479313
#Sta/Elev= 30
       0  208.88    8.74  201.41   17.49  194.83   26.23  188.78    61.2   166.4
   78.68  156.32   87.43  151.89   96.17  148.53  104.91  146.08  113.65  144.11
   122.4  141.17  131.14  137.46  148.63  130.99  157.37  124.08  166.11  113.73
  174.85  107.98  242.35108.6826  262.28  108.89  279.77  136.82  297.25  145.33
  305.99  150.85  314.74  155.71  323.48  159.95  349.71  175.39  358.45  179.03
  367.19  181.35  375.93  182.74  384.68  185.85  393.42  190.72  420.75  207.79
#Mann= 3 , 0 , 0
       0      .1       0  174.85    .045       0  242.35      .1       0
Bank Sta=174.85,242.35
XS Rating Curve= 0 ,0
Exp/Cntr=0.3,0.1

Type RM Length L Ch R = 1 ,2824.744,421.39,434.89,443.48
XS GIS Cut Line= 4
1540073.35701799736755.6485900281539899.39218132736973.822600842
1539863.85723634737023.3844978061539782.85149598737240.838440865
#Sta/Elev= 30
       0  207.35   17.91  196.39   26.86  191.82   53.72  181.17  143.25  152.17
   170.1   142.3  205.92   127.9  223.82  124.23  241.73  121.93  259.63  118.38
  268.59  111.28  279.04  107.98   347.5  108.08  354.97  112.28  362.44  123.72
   369.9  125.87  384.84  128.56  407.25  135.47  414.72  138.37  429.66   145.1
   444.6  150.86  459.54  157.67  467.01  161.33  489.42  174.12  496.89  176.99
  504.36  178.94   519.3  181.16  526.77  184.31  541.71  193.48  572.08  206.59
#Mann= 3 , 0 , 0
       0      .1       0  279.04    .045       0   347.5      .1       0
Bank Sta=279.04,347.5
XS Rating Curve= 0 ,0
Exp/Cntr=0.3,0.1

Type RM Length L Ch R = 1 ,2389.854,253.84,309.09,357.83
XS GIS Cut Line= 5
1539852.23825602 736507.085960061539585.18845716736695.153821692
1539481.38901263736803.6289169491539398.34774627736944.746646166
1539384.35701039737046.154111996
#Sta/Elev= 30
       0  200.15   25.68  192.63   68.49  182.59   94.18  175.79  128.42   165.9
  154.11  157.52  179.79  147.21  196.92  138.84  205.48  133.56  239.73     110
  248.29  107.99  256.85  107.98  396.62108.8027     477109.2758  493.01  109.37
  501.13  113.85   525.5  124.88   598.6   155.8  606.72   160.2  614.84  165.75
  622.96  170.03  631.08  172.68  647.57  175.31  654.63   178.2  668.77  186.49
  675.83  189.75  689.97  192.96   704.1  195.41  718.23  199.69  742.87  205.67
#Mann= 3 , 0 , 0
       0      .1       0  396.62    .045       0     477      .1       0
Bank Sta=396.62,477
XS Rating Curve= 0 ,0
Exp/Cntr=0.3,0.1

Type RM Length L Ch R = 1 ,2080.763,213.92,243.26,252.77
BEGIN DESCRIPTION:
Channel estimated from photos and bridge surveys (2-ft depth assumed)
END DESCRIPTION:
XS GIS Cut Line= 3
1539592.72696812736388.9813338071539406.57860212 736517.47909674
1539079.03734849736570.188423753
#Sta/Elev= 30
       0  183.78   17.01  182.46   25.52  180.84   85.06  161.02  110.58  153.79
  119.08  150.53  127.59  146.47  136.09  141.57   153.1  130.37  178.62     115
  187.13  110.67  195.63  108.43     225     106     323     106  353.81   108.2
  389.26  110.07  396.35  112.11  410.53  125.51  417.62  133.66  424.71  139.94
   431.8  145.57  453.07  160.51  460.16  164.42  467.25  166.88  474.34  168.41
  509.79  172.54  516.88  174.14  523.97  176.47  531.06  180.87  557.95  202.15
#Mann= 3 , 0 , 0
       0      .1       0  195.63     .04       0  353.81      .1       0
Bank Sta=195.63,353.81
XS Rating Curve= 0 ,0
Exp/Cntr=0.3,0.1

Type RM Length L Ch R = 1 ,1837.503,415.77,365.17,285.61
BEGIN DESCRIPTION:
Channel estimated from photos and bridge surveys (2-ft depth assumed)
END DESCRIPTION:
XS GIS Cut Line= 3
1539494.48083448736283.6965639291539159.25050518736291.636229619
1539089.28857444736294.794280306
#Sta/Elev= 30
       0  166.78       7  162.21   21.01  151.38   28.01   146.4   35.01  141.69
   42.01   137.3   56.02  129.19   70.02  121.61   77.02  118.15   91.03  111.81
   98.03  109.25  105.03  108.13     135     106     208     106  238.07  108.22
  266.07  108.98  273.08  109.68  280.08  111.88  287.08  115.36  294.08   119.7
  301.08   125.1  315.09  137.11  322.09  142.28  342.33  155.58  349.34   159.7
  356.35  162.98  384.37  172.42  391.38  175.76  398.39     181  405.36  186.51
#Mann= 3 , 0 , 0
       0      .1       0  105.03     .04       0  238.07      .1       0
Bank Sta=105.03,238.07
XS Rating Curve= 0 ,0
Exp/Cntr=0.3,0.1

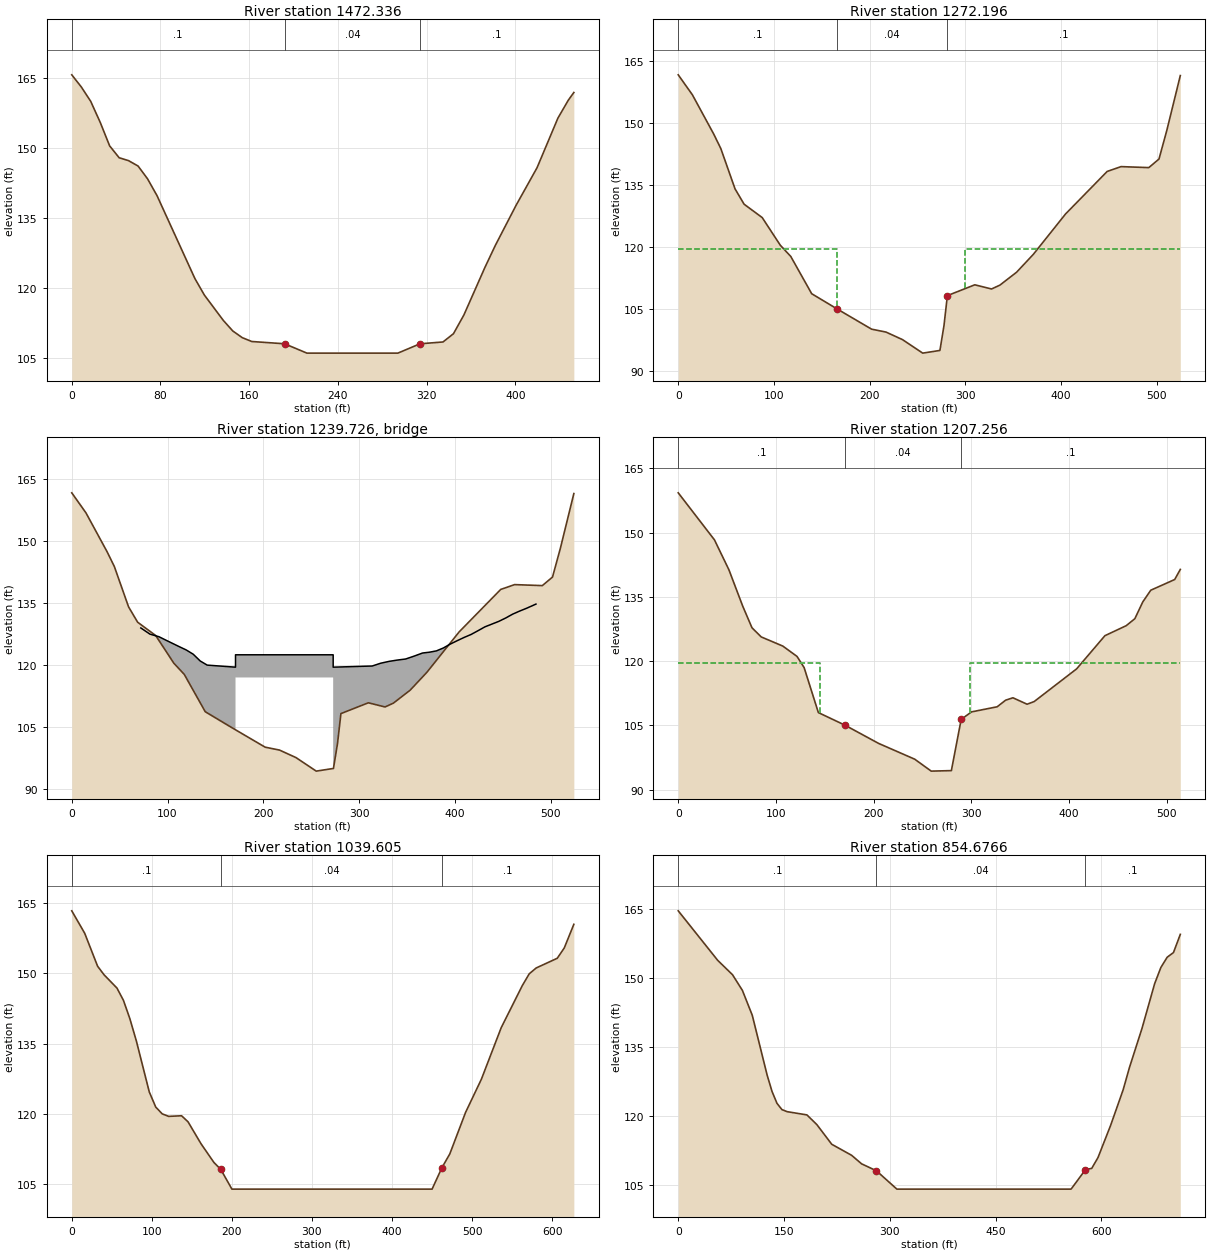
Type RM Length L Ch R = 1 ,1472.336,223.09,200.14,187.99
BEGIN DESCRIPTION:
Channel estimated from photos and bridge surveys (2-ft depth assumed)
END DESCRIPTION:
XS GIS Cut Line= 3
1539395.35704055735818.9368886351539252.28213044735918.995812699
1539066.19123428736125.659571737
#Sta/Elev= 30
       0  165.62    8.54  163.04   17.08  159.94   25.63  155.45   34.17  150.39
   42.71  147.86   51.25  147.23   59.79  146.08   68.34  143.34   76.88  139.73
  111.05  121.96  119.59  118.43  136.67     113  145.21  110.74  153.76  109.31
   162.3  108.49     192     108     212     106     294     106     314     108
  334.73  108.39  344.15  110.16  353.57  114.18   372.4   124.3  381.82  129.04
  400.66  137.69   419.5  145.71  438.34  156.35  447.76  160.21  452.69  161.83
#Mann= 3 , 0 , 0
       0      .1       0     192     .04       0     314      .1       0
Bank Sta=192,314
XS Rating Curve= 0 ,0
Exp/Cntr=0.5,0.3

Type RM Length L Ch R = 1 ,1272.196,60.15,64.94,75.95
BEGIN DESCRIPTION:
Elevations below 108 were obtained from bridge survey info.
END DESCRIPTION:
XS GIS Cut Line= 6
1539130.84737037735684.7442005281539058.91690183 735842.70860137
1538990.45528154735935.6937871431538912.12842169735994.177842483
1538803.86023068736023.1364975271538792.39682548736042.242172837
#Sta/Elev= 30
       0  161.76   14.83   156.9   37.07   147.4   44.49  143.88   59.32  134.12
   68.79   130.4   87.69  127.16  106.59  120.46  117.52  117.74  139.39   108.7
     166     105  201.94  100.11     217    99.4  234.19   97.58  255.33    94.3
   273.3   94.95  277.53  100.95  281.11  108.24  309.74  110.86  327.21  109.85
  335.94  110.78  353.42  113.92  370.89  118.25  404.51  128.03  447.99  138.34
  462.48  139.51  491.46  139.27  502.09  141.34  510.25  148.27  524.37  161.58
#Mann= 3 , 0 , 0
       0      .1       0     166     .04       0  281.11      .1       0
#XS Ineff= 2 , 0
       0     166   119.5     300       0   119.5
Permanent Ineff=
       F       F
Bank Sta=166,281.11
XS Rating Curve= 0 ,0
Exp/Cntr=0.5,0.3

Type RM Length L Ch R = 3 ,1239.726,,,
BEGIN DESCRIPTION:
Bell Manor Road, MDE Bridge #: CE040507PF-4
CE0002
Top of road obtained from DEM.
Opening from MDE2 bridge/culvert surveys.
END DESCRIPTION:
Bridge Culvert--1,0,-1,-1, 0
Deck Dist Width WeirC Skew NumUp NumDn MinLoCord MaxHiCord MaxSubmerge Is_Ogee
22.7,19.5,2.6,0, 36, 36, , , 0.95, 0, 1.5,1.5,,
   72.14    81.6   91.05   100.5  112.27  119.56  126.85  134.14  141.43     171
     171     273     273  313.76   322.5  331.23  339.97   348.7  357.44  366.34
  373.59  380.84  388.08  395.33  402.57  409.82  417.07  424.31  431.56   438.8
  446.05   453.3  460.54  467.79  475.03  484.79
     129  127.51  126.88   125.8  124.47  123.67  122.64     121     120   119.5
   122.5   122.5   119.5  119.78  120.45   120.9  121.22  121.48  122.17  122.93
  123.13  123.45  124.15   125.1  125.92  126.71  127.43  128.34  129.28  129.94
  130.61  131.43  132.36   133.1  133.78  134.79
                                                                                
     117     117
                                                                                
                                                
   72.14    81.6   91.05   100.5  112.27  119.56  126.85  134.14  141.43     171
     171     273     273  313.76   322.5  331.23  339.97   348.7  357.44  366.34
  373.59  380.84  388.08  395.33  402.57  409.82  417.07  424.31  431.56   438.8
  446.05   453.3  460.54  467.79  475.03  484.79
     129  127.51  126.88   125.8  124.47  123.67  122.64     121     120   119.5
   122.5   122.5   119.5  119.78  120.45   120.9  121.22  121.48  122.17  122.93
  123.13  123.45  124.15   125.1  125.92  126.71  127.43  128.34  129.28  129.94
  130.61  131.43  132.36   133.1  133.78  134.79
                                                                                
     117     117
                                                                                
                                                
BR Coef=-1 , 0 , 0 ,, 0 ,,,0.8,0,,0,
WSPro=,,,, 1 ,,,, 0 ,,,, 0 ,,,,-1 ,-1 ,-1 , 0 , 0 , 0 , 0 , 0
BC Design=,, 0 ,, 0 ,,,,,,
BC Use User HTab Curves=0
BC User HTab FreeFlow(D)= 0

Type RM Length L Ch R = 1 ,1207.256,130.09,167.65,225.6
BEGIN DESCRIPTION:
Elevations below 108 were obtained from bridge survey info.
END DESCRIPTION:
XS GIS Cut Line= 6
1539074.20186542735664.9632305651539004.26593706735815.738038838
1538947.42011973735892.9465369881538885.47745991735939.197056323
1538764.90220661735971.4474997221538740.94724996736011.372427478
#Sta/Elev= 30
       0  159.31   37.07  148.33    51.9  141.33   66.05  132.83    75.5  127.79
   84.95  125.65  107.02  123.52   121.6   121.1  128.89  118.49  143.46  107.98
     171     105  205.11  100.78  242.11   97.09  259.03    94.3  279.65   94.42
  289.69  106.39  300.31  108.14  326.52  109.33  335.25  110.88  342.67  111.43
  357.16  109.93  364.41  110.55  407.89  118.19  436.87  125.94  458.61  128.27
  467.48   129.9  475.65  133.84  483.81  136.56   508.3  139.06  514.04  141.42
#Mann= 3 , 0 , 0
       0      .1       0     171     .04       0  289.69      .1       0
#XS Ineff= 2 , 0
       0     145   119.5     299       0   119.5
Permanent Ineff=
       F       F
Bank Sta=171,289.69
XS Rating Curve= 0 ,0
Exp/Cntr=0.5,0.3

Type RM Length L Ch R = 1 ,1039.605,155.03,184.93,207.92
BEGIN DESCRIPTION:
Channel estimated from photos and bridge surveys (4-ft depth assumed)
END DESCRIPTION:
XS GIS Cut Line= 4
1539057.96044704735635.3859150261538896.48379217735727.917481288
 1538649.7329488735976.482669145 1538577.1591713736030.913002223
#Sta/Elev= 30
       0  163.25   16.14  158.48   32.27  151.46   40.34  149.63   56.47   146.8
   64.54  144.19   72.61  140.26   80.68  135.54   96.81  124.69  104.88  121.47
  112.95  120.03  121.02  119.49  137.15  119.62  145.22  118.33  161.36  113.68
  177.49  109.69  186.11   108.2     200     104     450     104  462.29  108.55
  472.15   111.5  491.88  120.35   511.6   127.4  536.35  138.37   562.6   147.3
  571.35  149.84   580.1  151.09  606.35  153.15   615.1  155.34  627.07  160.38
#Mann= 3 , 0 , 0
       0      .1       0  186.11     .04       0  462.29      .1       0
Bank Sta=186.11,462.29
XS Rating Curve= 0 ,0
Exp/Cntr=0.3,0.1

Type RM Length L Ch R = 1 ,854.6766,199.52,166.02,171.35
BEGIN DESCRIPTION:
Channel estimated from photos and bridge surveys (4-ft depth assumed)
END DESCRIPTION:
XS GIS Cut Line= 4
1539062.45071377735604.7920885681538908.15424208735603.856958449
1538762.27394164735619.754170686 1538439.6540463735874.109566405
#Sta/Elev= 30
       0  164.56      56  153.78      77  150.65      91  147.24     105  141.82
     126  128.84     133  125.25     140  122.67     147  121.31   154.3  120.86
  182.47  120.15  196.55  118.04  217.67  113.76  245.84  111.36  259.92  109.51
  281.05  107.99     310     104     557     104  577.37  108.23  586.29  108.52
   595.2  110.88  613.03  117.86  630.86  125.63  639.77  130.47   657.6     139
  675.43  148.69  684.34  152.24  693.25  154.46  702.17  155.48  711.87  159.44
#Mann= 3 , 0 , 0
       0      .1       0  281.05     .04       0  577.37      .1       0
Bank Sta=281.05,577.37
XS Rating Curve= 0 ,0
Exp/Cntr=0.3,0.1

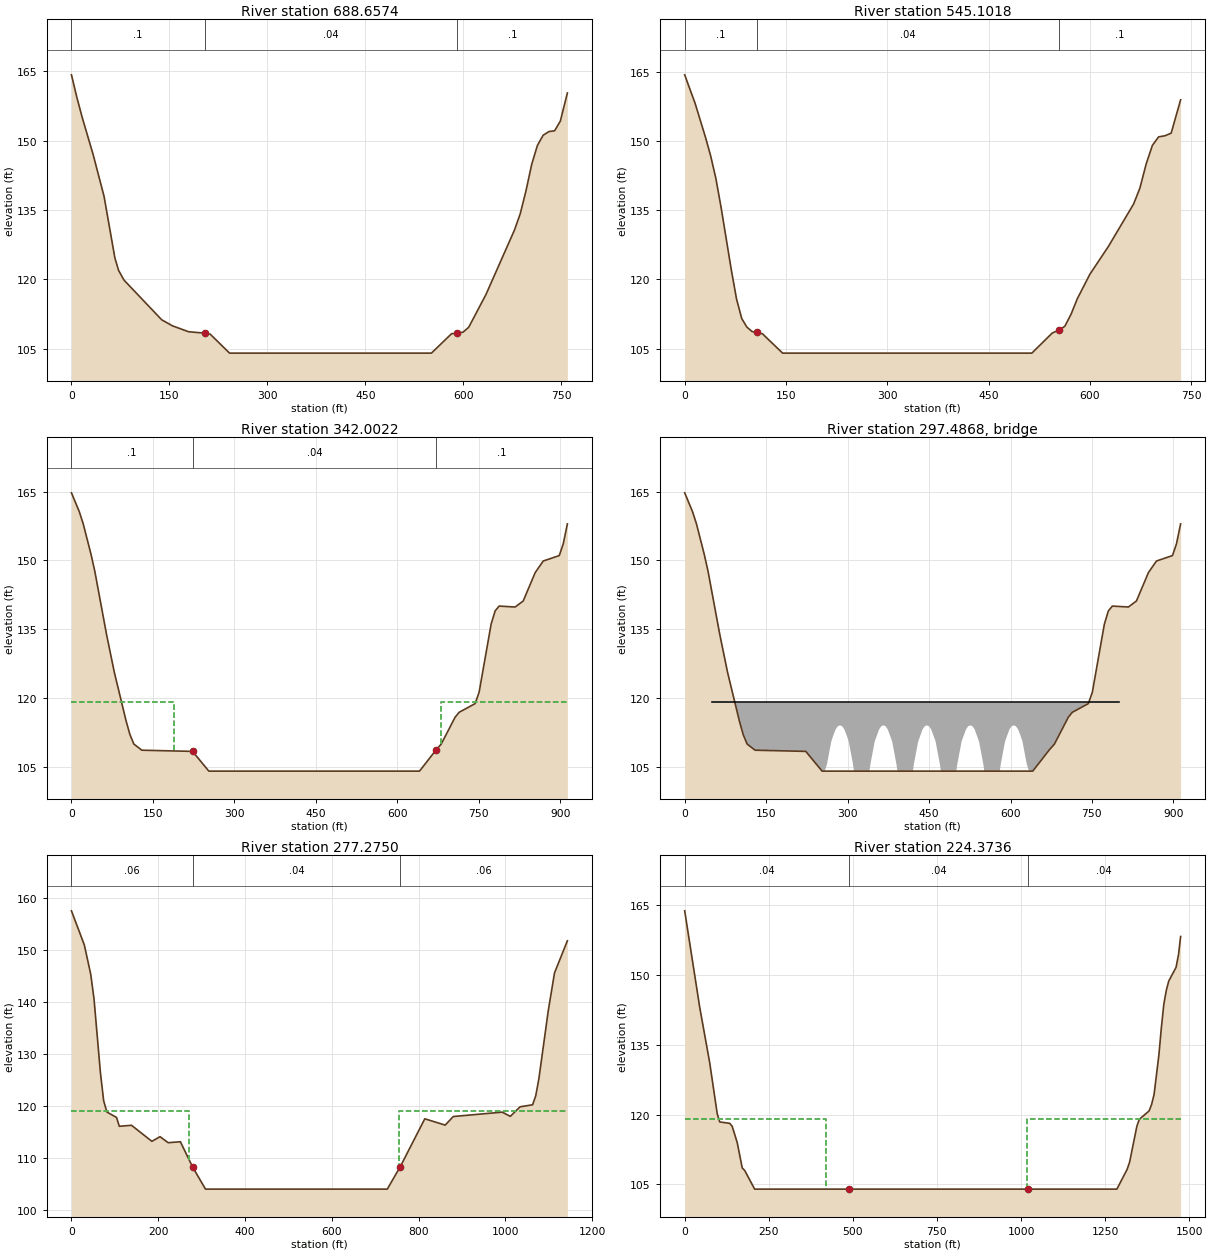
Type RM Length L Ch R = 1 ,688.6574,138.73,143.56,140.99
BEGIN DESCRIPTION:
Channel estimated from photos and bridge surveys (4-ft depth assumed)
END DESCRIPTION:
XS GIS Cut Line= 4
1538893.26677594735304.1961566061538854.34578903735364.950867921
 1538704.4828307735458.2600547371538296.86251713735765.496261239
#Sta/Elev= 30
       0  164.27    8.31  159.36   16.63  154.96   33.25  146.97   49.88  137.96
   66.51   124.6   72.15  121.92    80.4  119.82  138.12  111.22  154.61  109.91
  179.35  108.63  204.09  108.33  212.33  108.12     242     104     551     104
  581.79   108.2  590.55  108.34  599.32  108.53  608.08   109.6  634.38  116.66
  678.21  130.68  686.97  134.19  695.74  139.15  704.51  144.89  713.27  148.99
  722.04  151.18   730.8  151.98  739.57  152.15  748.33  154.25  759.13  160.34
#Mann= 3 , 0 , 0
       0      .1       0  204.09     .04       0  590.55      .1       0
Bank Sta=204.09,590.55
XS Rating Curve= 0 ,0
Exp/Cntr=0.3,0.1

Type RM Length L Ch R = 1 ,545.1018,274.5,203.1,167.86
BEGIN DESCRIPTION:
Channel estimated from photos and bridge surveys (4-ft depth assumed)
END DESCRIPTION:
XS GIS Cut Line= 4
1538802.13470897735251.9850765471538648.34934594735321.283419147
1538370.20668319735530.1277392951538205.60423797735672.717010766
#Sta/Elev= 30
       0  164.35   15.36   158.2   30.71  150.85   38.39  146.81   46.07  141.95
   53.75  135.72    69.1  121.98   76.78  115.73   84.46   111.5   92.13  109.64
   99.81  108.68  107.49  108.48  115.17  108.19     145     104     514     104
  544.28  108.37  553.54  108.94   562.8  109.82  572.07  112.44  581.33   115.8
  599.85  121.08  627.63   127.2  664.68  136.34  673.94  139.77   683.2  144.99
  692.46  149.05  701.72   150.9  710.98  151.13  720.25  151.69  734.27  158.93
#Mann= 3 , 0 , 0
       0      .1       0  107.49     .04       0  553.54      .1       0
Bank Sta=107.49,553.54
XS Rating Curve= 0 ,0
Exp/Cntr=0.5,0.3

Type RM Length L Ch R = 1 ,342.0022,74.48,64.73,65.85
BEGIN DESCRIPTION:
Channel estimated from photos and bridge surveys (4-ft depth assumed)
END DESCRIPTION:
XS GIS Cut Line= 4
1538723.28708823734980.2269611951538606.05367735735006.870918199
1538217.77200857735446.0922842031538152.37024184 735642.29758437
#Sta/Elev= 30
       0  164.77   14.36  160.68   21.54  158.05   35.89   151.4   43.07   147.6
   64.61  133.85   78.96  125.57   100.5  115.02  107.68  111.99  114.86  109.92
  129.57  108.57     223  108.31     253     104     641     104  671.46  108.64
  680.81  109.88  706.46  115.76  713.84  116.84  743.36  118.74  750.74  121.24
  772.87  136.11  780.25  138.99  787.63  140.04  817.14  139.84   831.9  141.15
  854.04  147.36  868.79  149.88  898.31  151.07  905.69  153.65  913.28  157.99
#Mann= 3 , 0 , 0
       0      .1       0     223     .04       0  671.46      .1       0
#XS Ineff= 2 , 0
       0     189     119     681       0     119
Permanent Ineff=
       F       F
Bank Sta=223,671.46
XS Rating Curve= 0 ,0
Exp/Cntr=0.5,0.3

Type RM Length L Ch R = 3 ,297.4868,,,
BEGIN DESCRIPTION:
Conrail Railroad Road, MDE Bridge #: CE040507FS-7
Top of road obtained from DEM.
Opening from MDE2 bridge/culvert photo.
END DESCRIPTION:
Bridge Culvert--1,0,-1,-1, 0
Deck Dist Width WeirC Skew NumUp NumDn MinLoCord MaxHiCord MaxSubmerge Is_Ogee
14.5,35,2.6,0, 60, 60, , , 0.95, 0, 2,2,,
      50     258     262     270     274     278     282     286     290     294
     298     302     310  311.71  340.29     342     350     358     362     366
     370     374     382     390  391.71  420.29     422     430     438     442
     446     450     454     462     470  471.71  500.29     502     510     518
     522     526     530     534     542     550  551.71  580.29     582     590
     598     602     606     610     614     618     622     630     634     800
     119     119     119     119     119     119     119     119     119     119
     119     119     119     119     119     119     119     119     119     119
     119     119     119     119     119     119     119     119     119     119
     119     119     119     119     119     119     119     119     119     119
     119     119     119     119     119     119     119     119     119     119
     119     119     119     119     119     119     119     119     119     119
             102   105.5   110.5   111.9   113.1   113.8     114   113.8   113.1
   111.9   110.5   105.5  104.01  104.01   105.5   110.5   113.1   113.8     114
   113.8   113.1   110.5   105.5  104.01  104.01   105.5   110.5   113.1   113.8
     114   113.8   113.1   110.5   105.5  104.01  104.01   105.5   110.5   113.1
   113.8     114   113.8   113.1   110.5   105.5  104.01  104.01   105.5   110.5
   113.1   113.8     114   113.8   113.1   111.9   110.5   105.5     102
      50     332     336     344     348     352     356     360     364     368
     372     376     384  385.71  414.29     416     424     432     436     440
     444     448     456     464  465.71  494.29     496     504     512     516
     520     524     528     536     544  545.71  574.29     576     584     592
     596     600     604     608     616     624  625.71  654.29     656     664
     672     676     680     684     688     692     696     704     708    1100
     119     119     119     119     119     119     119     119     119     119
     119     119     119     119     119     119     119     119     119     119
     119     119     119     119     119     119     119     119     119     119
     119     119     119     119     119     119     119     119     119     119
     119     119     119     119     119     119     119     119     119     119
     119     119     119     119     119     119     119     119     119     119
             102   105.5   110.5   111.9   113.1   113.8     114   113.8   113.1
   111.9   110.5   105.5  104.01  104.01   105.5   110.5   113.1   113.8     114
   113.8   113.1   110.5   105.5  104.01  104.01   105.5   110.5   113.1   113.8
     114   113.8   113.1   110.5   105.5  104.01  104.01   105.5   110.5   113.1
   113.8     114   113.8   113.1   110.5   105.5  104.01  104.01   105.5   110.5
   113.1   113.8     114   113.8   113.1   111.9   110.5   105.5     102
Pier Skew, UpSta & Num, DnSta & Num=  ,326, 2 ,400, 2 , 0 , 0 , 0 ,,
   28.58   28.58
     103  104.01
   28.58   28.58
     103  104.01
Pier Skew, UpSta & Num, DnSta & Num=  ,406, 2 ,480, 2 , 0 , 0 , 0 ,,
   28.58   28.58
     103  104.01
   28.58   28.58
     103  104.01
Pier Skew, UpSta & Num, DnSta & Num=  ,486, 2 ,560, 2 , 0 , 0 , 0 ,,
   28.58   28.58
     103  104.01
   28.58   28.58
     103  104.01
Pier Skew, UpSta & Num, DnSta & Num=  ,566, 2 ,640, 2 , 0 , 0 , 0 ,,
   28.58   28.58
     103  104.01
   28.58   28.58
     103  104.01
BR Coef=-1 , 1 , 0 ,, 0 ,,,0.8,0,0.5,0,
WSPro=,,,, 1 ,,,, 0 ,,,, 0 ,,,,-1 ,-1 ,-1 , 0 , 0 , 0 , 0 , 0
BC Design=,, 0 ,, 0 ,,,,,,
BC Use User HTab Curves=0
BC User HTab FreeFlow(D)= 0

Type RM Length L Ch R = 1 ,277.2750,59.61,52.9,79.77
BEGIN DESCRIPTION:
Channel estimated from photos and bridge surveys (4-ft depth assumed)
END DESCRIPTION:
XS GIS Cut Line= 4
  1538731.013034734927.1576500541538627.01972148734890.430654392
1538020.88733438735568.4240976571538050.83494061735688.214522496
#Sta/Elev= 30
       0  157.58   29.69  151.01   44.54  145.32   51.97  140.65   66.81  126.37
   74.24  121.02   81.66  118.84  103.93   117.8  110.29   116.1  138.46  116.29
   185.4   113.2  204.18   114.1  222.96  112.94  251.13  113.12   279.3  108.26
     309     104     728     104  758.17  108.35   814.5  117.54  861.45  116.33
  880.23  117.98   992.9  118.82 1011.68  118.01 1034.15  119.85 1063.02  120.24
 1070.23  121.97 1077.45  125.23 1099.09  138.33 1113.52  145.63  1143.2  151.81
#Mann= 3 , 0 , 0
       0     .06       0   279.3     .04       0  758.17     .06       0
#XS Ineff= 2 , 0
       0     272     119     755       0     119
Permanent Ineff=
       F       F
Bank Sta=279.3,758.17
XS Rating Curve= 0 ,0
Exp/Cntr=0.5,0.3

Type RM Length L Ch R = 1 ,224.3736,177.23,224.37,200.91
BEGIN DESCRIPTION:
Channel estimated from photos and bridge surveys (4-ft depth assumed)
END DESCRIPTION:
XS GIS Cut Line= 4
1538849.04656543734823.5604939161538671.06493251734759.614997029
1537942.47619976735579.9377602931537994.18922465735760.933347285
#Sta/Elev= 30
       0  163.85   44.63  143.12   74.38  131.18    96.7  120.24  104.13  118.45
  133.89  118.15  141.32  117.49   156.2     114  171.08  108.56  178.51     108
     208     104     490     104    1020     104    1285     104 1315.41  108.24
 1322.69  109.76 1344.53  117.55 1351.81  119.02 1380.93  120.83 1388.21  122.21
 1395.49  124.31 1402.77  128.61 1410.05  132.96 1417.33  138.77 1424.61  143.78
 1431.89  146.72 1439.17  148.74 1461.01   151.7 1468.29  154.44 1474.52  158.33
#Mann= 3 , 0 , 0
       0     .04       0     490     .04       0    1020     .04       0
#XS Ineff= 2 , 0
       0     421     119    1019       0     119
Permanent Ineff=
       F       F
Bank Sta=490,1020
XS Rating Curve= 0 ,0
Exp/Cntr=0.3,0.1
Stream Node=Conowingo_Creek ,Reach1          , 0 , 0 ,Upstream end
Stream Node=Conowingo_Creek ,Reach1          , 0 , 1 ,Downstream end

Chan Stop Cuts=-1
Use User Specified Reach Order=0
User Specified Reach Order=Conowingo_Creek ,Reach1