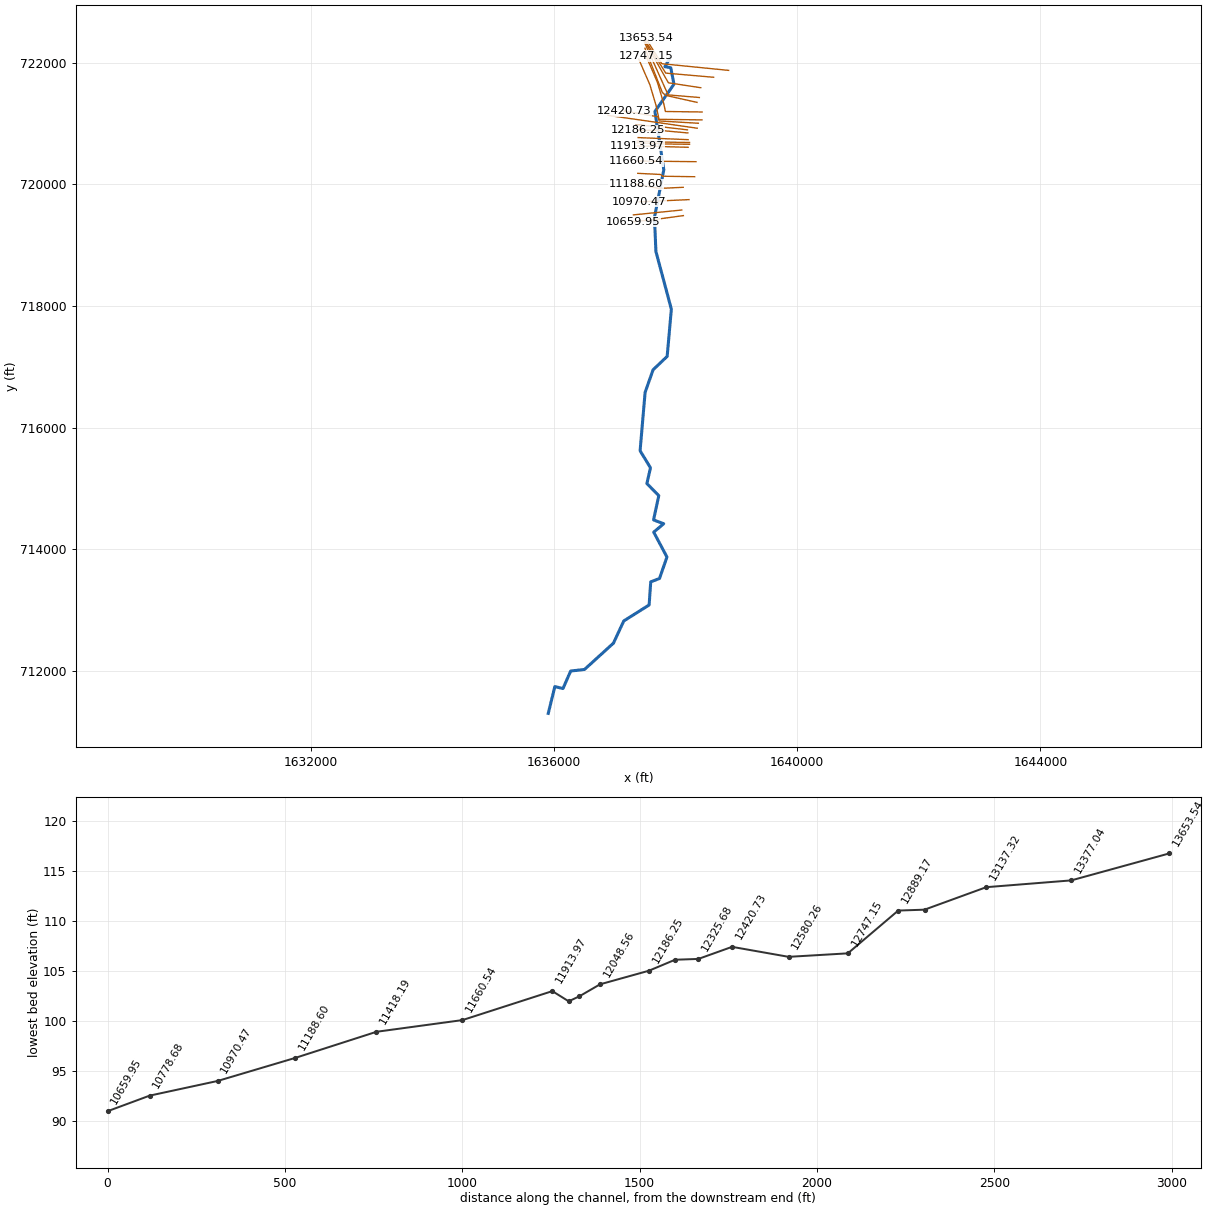
--- Dogwood.prj (project) ---

Proj Title=Dogwood Run
Current Plan=p10
Default Exp/Contr=0.3,0.1
English Units
Geom File=g13
Flow File=f01
Flow File=f02
Plan File=p10
Plan File=p11
Y Axis Title=Elevation
X Axis Title(PF)=Main Channel Distance
X Axis Title(XS)=Station
BEGIN DESCRIPTION:
& RDogwood Run- Georeferenced HEC-RAS model.  There was an existing detailed model between the mouth of Dogwood Run and the 1st bridge ( Blue Ball Road.)   The remaining portion of the stream is an approximate method stream.  Projection:  MD Stateplane.  Horizontal datum:  NAD83.  Vertrial datum: NAVD88.  Units:Feet.  Created by: Ann Banitt, USACE- St Paul District as part of FEMA Map Modernization study for Cecil County, MD.
END DESCRIPTION:
DSS File=dss
DSS Export Rating Curves= 0
DSS Export Rating Curve Sorted= 0
DSS Export Volume Flow Curves= 0
DXF OffsetX= 0
DXF OffsetY= 0
DXF ScaleX= 1
DXF ScaleY= 10

--- Dogwood.p10 (plan) ---

Plan Title=Dogwood Run _ Frequency Profiles
Program Version=4.00
Short Identifier=Dogwood Run
Geom File=g13
Flow File=f01
Subcritical Flow
K Sum by GR= 0
Std Step Tol= 0.01
Critical Tol= 0.01
Num of Std Step Trials= 20
Max Error Tol= 0.3
Flow Tol Ratio= 0.001
Split Flow NTrial= 30
Split Flow Tol= 0.02
Split Flow Ratio= 0.02
Log Output Level= 0
Friction Slope Method= 1
Unsteady Friction Slope Method= 2
Unsteady Bridges Friction Slope Method= 1
Secant Critical Depth
Global Vel Dist= 0 , 0 , 0
Global Log Level= 0
CheckData=True
Encroach Param=-1 ,0,0, 0
Computation Interval=1HOUR
Output Interval=1HOUR
Run HTab= 1
Run UNet= 0
Run PostProcess= 0
Run WQNet= 0
UNET Theta= 1
UNET Theta Warmup= 1
UNET ZTol= 0.02
UNET ZSATol= 0.05
UNET MxIter= 20
UNET MaxInSteps= 0
UNET DtIC= 0
UNET DtMin= 0
UNET MaxCRTS= 20
UNET WFStab= 2
UNET SFStab= 1
UNET WFX= 1
UNET SFX= 1
UNET DSS MLevel= 4
UNET DZMax Abort= 100
UNET Convert EG Bridges= 0
UNET Use Existing IB Tables=-1
UNET Froude Reduction=False
UNET Froude Limit= 1
UNET Froude Power= 10
UNET Time Slicing=0,0, 5
Instantaneous Interval=1HOUR
DSS File=dss
Write IC File= 0
Echo Input=False
Echo Output=False
Write Detailed= 0
Detailed Automatic Start=False, 10
WQ ULTIMATE=-1
WQ Max Comp Step=1HOUR
WQ Output Interval=15MIN
WQ Output Selected Increments= 0
WQ Output face flow=0
WQ Output face velocity=0
WQ Output face area=0
WQ Output face dispersion=0
WQ Output cell volume=0
WQ Output cell surface area=0
WQ Output cell length=0
WQ Output face conc=0
WQ Output face dconc_dx=0
WQ Output face adv mass=0
WQ Output face disp mass=0
WQ Output cell mass=0
WQ Output cell source sink=0
WQ Output MaxMinRange=-1
WQ Create Restart=0
WQ Fixed Restart=0
Sorting and Armoring Iterations= 10
XS Update Threshold= 0.02
Hydraulics Update Threshold= 0.02
Energy Slope Method= 0
Volume Change Method= 0
XS Weighting Method= 0
Number of US Weighted Cross Sections= 1
Number of DS Weighted Cross Sections= 1
Upstream XS Weight=0.25
Main XS Weight=0.5
Downstream XS Weight=0.25
Number of DS XS's Weighted with US Boundary= 1
Upstream Boundary Weight= 1
Weight of XSs Associated with US Boundary= 0
Number of US XS's Weighted with DS Boundary= 1
Downstream Boundary Weight= 0.5
Weight of XSs Associated with DS Boundary= 0.5
Sediment Output Level= 4
Output Increment= 10
Disregard all LS=0
Disregard all Conn=0
Disregard all Breaches=0
Disregard all Pumps=0

--- Dogwood.p11 (plan) ---

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Plan Title=Dogwood Run_Floodway
Short Identifier=Dogwood FW
Geom File=g13
Flow File=f02
Encroach Param=-1 ,0,0, 2
Encroach River=DogwoodRun
Encroach Reach=One
Encroach Node=1570.898
       1     760     925
Encroach Node=1495.409
       1  859.37  965.42
Encroach Node=1384.976
       1     955  980.54
Encroach Node=1207.973
       1     426  458.33
Encroach Node=1087.044
       1  510.03  536.65
Encroach Node=1046.3*
       1  528.01   556.1
Encroach Node=1005.55*
       1     546  575.55
Encroach Node=964.8134
       1  563.98     595
Encroach Node=836.7749
       1  634.83     665
Encroach Node=588.8409
       1  864.08  895.85
Encroach Node=186.0519
       1  958.49  990.87
WQ Output cell continuity=0
WQ Output face courant=0
WQ Output face peclet=0
WQ Output cell source sink temp=0
WQ Output cell source sink nsm=0
Mass or Volume Output= 0
Output Increment Type= 1
Profile and TS Output Increment= 10
XS Output Flag= 0
XS Output Increment= 10

--- Dogwood.f01 (steady flow) ---

Flow Title=Dogwood Run Frequency Profiles
Program Version=4.00
Number of Profiles= 5
Profile Names=Q10cur,Q50cur,Q100cur,Q500cur,Q100ult
River Rch & RM=DogwoodRun,One             ,13653.54
     254     575     782    1530     862
River Rch & RM=DogwoodRun,One             ,11660.54
     254     575     793    1610     894
River Rch & RM=DogwoodRun,One             ,9428.959
     279     643     887    1781    1002
River Rch & RM=DogwoodRun,One             ,7460.738
     298     703     972    1978    1114
River Rch & RM=DogwoodRun,One             ,4441.049
     326     777    1079    2194    1234
River Rch & RM=DogwoodRun,One             ,186.0519
     405    1022    1442    3010    1527
Boundary for River Rch & Prof#=DogwoodRun,One             , 1
Up Type= 0
Dn Type= 3
Dn Slope=0.0094
Boundary for River Rch & Prof#=DogwoodRun,One             , 2
Up Type= 0
Dn Type= 3
Dn Slope=0.0094
Boundary for River Rch & Prof#=DogwoodRun,One             , 3
Up Type= 0
Dn Type= 3
Dn Slope=0.0094
Boundary for River Rch & Prof#=DogwoodRun,One             , 4
Up Type= 0
Dn Type= 3
Dn Slope=0.0094
Boundary for River Rch & Prof#=DogwoodRun,One             , 5
Up Type= 0
Dn Type= 3
Dn Slope=0.0094
DSS Import GetInterval= 0
DSS Import GetPeak= 0
DSS Import FillOption= 0

--- Dogwood.f02 (steady flow) ---

Flow Title=Dogwood Run Floodway
Program Version=4.00
Number of Profiles= 2
Profile Names=Q100cur,Floodway
River Rch & RM=DogwoodRun,One             ,13653.54
     782     782
River Rch & RM=DogwoodRun,One             ,11660.54
     793     793
River Rch & RM=DogwoodRun,One             ,9428.959
     887     887
River Rch & RM=DogwoodRun,One             ,7460.738
     972     972
River Rch & RM=DogwoodRun,One             ,4441.049
    1079    1079
River Rch & RM=DogwoodRun,One             ,186.0519
    1442    1442
Boundary for River Rch & Prof#=DogwoodRun,One             , 1
Up Type= 0
Dn Type= 3
Dn Slope=0.0094
Boundary for River Rch & Prof#=DogwoodRun,One             , 2
Up Type= 0
Dn Type= 3
Dn Slope=0.0094
DSS Import GetInterval= 0
DSS Import GetPeak= 0
DSS Import FillOption= 0

--- Dogwood.g13 (geometry) ---

Geom Title=Dogwood Run- Effective FIS HEC2 Geom
Program Version=4.00

River Reach=DogwoodRun      ,One
Reach XY= 30
 1637906.0726155722072.6196752641637825.10858522721935.839533135
1637922.02007605 721917.438617171637974.15600465721647.865198031
1637661.09508741721198.882848099 1637807.4728989720240.948330462
1637653.58416593 719457.189434351637677.44288415718896.509554341
1637931.53823406 717948.12550199  1637862.347951717170.331285477
1637630.91838354716950.8310770991637499.69543289 716578.63507165
1637417.38285469 715619.514596061637587.97269058715339.174656063
1637529.09918344715079.9649203871637724.88492949714881.235027775
1637638.52329718  714481.81247821637805.35826869714419.004018337
1637641.46744373 714280.629130141637858.76914322713871.863480702
 1637737.0896799713518.7544499041637592.39833444713463.137769476
1637565.90101543713082.8521725091637148.97227387712820.290471703
1636979.03446835712454.7675736841636503.55479941712022.468720898
1636275.87413237711996.4620929661636148.78513929711708.426421463
1636015.68315464711740.6834686991635906.77645139711300.164445624

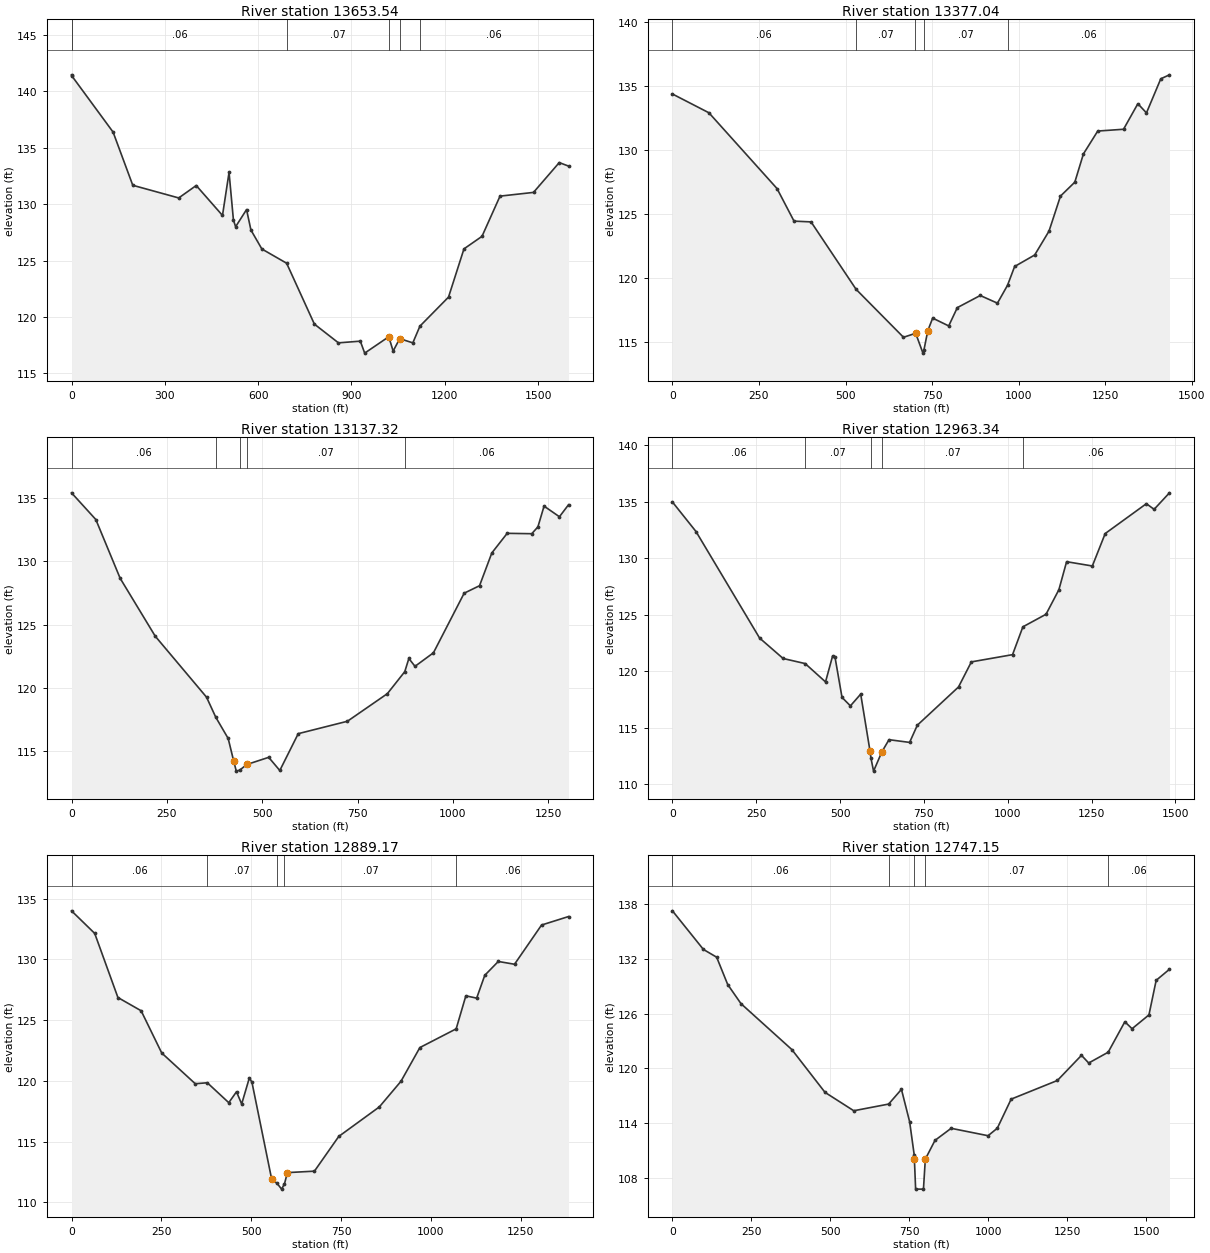
Type RM Length L Ch R = 1 ,13653.54,153.69,276.5,174.19
XS GIS Cut Line= 3
1638873.06511404721874.6961573361637774.00882687721984.538790092
1637510.36642215722401.800458238
#Sta/Elev= 30
       0  141.44    2.24   141.3  133.66  136.37  196.98  131.66  344.71  130.54
  400.99  131.64  485.41  128.99  506.51   132.8  520.58  128.59  527.62  127.99
  562.79  129.51  576.86   127.7  612.03  126.02  691.66  124.76  780.87  119.37
  858.25  117.71   928.6  117.86  942.67   116.8 1020.06  118.25 1034.12  116.98
 1055.23  118.08 1097.44  117.71 1120.27  119.19 1212.17  121.76 1261.85  126.03
 1319.81  127.14 1377.78   130.7 1485.42  131.03 1568.22  133.67  1598.1  133.36
#Mann= 6 ,-1 , 0
       0     .06       0    2.24     .06       0  691.66     .07       0
 1020.06    .045       0 1055.23     .07       0 1120.27     .06       0
Bank Sta=1020.06,1055.23
XS Rating Curve= 0 ,0
Exp/Cntr=0.3,0.1

Type RM Length L Ch R = 1 ,13377.04,195.08,239.72,159.53
XS GIS Cut Line= 3
1638626.40686968721761.4583944381637839.49178195721829.729566425
1637494.54270239722375.898942396
#Sta/Elev= 30
       0  134.38  105.39  132.91  302.13  126.98  351.31  124.43   400.5  124.37
  530.69  119.09   667.5  115.34  699.98  115.63  702.63  115.66  723.71   114.1
  726.54  114.34  737.76  115.86  751.81  116.84  798.15  116.23  822.99  117.66
  889.22  118.61   938.9  118.01  968.05  119.41  988.57  120.88 1046.53  121.78
 1087.92  123.65 1121.04  126.39 1162.44  127.48 1187.27  129.69 1228.67  131.48
 1303.18  131.62 1344.58  133.62 1369.42   132.9 1410.81  135.57 1435.85  135.88
#Mann= 5 ,-1 , 0
       0     .06       0  530.69     .07       0  699.98    .045       0
  726.54     .07       0  968.05     .06       0
Bank Sta=702.63,737.76
XS Rating Curve= 0 ,0
Exp/Cntr=0.3,0.1

Type RM Length L Ch R = 1 ,13137.32,198.08,173.98,106.43
XS GIS Cut Line= 3
1638414.51804505721589.6753333511637882.69685175721670.800600126
1637504.11227342722335.577091753
#Sta/Elev= 30
       0  135.41   63.73   133.3  127.46  128.66  219.51  124.08  354.05  119.26
  378.13  117.68   410.7     116  424.86  114.25  431.94  113.42  440.93   113.5
  460.26  113.96  461.26  113.96  516.91  114.51  546.03  113.47  594.36  116.38
  723.25  117.36  827.97  119.54  873.66  121.28  884.36  122.32  900.47   121.7
  948.81  122.77 1029.36  127.48 1069.64  128.07 1101.86  130.66 1142.14  132.21
 1206.58  132.18 1222.69  132.72  1238.8  134.36 1279.08  133.52 1302.99  134.47
#Mann= 5 ,-1 , 0
       0     .06       0  378.13     .07       0  440.93    .045       0
  461.26     .07       0  873.66     .06       0
Bank Sta=424.86,460.26
XS Rating Curve= 0 ,0
Exp/Cntr=0.3,0.1

Type RM Length L Ch R = 1 ,12963.34,67.39,74.17,80.8
XS GIS Cut Line= 3
1638392.11395937721428.7392602411637878.47461727721471.542538747
1637481.83090314722353.290075943
#Sta/Elev= 30
       0  134.97   70.24  132.36   259.9  122.94  330.14  121.13  395.92  120.68
  456.58  119.06  477.65  121.35  484.67  121.28  505.75  117.69  530.77  116.94
  561.47  117.98  589.17  112.96  592.18   112.3  599.85  111.17  624.67  112.88
  645.91  113.95  707.31  113.71  730.34  115.23  853.15  118.61  891.53  120.83
 1014.34  121.47 1045.15  123.93 1114.12  125.04  1152.5  127.21 1175.53  129.69
 1252.28  129.31 1290.66  132.18 1413.47  134.82  1436.5  134.32 1482.28  135.78
#Mann= 5 ,-1 , 0
       0     .06       0  395.92     .07       0  592.18    .045       0
  624.67     .07       0 1045.15     .06       0
Bank Sta=589.17,624.67
XS Rating Curve= 0 ,0
Exp/Cntr=0.3,0.1

Type RM Length L Ch R = 1 ,12889.17,120.32,142.02,66.72
XS GIS Cut Line= 4
1638353.67409498721348.5530126541637837.62725905721463.480473921
 1637783.5437479 721510.803546191637497.35183457 722238.67746757
#Sta/Elev= 30
       0     134   64.54  132.14  129.09  126.86  193.63  125.77     251  122.29
  344.23  119.76  377.75  119.84  437.46   118.2  458.98   119.1  473.32  118.09
  494.83  120.25  502.01  119.87  556.59  111.93  571.87  111.55   584.5  111.08
  592.47  111.52  600.55  112.44  675.77  112.56  743.47  115.42  856.29  117.85
  916.46  119.96  969.12  122.74 1070.05  124.28 1096.98     127 1127.07  126.81
 1149.64  128.69 1187.24  129.83 1232.37   129.6 1307.59  132.83 1382.67  133.53
#Mann= 5 ,-1 , 0
       0     .06       0  377.75     .07       0  571.87    .045       0
  592.47     .07       0 1070.05     .06       0
Bank Sta=556.59,600.55
XS Rating Curve= 0 ,0
Exp/Cntr=0.5,0.3

Type RM Length L Ch R = 1 ,12747.15,320.66,166.89,218.45
BEGIN DESCRIPTION:
Underwater portion adjusted as per bridge inspection survey.
END DESCRIPTION:
XS GIS Cut Line= 5
1638437.21752378721190.5493713771637833.94284196721198.738620445
1637806.37375996 721328.723640771637701.02016582721681.335670128
1637514.66651009722111.940672114
#Sta/Elev= 30
       0  137.23   98.01  133.01  140.01  132.16  175.02  129.17  217.02  127.08
  378.03  122.06  483.04  117.38  574.05  115.37  684.44   116.1  724.98  117.71
  750.82  114.18  765.43  110.54  765.98  110.08  769.88   106.8  794.65   106.8
  800.58  110.08  831.18  112.13  882.32  113.45  999.21  112.64 1028.44  113.46
 1072.27  116.64 1218.63  118.68 1294.91  121.43 1317.79  120.59 1379.42  121.77
  1432.2   125.1 1455.08  124.34 1508.48  125.85 1531.36  129.63 1573.42  130.84
#Mann= 5 ,-1 , 0
       0     .06       0  684.44     .07       0  765.43    .045       0
  800.58     .07       0 1379.42     .06       0
#XS Ineff= 2 ,-1
       0  706.43  113.08  900.61 1573.42  113.08
Permanent Ineff=
       F       F
Bank Sta=765.98,800.58
XS Rating Curve= 0 ,0
Exp/Cntr=0.5,0.3

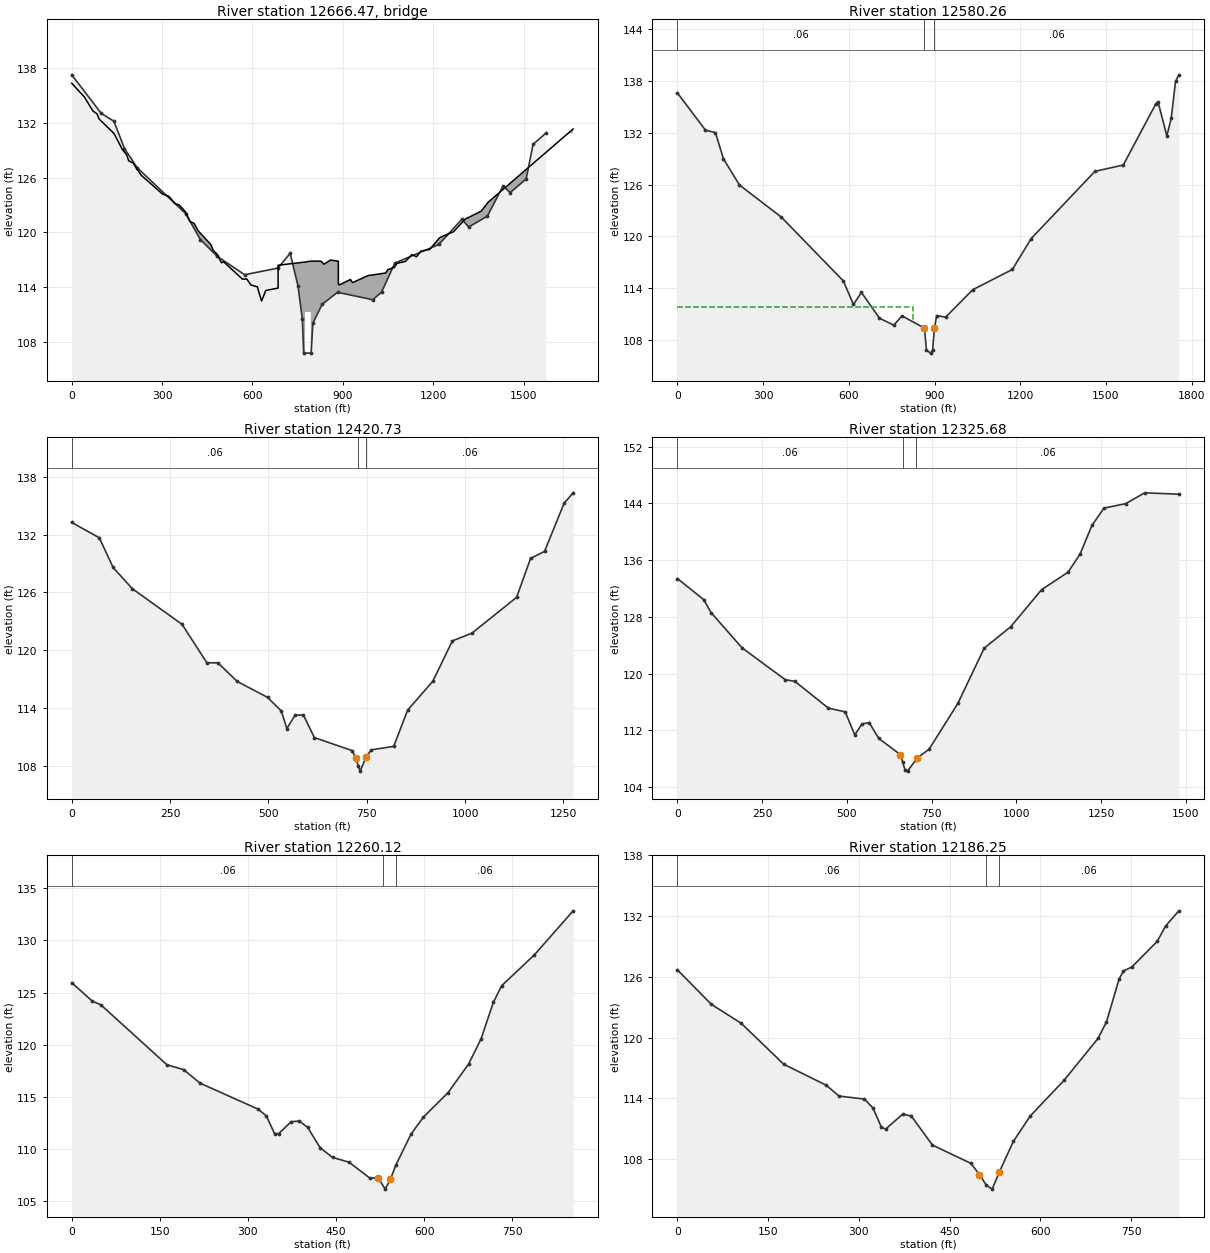
Type RM Length L Ch R = 3 ,12666.47,,,
BEGIN DESCRIPTION:
CE050807PF-3  Singerly Road.  Top of road taken from LIDAR. Bridge Inspection indicates bridge has opening of 19' wide x 4.5' high.  Deck thickness is 3'.  Assume top of rd at 114.29 from Lidar. Railing coded as 2.5' high as bridge inspection notes.
END DESCRIPTION:
Bridge Culvert--1,0,-1,-1, 0
Deck Dist Width WeirC Skew NumUp NumDn MinLoCord MaxHiCord MaxSubmerge Is_Ogee
50,45,2.6,0, 60, 60, , , 0.95, 0, 0,0,,
       0      42   70.01   84.01   91.01  140.01  168.02  182.02  189.02  203.02
  231.02  301.03  322.03  343.03  357.03  378.03  392.04  406.04  420.04  462.04
  469.04  483.04  497.05  504.05  567.05  581.05  595.05  616.06  630.06  644.06
  684.99     685 774.499   774.5   793.5  793.51     827  837.43  859.35     885
  885.01  888.57   925.1   932.4  983.54 1041.99  1049.3 1071.21 1078.52 1107.74
 1129.66 1144.27 1158.88 1188.11 1221.84  1267.6 1305.74 1359.13 1382.01 1664.31
  136.31  134.81  133.29  132.96  132.39  130.83  129.07  128.51  127.83   127.6
  126.24   124.2  123.96  123.15  122.99  122.24   121.2  120.99  120.16  118.66
  118.07  117.59  116.67  116.79  114.88  114.91  114.24  114.05  112.49  113.65
  113.91  116.41  116.76  116.76  116.86  116.86  116.86  116.53  116.98  116.85
  114.35  114.26  114.85  114.51  115.28  115.56  115.93  116.18  116.61  116.83
  117.58  117.33  117.96  118.14  119.44  120.08  121.45  122.32  123.29  131.31
                                                                                
                                                                                
                                                                                
                           111.3   111.3
                                                                                
                                                                                
       0      42   70.01   84.01   91.01  140.01  168.02  182.02  189.02  203.02
  231.02  301.03  322.03  343.03  357.03  378.03  392.04  406.04  420.04  462.04
  497.05  504.05  567.05  581.05  595.05  616.06  630.06  644.06  655.26  776.91
  779.99     780  784.07     827  837.43  871.99     872     891  891.01   925.1
   932.4  976.24     980  980.01  983.54 1041.99  1049.3 1071.21 1078.52 1107.74
 1129.66 1144.27 1158.88 1188.11 1221.84  1267.6 1305.74 1359.13 1382.01 1664.31
  136.31  134.81  133.29  132.96  132.39  130.83  129.07  128.51  127.83   127.6
  126.24   124.2  123.96  123.15  122.99  122.24   121.2  120.99  120.16  118.66
  116.67  116.79  114.88  114.91  114.24  114.05  112.49  113.65  113.91  114.25
  114.26  116.76  116.77  116.86  116.53     117     117   116.8   116.8  117.35
  117.01  117.54  117.75  115.25  115.28  115.56  115.93  116.18  116.61  116.83
  117.58  117.33  117.96  118.14  119.44  120.08  121.45  122.32  123.29  131.31
                                                                                
                                                                                
                                                                                
       1       1                                   111.3   111.3
                       1       1
                                                                                
BR Coef=-1 , 0 , 0 ,, 0 ,,,0.63,0,,0,
WSPro=,,,, 1 ,,,, 0 ,,,, 0 ,,,,-1 ,-1 ,-1 , 0 , 0 , 0 , 0 , 0
BR U #Sta/Elev= 30
       0  137.23   98.01  133.01  140.01  132.16  175.02  129.17  217.02  127.08
  378.03  122.06  427.04  119.22  483.04  117.38  574.05  115.37  684.44   116.1
  724.98  117.71  750.82  114.18  765.43  110.54  769.88   106.8  794.65   106.8
  800.58  110.08  831.18  112.13  882.32  113.45  999.21  112.64 1028.44  113.46
 1072.27  116.64 1218.63  118.68 1294.91  121.43 1317.79  120.59 1379.42  121.77
  1432.2   125.1 1455.08  124.34 1508.48  125.85 1531.36  129.63 1573.42  130.84
BR U #Mann= 5
       0     .06  684.44     .07  765.43    .042  800.58     .07 1379.42     .06
BR D #Sta/Elev= 30
       0  136.62   98.01  132.31  133.01  132.02  161.01  128.98  217.02  125.95
  364.03  122.21  581.05  114.81  616.06  112.09  644.06  113.49   707.2   110.5
  757.29  109.69  785.91  110.77  864.62  109.36  871.78   106.8  886.09  106.45
  893.25   106.8  899.73  109.39  907.56   110.8  938.65  110.62 1033.62   113.8
 1172.43  116.15 1238.19  119.73 1461.49  127.53 1560.65  128.26 1675.06  135.38
 1682.69  135.56  1713.2  131.64 1728.45  133.66 1743.71  137.97 1755.21  138.72
BR D #Mann= 3
       0     .06  864.62    .042  899.73     .06
BC Design=,, 0 ,, 0 ,,,,,,
BC Use User HTab Curves=0
BC User HTab FreeFlow(D)= 0

Type RM Length L Ch R = 1 ,12580.26,9.62,159.53,178.18
BEGIN DESCRIPTION:
Underwater portion adjusted as per bridge inspection survey notes.
END DESCRIPTION:
XS GIS Cut Line= 5
1638435.45298049 721060.561347351637728.32175073721070.160413817
1637680.30020212721296.5764390981637578.66112162721636.756218821
1637395.35984601722060.308125153
#Sta/Elev= 30
       0  136.62   98.01  132.31  133.01  132.02  161.01  128.98  217.02  125.95
  364.03  122.21  581.05  114.81  616.06  112.09  644.06  113.49   707.2   110.5
  757.29  109.69  785.91  110.77  864.62  109.36  871.78   106.8  886.09  106.45
  893.25   106.8  899.73  109.39  907.56   110.8  938.65  110.62 1033.62   113.8
 1172.43  116.15 1238.19  119.73 1461.49  127.53 1560.65  128.26 1675.06  135.38
 1682.69  135.56  1713.2  131.64 1728.45  133.66 1743.71  137.97 1755.21  138.72
#Mann= 3 , 0 , 0
       0     .06       0  864.62    .045       0  899.73     .06       0
#XS Ineff= 2 ,-1
       0  825.26   111.8  977.39 1755.22   111.8
Permanent Ineff=
       F       F
Bank Sta=864.62,899.73
XS Rating Curve= 0 ,0
Exp/Cntr=0.5,0.3

Type RM Length L Ch R = 1 ,12420.73,56.12,95.05,98.14
XS GIS Cut Line= 4
1638375.69198489721005.2458448861637730.52696115721042.755439311
1637708.02120455721112.1481889491637160.38112627721205.922174931
#Sta/Elev= 30
       0  133.27   70.12  131.67  105.18  128.59  154.26  126.38  280.47  122.69
  343.58   118.7  371.63  118.69  420.71  116.76  497.84  115.11   532.9  113.69
  546.92  111.87  567.96  113.26  588.99  113.28  617.04  110.93  712.49  109.59
  722.82  108.78  728.69  107.98  733.41  107.45   748.7  108.94  761.82  109.66
  818.63  110.02  854.14  113.79  918.06  116.78  967.77  120.97 1017.48  121.77
 1131.11  125.49 1166.62  129.53 1202.13  130.26 1251.85  135.26 1274.82  136.34
#Mann= 3 ,-1 , 0
       0     .06       0  728.69    .045       0   748.7     .06       0
Bank Sta=722.82,748.7
XS Rating Curve= 0 ,0
Exp/Cntr=0.3,0.1

Type RM Length L Ch R = 1 ,12325.68,63.3,65.56,67.11
XS GIS Cut Line= 2
1638356.28783219720923.9544498921636891.71651922721134.449517116
#Sta/Elev= 30
       0  133.39   77.79  130.41   99.01   128.6  190.94  123.61  318.24  119.13
  346.52   118.9  445.53  115.12  495.04   114.6  523.32  111.35  544.54  112.89
  565.75  113.09  594.04  110.85  657.69  108.57  664.76   107.5  671.83  106.38
   678.9  106.24   704.3  107.86  707.19  108.08  742.55  109.33  827.41  115.78
  905.21  123.58     983  126.58 1074.93  131.84 1152.72  134.29 1188.08  136.84
 1223.44  140.91  1258.8  143.32 1322.45  143.95 1379.02  145.48 1479.62  145.29
#Mann= 3 ,-1 , 0
       0     .06       0  664.76    .045       0   704.3     .06       0
Bank Sta=657.69,707.19
XS Rating Curve= 0 ,0
Exp/Cntr=0.3,0.1

Type RM Length L Ch R = 1 ,12260.12,69.19,73.87,72.5
XS GIS Cut Line= 3
1638196.18671907720896.361938819 1637678.0926201720957.862317488
1637346.36330496720972.771500185
#Sta/Elev= 30
       0  125.95   35.25  124.17   49.34  123.84  162.13  118.08  190.33  117.62
  218.52  116.32  317.21  113.83  331.31  113.19  345.41  111.48  352.46  111.48
   373.6  112.62   387.7  112.69   401.8  112.07  422.95  110.13   444.1   109.2
  472.29  108.74  507.54  107.22  521.73  107.25  533.68  106.16  542.75  107.11
  551.89  108.46  577.79  111.44  598.81  113.06  640.85  115.41  675.89  118.16
  696.91  120.55  717.93  124.06  731.94  125.65     788  128.63   853.8  132.84
#Mann= 3 ,-1 , 0
       0     .06       0  530.29    .045       0  551.89     .06       0
Bank Sta=521.73,542.75
XS Rating Curve= 0 ,0
Exp/Cntr=0.3,0.1

Type RM Length L Ch R = 1 ,12186.25,136.43,137.69,131.41
XS GIS Cut Line= 3
1638203.14785066720845.8300686781637726.77600174720888.966102242
1637376.06129408 720890.84158197
#Sta/Elev= 30
       0  126.68   56.23  123.28  105.43  121.42  175.72  117.38     246  115.31
  267.09  114.24  309.26  113.94  323.32  113.06  337.37  111.15   344.4  110.99
  372.52  112.46  386.57  112.28  421.72   109.4  485.32   107.6  499.32   106.5
  510.44  105.47  520.32  105.06  532.24  106.74  532.49  106.78  555.32  109.76
  583.32  112.27  639.32   115.8  695.32  119.92  709.32  121.54  730.32  125.79
  737.32  126.57  751.33  126.97  793.33   129.5  807.33  131.03  829.04  132.51
#Mann= 3 ,-1 , 0
       0     .06       0  510.44    .045       0  532.49     .06       0
Bank Sta=499.32,532.24
XS Rating Curve= 0 ,0
Exp/Cntr=0.3,0.1

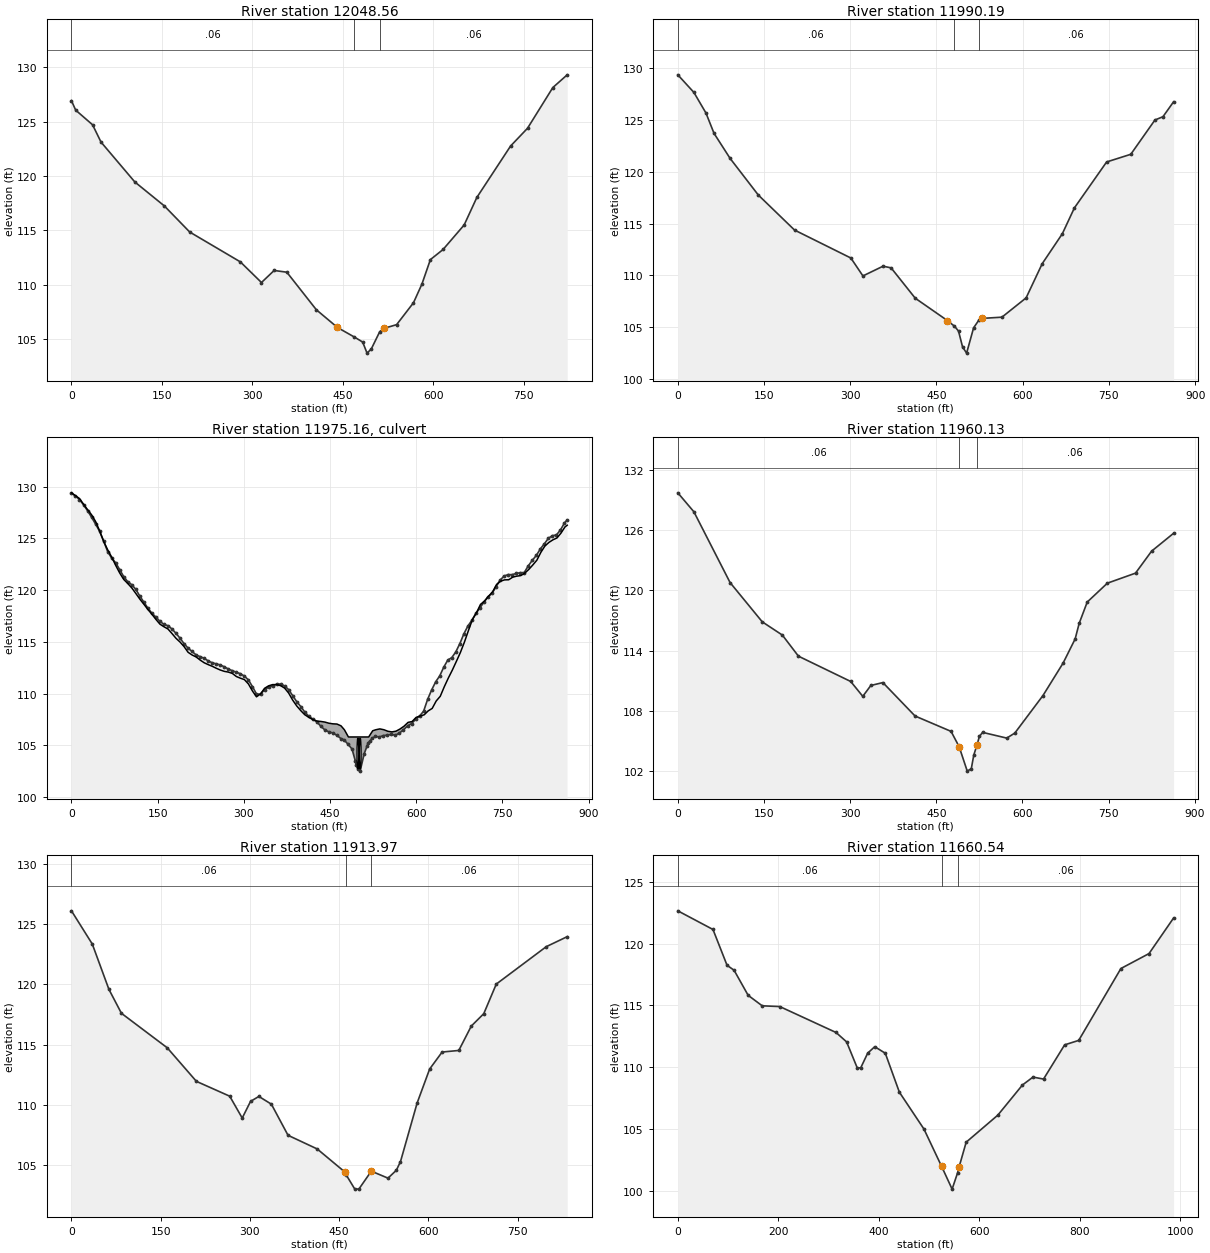
Type RM Length L Ch R = 1 ,12048.56,57.78,58.37,55.11
XS GIS Cut Line= 2
1638206.63308582 720735.326148451637384.81013855720769.568771273
#Sta/Elev= 30
       0  126.94    7.01  126.07   35.03  124.72   49.04  123.13  105.09  119.46
  154.13  117.25  196.17  114.85  280.24   112.1  315.27   110.2  336.29  111.31
  357.31  111.15  406.35  107.69  441.38  106.06  469.41  105.18  483.16  104.72
  490.43   103.7  497.43  104.08  511.44  105.67  518.45  105.98  539.47  106.32
  567.49  108.34   581.5  110.06  595.52  112.31  616.53  113.24  651.57   115.5
  672.58  118.03  728.63  122.77  756.66   124.4  798.69  128.15  822.54  129.32
#Mann= 3 ,-1 , 0
       0     .06       0  469.41    .045       0  511.44     .06       0
Bank Sta=441.38,518.45
XS Rating Curve= 0 ,0
Exp/Cntr=0.5,0.3

Type RM Length L Ch R = 1 ,11990.19,31.45,30.05,30.25
BEGIN DESCRIPTION:
lowered under water portion by 0.5 feet.  Although this bridge is overtopped for the 100Ycur profile, the contraction does not happen as rapidly as the width of the cross section would allow on the left bank.
END DESCRIPTION:
XS GIS Cut Line= 4
1638230.57747491720689.2287269091637756.40689236720695.670447439
1637702.14382797720701.8719404941637368.72327231720713.972236604
#Sta/Elev= 30
       0  129.36      28  127.66      49  125.67   63.01  123.71   91.01  121.29
  140.01  117.76  203.02  114.38  301.03  111.68  322.03  109.95  357.03  110.89
  371.03  110.73  413.04   107.8  469.04  105.64  481.26   105.1  488.31  104.63
  495.35   103.1   502.4   102.5  514.55  104.94  523.53  105.67  528.83  105.85
  563.85  105.97  605.88  107.83   633.9  111.13  668.92  114.02  689.94  116.52
  745.97  120.95     788  121.69  830.03     125  844.04  125.32  862.47  126.76
#Mann= 3 ,-1 , 0
       0     .06       0  481.26    .045       0  523.53     .06       0
Bank Sta=469.04,528.83
XS Rating Curve= 0 ,0
Exp/Cntr=0.5,0.3

Type RM Length L Ch R = 2 ,11975.16,,,
BEGIN DESCRIPTION:
CE033108fs-6  Driveway  Bridge approaches taken from LIDAR.  Photograph taken from end of driveway.  Access was not allowed to view opening.  Assumed the opening was similar to the downstream driveway crossing.  Photograph shows a possible gate - but unsure if it is a flow-thru rail.  Assumed no railing.
END DESCRIPTION:
Bridge Culvert--1,0,-1,-1, 0
Deck Dist Width WeirC Skew NumUp NumDn MinLoCord MaxHiCord MaxSubmerge Is_Ogee
9,14,2.6,0, 121, 121, , , 0.95, 0, 0,0,,
       0       7      14      21      28      35      42      49   56.01   63.01
   70.01   77.01   84.01   91.01   98.01  105.01  112.01  119.01  126.01  133.01
  140.01  147.01  154.01  161.01  168.02  175.02  182.02  189.02  196.02  203.02
  210.02  217.02  224.02  231.02  238.02  245.02  252.02  259.02  266.02  273.03
  280.03  287.03  294.03  301.03  308.03  315.03  322.03  329.03  336.03  343.03
  350.03  357.03  364.03  371.03  378.03  385.04  392.04  399.04  406.04  413.04
  420.04  427.04  434.04  441.04  448.04  455.04  462.04  469.04  474.97  482.01
  517.24  524.29  529.75  536.76  543.76  550.77  557.77  564.78  571.78  578.79
  585.79  592.79   599.8   606.8  613.81  620.81  627.82  634.82  641.83  648.83
  655.84  662.84  669.85  676.85  683.86  690.86  697.86  704.87  711.87  718.88
  725.88  732.89  739.89   746.9   753.9  760.91  767.91  774.92  781.92  788.92
  795.93  802.93  809.94  816.94  823.95  830.95  837.96  844.96  851.97  858.97
  862.81
  129.39  129.11  128.84  128.29  127.77  127.27  126.62  125.72   124.7  123.89
  123.18  122.38  121.64  121.02  120.63   120.2  119.67  119.12  118.63  118.12
  117.66  117.16   116.7  116.45  116.23  115.79  115.33  114.97  114.53  113.98
  113.72  113.53  113.23  112.97  112.79  112.63  112.44  112.27  112.14  112.07
  111.94  111.64  111.48  111.34  110.92  110.24  109.68  109.96   110.5  110.74
  110.86  110.86  110.76  110.52  110.04  109.36   108.8  108.35  107.95   107.7
  107.48  107.34   107.3  107.24  107.13  107.07  107.05  106.88   106.5   105.8
   105.8   106.4   106.5  106.58   106.5  106.35  106.29  106.36  106.57  106.84
  107.21  107.29  107.69  107.83  107.94  108.32  108.56  109.28  109.73  110.65
  111.49  112.26   113.1  113.96  114.96  116.08  117.15   117.8  118.61  118.93
   119.4  119.82  120.54  120.86  120.98  120.99  121.24  121.34  121.39  121.63
  121.99  122.42  122.88  123.64  124.25   124.6  124.85  125.03   125.5   126.1
  126.26
                                                                                
                                                                                
                                                                                
                                                                                
                                                                                
                                                                                
                                                                                
                                                                                
                                                                                
                                                                                
                                                                                
                                                                                
        
       0       7      14      21      28      35      42      49   56.01   63.01
   70.01   77.01   84.01   91.01   98.01  105.01  112.01  119.01  126.01  133.01
  140.01  147.01  154.01  161.01  168.02  175.02  182.02  189.02  196.02  203.02
  210.02  217.02  224.02  231.02  238.02  245.02  252.02  259.02  266.02  273.03
  280.03  287.03  294.03  301.03  308.03  315.03  322.03  329.03  336.03  343.03
  350.03  357.03  364.03  371.03  378.03  385.04  392.04  399.04  406.04  413.04
  420.04  427.04  434.04  441.04  448.04  455.04  462.04  469.04  474.97  482.01
  517.24  524.29  529.75  536.76  543.76  550.77  557.77  564.78  571.78  578.79
  585.79  592.79   599.8   606.8  613.81  620.81  627.82  634.82  641.83  648.83
  655.84  662.84  669.85  676.85  683.86  690.86  697.86  704.87  711.87  718.88
  725.88  732.89  739.89   746.9   753.9  760.91  767.91  774.92  781.92  788.92
  795.93  802.93  809.94  816.94  823.95  830.95  837.96  844.96  851.97  858.97
  863.15
  129.39  129.11  128.84  128.29  127.77  127.27  126.62  125.72   124.7  123.89
  123.18  122.38  121.64  121.02  120.63   120.2  119.67  119.12  118.63  118.12
  117.66  117.16   116.7  116.45  116.23  115.79  115.33  114.97  114.53  113.98
  113.72  113.53  113.23  112.97  112.79  112.63  112.44  112.27  112.14  112.07
  111.94  111.64  111.48  111.34  110.92  110.24  109.68  109.96   110.5  110.74
  110.86  110.86  110.76  110.52  110.04  109.36   108.8  108.35  107.95   107.7
  107.48  107.34   107.3  107.24  107.13  107.07  107.05  106.88   106.5   105.8
   105.8   106.4   106.5  106.58   106.5  106.35  106.29  106.36  106.57  106.84
  107.21  107.29  107.69  107.83  107.94  108.32  108.56  109.28  109.73  110.65
  111.49  112.26   113.1  113.96  114.96  116.08  117.15   117.8  118.61  118.93
   119.4  119.82  120.54  120.86  120.98  120.99  121.24  121.34  121.39  121.63
  121.99  122.42  122.88  123.64  124.25   124.6  124.85  125.03   125.5   126.1
  126.26
                                                                                
                                                                                
                                                                                
                                                                                
                                                                                
                                                                                
                                                                                
                                                                                
                                                                                
                                                                                
                                                                                
                                                                                
        
BR Coef=-1 , 0 , 0 ,, 0 ,,,0.8,0,,0,
WSPro=,,,, 1 ,,,, 0 ,,,, 0 ,,,,-1 ,-1 ,-1 , 0 , 0 , 0 , 0 , 0
Culvert=1,3,,16,0.015,0.2,1,1,3,102.7,498.5,102.3,502.8,Culvert #1  , 0 ,9
Culvert Bottom n=0.02
Culvert=1,3,,16,0.015,0.2,1,1,3,102.7,502.5,102.3,506.8,Culvert #2  , 0 ,9
Culvert Bottom n=0.02
BR U #Sta/Elev= 129
       0  129.36       7  129.09      14  128.74      21  128.24      28  127.66
      35  127.03      42  126.37      49  125.67   56.01  124.74   63.01  123.71
   70.01  123.08   77.01  122.63   84.01  121.95   91.01  121.29   98.01   120.8
  105.01  120.51  112.01  120.06  119.01  119.41  126.01  118.83  133.01  118.25
  140.01  117.76  147.01  117.38  154.01  116.97  161.01  116.68  168.02  116.55
  175.02  116.23  182.02  115.81  189.02  115.34  196.02  114.81  203.02  114.38
  210.02  114.06  217.02  113.72  224.02  113.56  231.02   113.4  238.02  113.15
  245.02  112.97  252.02  112.87  259.02  112.76  266.02  112.58  273.03  112.37
  280.03   112.2  287.03  112.05  294.03  111.91  301.03  111.68  308.03  111.31
  315.03  110.66  322.03  109.95  329.03  109.94  336.03  110.37  343.03   110.6
  350.03  110.75  357.03  110.89  364.03  110.92  371.03  110.73  378.03  110.37
  385.04  109.79  392.04  109.21  399.04  108.74  406.04  108.21  413.04   107.8
  420.04  107.53  427.04  107.26  434.04  106.83  441.04  106.48  448.04  106.29
  455.04  106.18  462.04  105.95  469.04  105.64  474.21  105.53  481.26   105.1
  488.31  104.63  493.94   103.5  495.35   103.1  498.42   102.7   502.4   102.5
  509.44  104.17  514.55  104.94  516.49  105.23  518.86  105.37  523.53  105.67
  528.83  105.85  535.84   105.8  542.84  105.93  549.84  105.98  556.85  106.04
  563.85  105.97  570.86  106.18  577.86  106.49  584.87  106.86  591.87  107.09
  598.88   107.5  605.88  107.83  612.89  108.29  619.89  109.44   626.9  110.35
   633.9  111.13   640.9   111.7  647.91  112.54  654.91  113.23  661.92  113.47
  668.92  114.02  675.93  114.82  682.93  115.76  689.94  116.52  696.94  117.08
  703.95  117.75  710.95  118.27  717.96  118.85  724.96  119.34  731.96  119.68
  738.97  120.32  745.97  120.95  752.98  121.35  759.98  121.49  766.99  121.48
  773.99   121.6     781  121.67     788  121.69  795.01  122.33  802.01  122.87
  809.02  123.34  816.02  123.97  823.03  124.46  830.03     125  837.03  125.25
  844.04  125.32  851.04   125.8  858.05  126.48  862.47  126.76
BR U #Mann= 3
       0     .06  481.26     .04  523.53     .06
BR D #Sta/Elev= 128
       0  129.72       7  129.43      14  128.94      21  128.39      28  127.83
      35  127.14      42  126.32      49  125.39   56.01  124.47   63.01  123.69
   70.01  122.94   77.01  122.25   84.01  121.52   91.01  120.78   98.01  120.28
  105.01  119.88  112.01  119.38  119.01   118.9  126.01  118.45  133.01  117.94
  140.01  117.39  147.01  116.87  154.01  116.57  161.01   116.4  168.02  116.21
  175.02  115.92  182.02  115.55  189.02  115.07  196.02  114.51  203.02  113.94
  210.02  113.45  217.02  113.14  224.02  112.88  231.02   112.6  238.02  112.41
  245.02  112.35  252.02  112.19  259.02  112.05  266.02  111.98  273.03  111.74
  280.03   111.5  287.03  111.34  294.03  111.14  301.03  110.93  308.03  110.53
  315.03  109.73  322.03  109.45  329.03  110.04  336.03  110.53  343.03  110.76
  350.03  110.87  357.03  110.82  364.03  110.57  371.03  110.16  378.03  109.66
  385.04  109.19  392.04  108.72  399.04  108.32  406.04   107.8  413.04  107.49
  420.04  107.34  427.04  107.05  434.04  106.83  441.04  106.52  448.04  106.39
  455.04  106.36  462.04  106.28  469.04  106.16  475.72  105.96  482.76  105.48
  489.81  104.43  495.11   103.5  496.86   103.2   503.9     102  510.95  102.24
   515.3   103.6  515.48  103.63  517.99  104.13  520.85   104.6  525.04  105.46
  530.68  105.86  537.68  105.93  544.69   105.8  551.69  105.58  558.69  105.41
   565.7  105.35   572.7  105.29  579.71  105.44  586.71  105.79  593.72   106.3
  600.72  106.77  607.73  107.38  614.73   107.9  621.74  108.59  628.74  109.08
  635.75  109.53  642.75  110.12  649.75  110.73  656.76  111.44  663.76  112.16
  670.77  112.76  677.77  113.57  684.78  114.27  691.78  115.17  698.79  116.72
  705.79  117.91   712.8  118.84   719.8  119.23  726.81  119.62  733.81  120.07
  740.82  120.46  747.82  120.72  754.82  120.82  761.83  120.89  768.83  120.98
  775.84  121.04  782.84  121.12  789.85  121.42  796.85  121.72  803.86  122.42
  810.86  122.81  817.87  123.36  824.87  123.91  831.88  124.22  838.88  124.39
  845.88  124.61  852.89   125.1  863.15  125.69
BR D #Mann= 3
       0     .06  489.81     .04  520.85     .06
BC Design=,, 0 ,, 0 ,,,,,,
BC Use User HTab Curves=0
BC User HTab FreeFlow(D)= 0

Type RM Length L Ch R = 1 ,11960.13,47.25,46.16,49.81
BEGIN DESCRIPTION:
lowered under water portion by 0.5 feet
END DESCRIPTION:
XS GIS Cut Line= 4
1638230.16995533720659.231494918 1637754.4951385720665.693650797
 1637699.8932372720671.9338680651637367.63524681720683.991973102
#Sta/Elev= 30
       0  129.72      28  127.83   91.01  120.78  147.01  116.87  182.02  115.55
  210.02  113.45  301.03  110.93  322.03  109.45  336.03  110.53  357.03  110.82
  413.04  107.49  475.72  105.96  489.81  104.43   503.9     102  510.95  102.24
   515.3   103.6  520.85   104.6  525.04  105.46  530.68  105.86   572.7  105.29
  586.71  105.79  635.75  109.53  670.77  112.76  691.78  115.17  698.79  116.72
   712.8  118.84  747.82  120.72  796.85  121.72  824.87  123.91  863.15  125.69
#Mann= 3 , 0 , 0
       0     .06       0  489.81    .045       0  520.85     .06       0
Bank Sta=489.81,520.85
XS Rating Curve= 0 ,0
Exp/Cntr=0.5,0.3

Type RM Length L Ch R = 1 ,11913.97,252.78,253.44,264.15
XS GIS Cut Line= 2
1638206.63308582720609.7698648421637373.39593092720632.598280072
#Sta/Elev= 30
       0  126.08   35.01  123.33   63.02  119.57   84.03  117.59  161.06  114.73
  210.08  111.95   266.1  110.72  287.11  108.91  301.11  110.29  315.12   110.7
  336.13  110.06  364.14  107.48  413.15  106.35  459.63  104.44  462.17  104.18
  476.18  103.04  483.18  103.02  504.19  104.51   532.2  103.93   546.2  104.58
  553.21   105.3  581.22  110.16  602.23  112.97  623.23  114.38  651.24  114.51
  672.25  116.53  693.26  117.56  714.27  120.01   798.3  123.11  833.55  123.94
#Mann= 3 ,-1 , 0
       0     .06       0  462.17    .045       0  504.19     .06       0
Bank Sta=459.63,504.19
XS Rating Curve= 0 ,0
Exp/Cntr=0.3,0.1

Type RM Length L Ch R = 1 ,11660.54,248.7,242.34,223.87
XS GIS Cut Line= 2
1638335.80212417720373.1874857691637348.93484287720384.498285547
#Sta/Elev= 30
       0  122.65      70  121.14   98.01  118.24  112.01  117.84  140.01  115.81
  168.01  114.96  203.01   114.9  315.02   112.8  336.02  112.04  357.02  109.95
  364.02  109.93  378.02  111.13  392.03  111.65  413.03  111.12  441.03  107.97
  490.03  104.98  525.03  101.97  546.04  100.12  557.03  101.45  560.04  101.93
  574.04  103.92  637.04  106.11  686.05  108.55  707.05  109.19  728.05  109.03
  770.05   111.8  798.05  112.16  882.06  117.98  938.06  119.19  986.93  122.07
#Mann= 3 ,-1 , 0
       0     .06       0  525.03    .045       0  557.03     .06       0
Bank Sta=525.03,560.04
XS Rating Curve= 0 ,0
Exp/Cntr=0.3,0.1

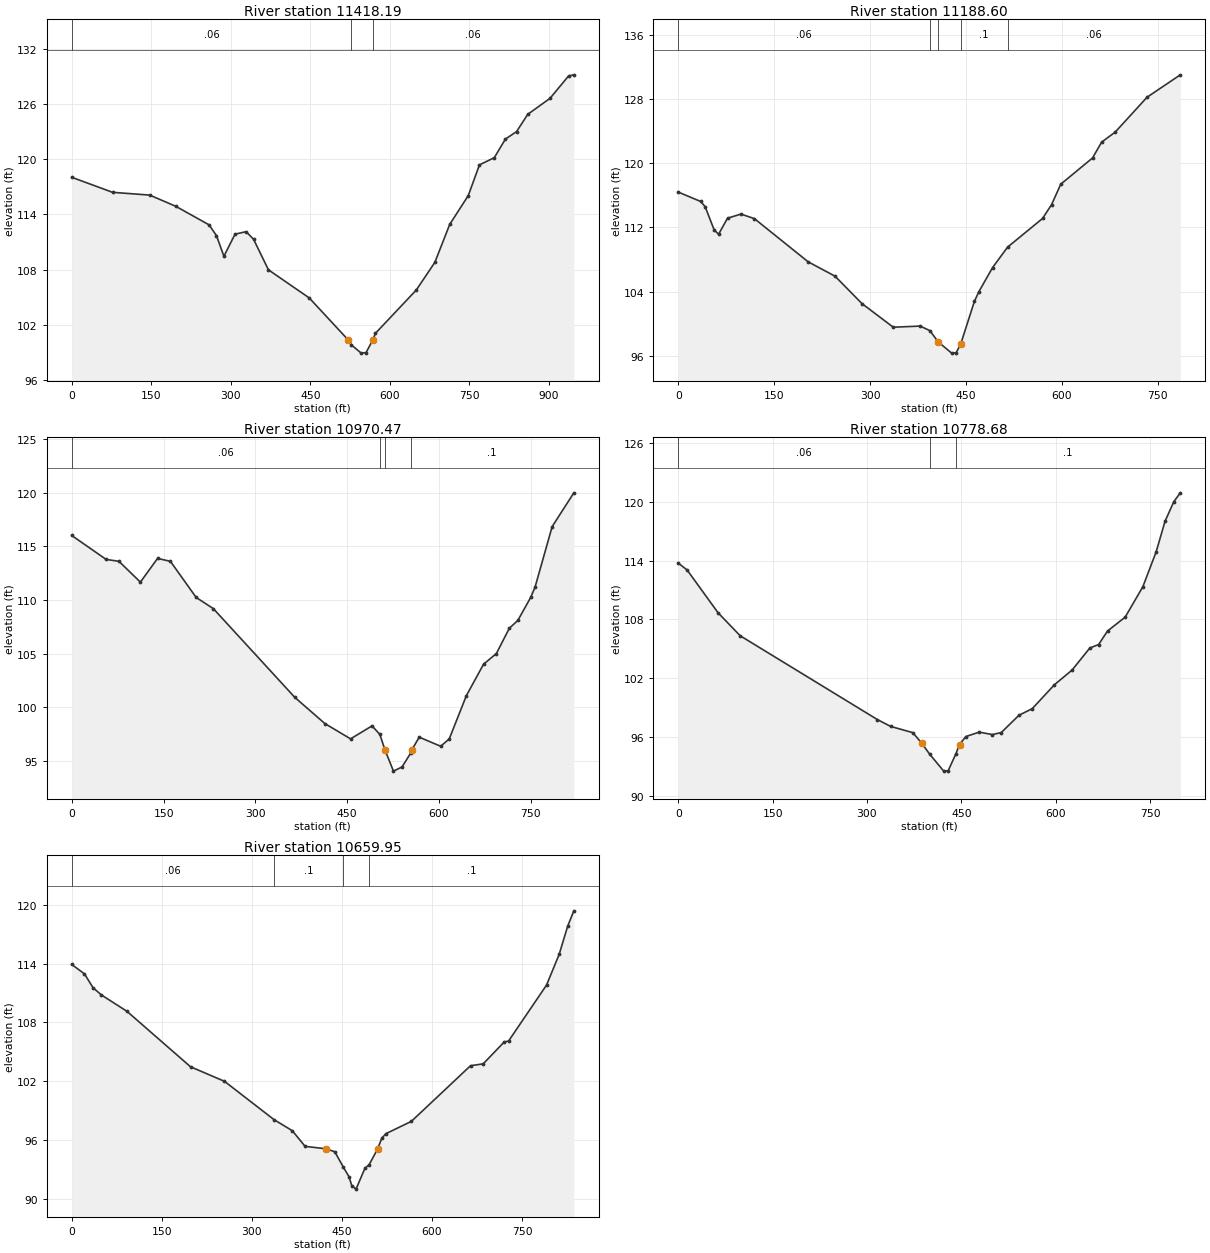
Type RM Length L Ch R = 1 ,11418.19,211.9,229.59,229.84
XS GIS Cut Line= 4
1638315.09680849720125.9759779721637787.40717588720133.931098074
1637752.93498881720163.0998716951637379.04434462720181.661818594
#Sta/Elev= 30
       0  118.03   77.01   116.4  147.02   116.1  196.02  114.89  259.03  112.87
  273.03   111.7  287.03  109.46  308.03  111.86  329.04  112.13  343.04   111.3
  371.04  107.99  448.05  104.94  521.74  100.37  527.75   99.83  546.09   98.95
  555.26   99.01  567.88  100.37  572.91   101.1     650   105.8  685.04   108.8
  713.08  112.92  748.12  116.05  769.15  119.38  797.18  120.16  818.21  122.18
  839.23  122.99  860.26  124.86  902.31   126.6  937.35  129.03  947.26  129.15
#Mann= 3 ,-1 , 0
       0     .06       0  527.75    .045       0  567.88     .06       0
Bank Sta=521.74,567.88
XS Rating Curve= 0 ,0
Exp/Cntr=0.3,0.1

Type RM Length L Ch R = 1 ,11188.60,208.23,218.13,224.29
XS GIS Cut Line= 3
1638127.17840114719951.9022786021637735.41031428719933.680507123
1637348.19767025720002.012150183
#Sta/Elev= 30
       0   116.4   35.04  115.23   42.05  114.59   56.06  111.71   63.07  111.14
   77.08  113.14   98.11  113.66  119.13  113.09  203.22  107.71  245.26  105.92
  287.31  102.51  336.36   99.56  378.41    99.7  393.71   99.13  406.41   97.75
  427.73   96.33  434.84   96.39  441.95   97.48  463.27  102.78  470.38     104
  491.71  106.99  515.21  109.54   569.9  113.11  584.11  114.85  598.33  117.38
  648.09  120.65   662.3  122.62  683.63  123.88  733.38  128.22  785.39  131.01
#Mann= 5 ,-1 , 0
       0     .06       0  393.71      .1       0  406.41    .045       0
  441.95      .1       0  515.21     .06       0
Bank Sta=406.41,441.95
XS Rating Curve= 0 ,0
Exp/Cntr=0.3,0.1

Type RM Length L Ch R = 1 ,10970.47,189.1,191.8,194.9
XS GIS Cut Line= 2
1638222.28707413719749.4336270541637402.90970488719712.309733316
#Sta/Elev= 30
       0  116.01   56.06  113.78   77.08   113.6  112.11  111.66  140.14  113.87
  161.17   113.6  203.21  110.23  231.24  109.19  364.37  100.91  413.42   98.47
  455.47   97.04   490.5   98.25  503.29   97.46  511.52   96.03  525.54   94.03
  539.55   94.42  553.57    95.7  555.46      96  567.58    97.2  602.62   96.35
  616.63   97.03  644.66  101.07  672.69     104  693.71     105  714.73  107.35
  728.75  108.09  749.77  110.24  756.78  111.18   784.8  116.84  820.22  119.99
#Mann= 4 ,-1 , 0
       0     .06       0  503.29      .1       0  511.52    .045       0
  553.57      .1       0
Bank Sta=511.52,555.46
XS Rating Curve= 0 ,0
Exp/Cntr=0.3,0.1

Type RM Length L Ch R = 1 ,10778.68,114.26,118.72,115.76
XS GIS Cut Line= 2
1638102.40590647719578.5583471511637308.22993024 719498.29588151
#Sta/Elev= 30
       0  113.74   14.07  113.04   63.32  108.68    98.5  106.34   316.6   97.81
  337.71   97.11  372.89   96.48  386.96   95.42  399.67   94.29  422.14   92.56
  429.17    92.6  441.34   94.31   447.2   95.27  457.32   96.08  478.42   96.53
  499.53   96.28   513.6   96.49  541.75   98.25  562.85   98.92  598.03  101.35
  626.17  102.85  654.32  105.09  668.39  105.45  682.46  106.82   710.6  108.24
  738.74  111.34  759.85  114.89  773.92  117.99  787.99     120  798.22  120.89
#Mann= 3 ,-1 , 0
       0     .06       0  399.67    .045       0  441.34      .1       0
Bank Sta=386.96,447.2
XS Rating Curve= 0 ,0
Exp/Cntr=0.5,0.3

Type RM Length L Ch R = 1 ,10659.95,40.03,40.81,42.26
BEGIN DESCRIPTION:
lowered under water portion by 0.5'.
END DESCRIPTION:
XS GIS Cut Line= 3
 1638129.2469613719486.4262233531637652.50046623719420.751961276
1637299.22420809719385.764104545
#Sta/Elev= 30
       0   113.9    21.2  112.94   35.33  111.54   49.46  110.79   91.86  109.13
  197.85  103.47  254.38  101.99  336.76   98.09  367.44   96.95  388.64   95.36
  423.97   95.11   438.1   94.81  452.23   93.25   461.7   92.27  466.36   91.36
  473.43      91  488.28   93.12  495.32    93.5  509.39   95.09  516.42    96.2
  523.45   96.66  565.66   97.91  664.14  103.58  685.24  103.77  720.41  106.01
  727.45  106.09  790.76   111.8  811.86  114.94  825.93   117.8  836.25  119.37
#Mann= 4 ,-1 , 0
       0     .06       0  336.76      .1       0  452.23    .045       0
  495.32      .1       0
Bank Sta=423.97,509.39
XS Rating Curve= 0 ,0
Exp/Cntr=0.5,0.3