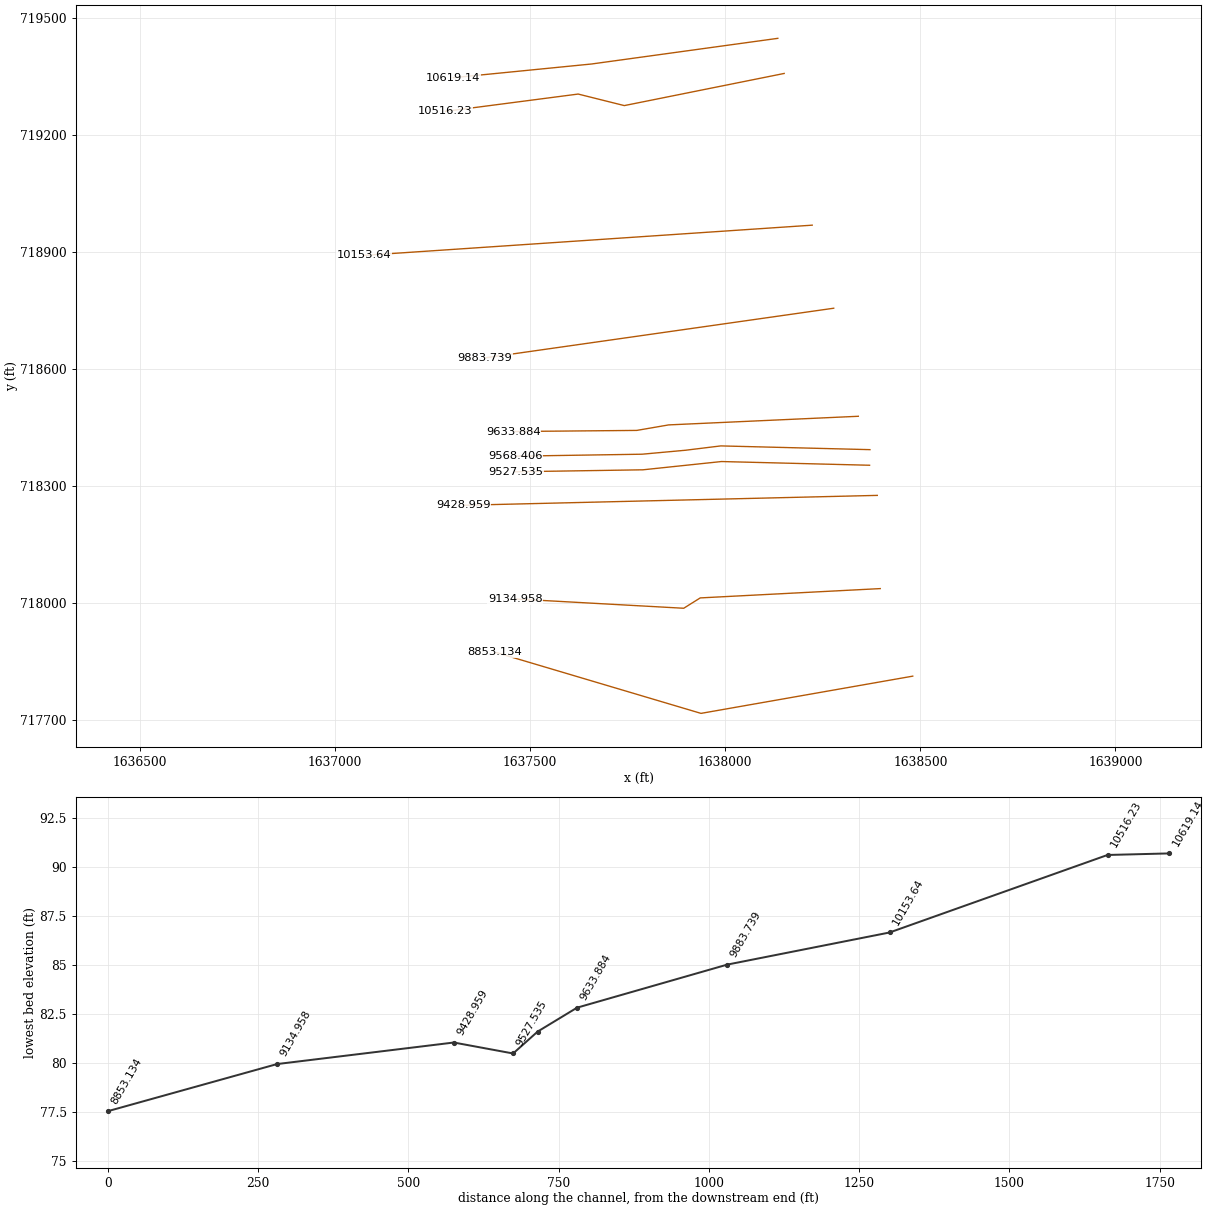
HEC-RAS study Dogwood.prj: Dogwood Run

--- Dogwood.g13 (geometry) --- (continued)

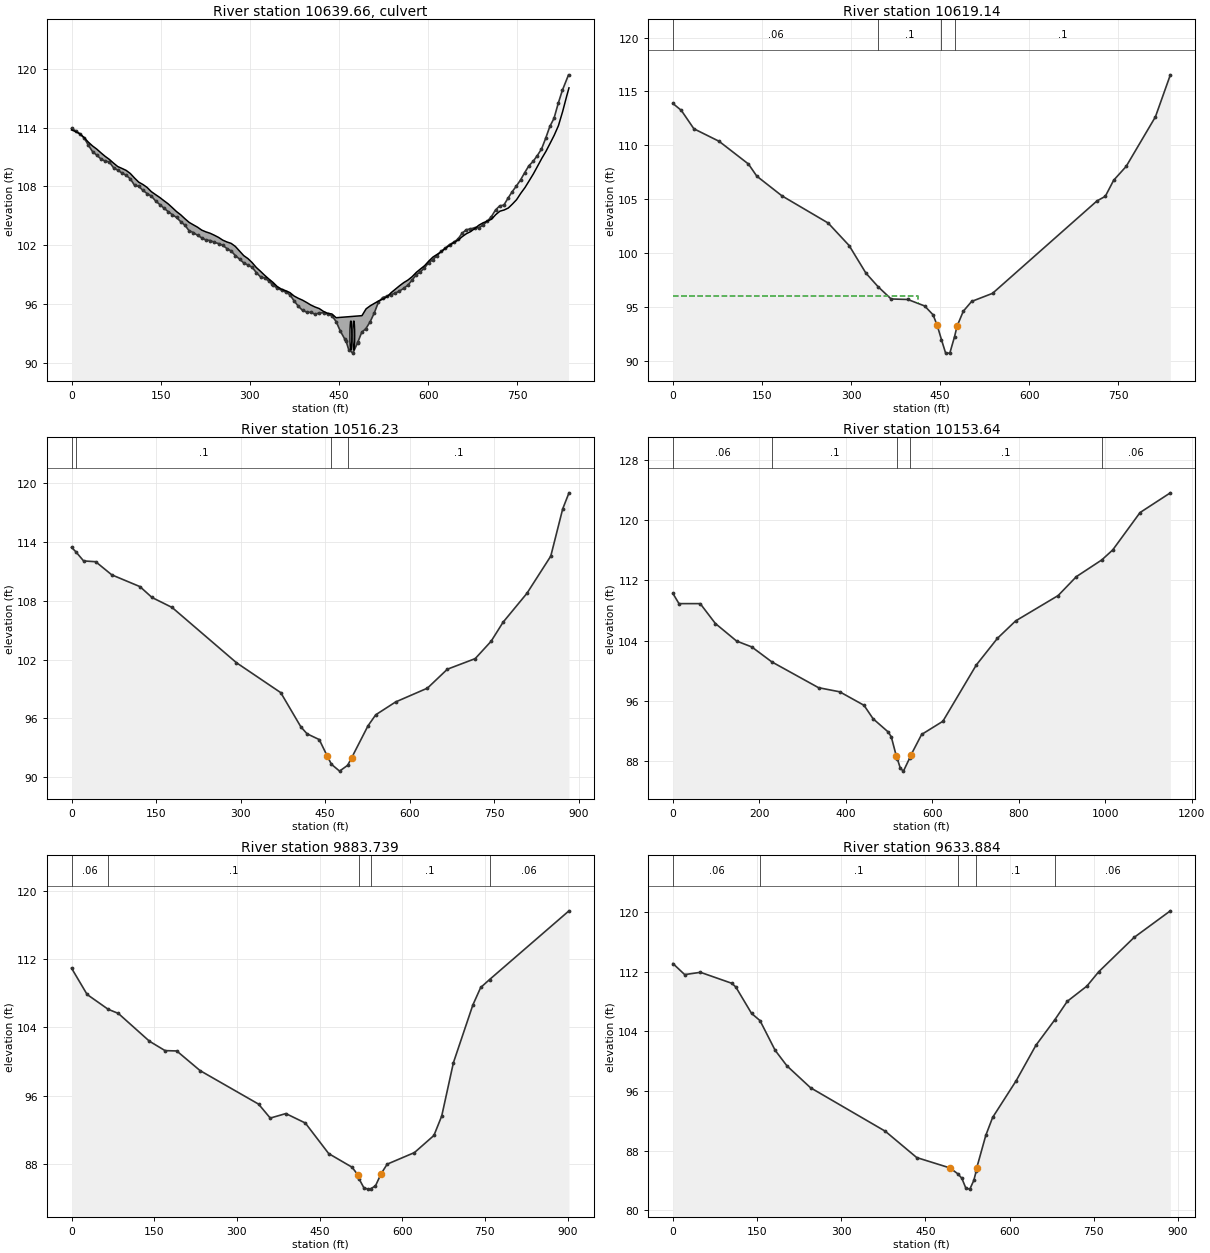
Type RM Length L Ch R = 2 ,10639.66,,,
BEGIN DESCRIPTION:
CE033108FS-4  Driveway  Photograph was available, but no survey information.  Assumed 36" dia culverts.
END DESCRIPTION:
Bridge Culvert--1,0,-1,-1, 0
Deck Dist Width WeirC Skew NumUp NumDn MinLoCord MaxHiCord MaxSubmerge Is_Ogee
15,14,2.6,0, 115, 115, , , 0.95, 0, 0,0,,
       0    7.07   14.13    21.2   28.26   35.33    42.4   49.46   56.53   63.59
   70.66   77.73   84.79   91.86   98.93  105.99  113.06  120.12  127.19  134.26
  141.32  148.39  155.45  162.52  169.59  176.65  183.72  190.78  197.85  204.92
  211.98  219.05  226.12  233.18  240.25  247.31  254.38  261.45  268.51  275.58
  282.64  289.71  296.78  303.84  310.91  317.97  325.04  332.11  339.17  346.24
  353.31  360.37  367.44   374.5  381.57  388.64   395.7  402.77  409.83   416.9
  423.97  431.03   438.1  445.16  488.66   495.7  502.73  509.77   516.8  523.84
  530.87   537.9  544.94  551.97  559.01  566.04  573.08  580.11  587.14  594.18
  601.21  608.25  615.28  622.32  629.35  636.38  643.42  650.45  657.49  664.52
  671.55  678.59  685.62  692.66  699.69  706.73  713.76  720.79  727.83  734.86
   741.9  748.93  755.97     763  770.03  777.07   784.1  791.14  798.17  805.21
  812.24  819.27  826.31  833.34  837.02
  113.75  113.58  113.34  112.97  112.51  112.12   111.8  111.42  111.06  110.75
  110.37  110.02  109.83  109.63  109.31  108.85  108.43  108.19  107.89  107.46
  107.16  106.87  106.54  106.22  105.83  105.43   105.1   104.7  104.33  104.08
  103.84  103.54  103.36  103.22  103.02   102.8  102.52  102.33  102.19  101.88
  101.41  100.94  100.64  100.23   99.73   99.34   98.93   98.55    98.2   97.78
   97.52   97.36   97.17   96.82   96.59    96.4   96.16    95.9    95.7   95.54
   95.25   95.06   94.99   94.61   94.82   95.52   95.83   96.08   96.32   96.51
   96.74   97.17   97.52   97.87   98.19   98.45   98.79   99.23   99.58   99.92
  100.39   100.8  101.07  101.35  101.69  101.99  102.27  102.52  102.88  103.18
  103.39  103.71  104.05  104.29  104.46  104.65  105.12  105.47  105.59  105.79
   106.2  106.65   107.3  107.88  108.57  109.27  110.05  110.84  111.56  112.38
  113.22  114.19  115.62  117.24  118.04
                                                                                
                                                                                
                                                                                
                                                                                
                                                                                
                                                                                
                                                                                
                                                                                
                                                                                
                                                                                
                                                                                
                                        
       0    7.07   14.13    21.2   28.26   35.33    42.4   49.46   56.53   63.59
   70.66   77.73   84.79   91.86   98.93  105.99  113.06  120.12  127.19  134.26
  141.32  148.39  155.45  162.52  169.59  176.65  183.72  190.78  197.85  204.92
  211.98  219.05  226.12  233.18  240.25  247.31  254.38  261.45  268.51  275.58
  282.64  289.71  296.78  303.84  310.91  317.97  325.04  332.11  339.17  346.24
  353.31  360.37  367.44   374.5  381.57  388.64   395.7  402.77  409.83   416.9
  423.97  431.03   438.1  445.16  488.66   495.7  502.73  509.77   516.8  523.84
  530.87   537.9  544.94  551.97  559.01  566.04  573.08  580.11  587.14  594.18
  601.21  608.25  615.28  622.32  629.35  636.38  643.42  650.45  657.49  664.52
  671.55  678.59  685.62  692.66  699.69  706.73  713.76  720.79  727.83  734.86
   741.9  748.93  755.97     763  770.03  777.07   784.1  791.14  798.17  805.21
  812.24  819.27  826.31  833.34  837.78
  113.75  113.58  113.34  112.97  112.51  112.12   111.8  111.42  111.06  110.75
  110.37  110.02  109.83  109.63  109.31  108.85  108.43  108.19  107.89  107.46
  107.16  106.87  106.54  106.22  105.83  105.43   105.1   104.7  104.33  104.08
  103.84  103.54  103.36  103.22  103.02   102.8  102.52  102.33  102.19  101.88
  101.41  100.94  100.64  100.23   99.73   99.34   98.93   98.55    98.2   97.78
   97.52   97.36   97.17   96.82   96.59    96.4   96.16    95.9    95.7   95.54
   95.25   95.06   94.99   94.61   94.82   95.52   95.83   96.08   96.32   96.51
   96.74   97.17   97.52   97.87   98.19   98.45   98.79   99.23   99.58   99.92
  100.39   100.8  101.07  101.35  101.69  101.99  102.27  102.52  102.88  103.18
  103.39  103.71  104.05  104.29  104.46  104.65  105.12  105.47  105.59  105.79
   106.2  106.65   107.3  107.88  108.57  109.27  110.05  110.84  111.56  112.38
  113.22  114.19  115.62  117.24  118.04
                                                                                
                                                                                
                                                                                
                                                                                
                                                                                
                                                                                
                                                                                
                                                                                
                                                                                
                                                                                
                                                                                
                                        
BR Coef=-1 , 0 , 0 ,, 0 ,,,0.8,0,,0,
WSPro=,,,, 1 ,,,, 0 ,,,, 0 ,,,,-1 ,-1 ,-1 , 0 , 0 , 0 , 0 , 0
Culvert=1,3,,20,0.015,0.2,1,1,3,91.3,470,91,459,Culvert #1  , 0 ,10
Culvert Bottom n=0.02
Culvert=1,3,,20,0.015,0.2,1,1,3,91.3,475,91,464,Culvert #2  , 0 ,10
Culvert Bottom n=0.02
BR U #Sta/Elev= 122
       0   113.9    7.07  113.66   14.13  113.36    21.2  112.94   28.26   112.2
   35.33  111.54    42.4  111.18   49.46  110.79   56.53  110.57   63.59  110.48
   70.66   109.9   77.73  109.65   84.79  109.36   91.86  109.13   98.93  108.76
  105.99  108.11  113.06     108  120.12  107.59  127.19  107.26  134.26  107.01
  141.32  106.52  148.39  106.15  155.45  105.78  162.52  105.43  169.59  105.11
  176.65  104.83  183.72   104.4  190.78  104.04  197.85  103.47  204.92  103.29
  211.98  103.01  219.05  102.75  226.12  102.53  233.18  102.48  240.25  102.29
  247.31  102.17  254.38  101.99  261.45  101.66  268.51  101.41  275.58  100.95
  282.64  100.59  289.71  100.19  296.78   99.98  303.84   99.75  310.91   99.21
  317.97   98.77  325.04   98.65  332.11   98.34  336.76   98.09  339.17   97.95
  346.24    97.6  353.31   97.42  360.37   97.22  367.44   96.95   374.5   96.32
  381.57   95.78  388.64   95.36   395.7   95.18  402.77   95.15  409.83   94.96
   416.9    95.1  423.97   95.11  431.03   94.99   438.1   94.81  445.16   94.22
  452.23   93.25   459.3   92.48   461.7   92.27  466.36   91.36  473.43      91
  481.25   92.04  481.77   92.12  488.28   93.12  495.32    93.5  502.35   94.18
  509.39   95.09  516.42    96.2  523.45   96.66  530.49   96.81  537.52   96.95
  544.56   97.11  551.59   97.32  558.63   97.59  565.66   97.91  572.69   98.41
  579.73   98.96  586.76   99.28   593.8   99.67  600.83  100.22  607.86  100.51
   614.9  100.93  621.93  101.37  628.97  101.71     636  102.07  643.04   102.3
  650.07  102.62   657.1  103.21  664.14  103.58  671.17  103.66  678.21  103.78
  685.24  103.77  692.28  104.05  699.31  104.43  706.34   104.9  713.38  105.59
  720.41  106.01  727.45  106.09  734.48   106.8  741.52  107.46  748.55  108.04
  755.58  108.66  762.62  109.41  769.65  110.11  776.69  110.55  783.72  111.14
  790.76   111.8  797.79   112.9  804.82  114.11  811.86  114.94  818.89  116.46
  825.93   117.8  836.25  119.37
BR U #Mann= 4
       0     .06  336.76      .1  452.23     .04  495.32      .1
BR D #Sta/Elev= 124
       0  113.88    7.07  113.63   14.13  113.24    21.2  112.65   28.26  112.04
   35.33  111.53    42.4  111.33   49.46  111.18   56.53  110.94   63.59  110.85
   70.66  110.52   77.73  110.37   84.79  110.03   91.86  109.75   98.93  109.36
  105.99  108.93  113.06  108.83  120.12  108.52  127.19  108.26  134.26  107.63
  141.32  107.13  148.39  106.83  155.45  106.51  162.52  106.22  169.59  105.93
  176.65  105.64  183.72   105.3  190.78  105.06  197.85  104.87  204.92   104.7
  211.98  104.38  219.05  104.19  226.12  104.07  233.18  103.82  240.25  103.44
  247.31   103.2  254.38  103.02  261.45  102.78  268.51  102.37  275.58  101.81
  282.64  101.56  289.71  100.91  296.78  100.69  303.84  100.14  310.91   99.49
  317.97    98.8  325.04   98.13  332.11   97.71  339.17   97.44   345.5   96.87
  346.24    96.8  353.31   96.29  360.37    95.9  367.44   95.73   374.5   95.58
  381.57    95.5  388.64   95.51   395.7   95.68  402.77   95.42  409.83   95.34
   416.9   95.29  423.97   95.08  431.03   94.82   438.1   94.26  445.16   93.27
  452.23   91.96  453.74   91.81   459.3    90.7  466.36    90.7  473.43   92.07
  474.27   92.22  478.63   93.21  482.01   93.67  489.05   94.59  496.08   95.08
  503.11    95.5  510.15    95.7  517.18   95.86  524.22   95.95  531.25   95.98
  538.29   96.25  545.32   96.61  552.35   96.91  559.39   97.35  566.42   97.73
  573.46   97.99  580.49   98.39  587.53   98.76  594.56   98.97  601.59   99.32
  608.63   99.71  615.66  100.15   622.7  100.46  629.73  100.58  636.77  100.89
   643.8  101.27  650.83  101.62  657.87  101.97   664.9  102.34  671.94  102.66
  678.97  102.91  686.01  103.29  693.04  103.73  700.07  104.02  707.11   104.4
  714.14  104.83  721.18  105.13  728.21  105.26  735.24  105.78  742.28  106.75
  749.31  107.22  756.35  107.52  763.38  108.04  770.42  108.81  777.45  109.48
  784.48  110.05  791.52  110.71  798.55  111.55  805.59  112.11  812.62  112.64
  819.66   113.8  826.69  114.89  833.72  115.82  837.78  116.54
BR D #Mann= 4
       0     .06   345.5      .1  452.23     .04  474.27      .1
BC Design=,, 0 ,, 0 ,,,,,,
BC Use User HTab Curves=0
BC User HTab FreeFlow(D)= 0

Type RM Length L Ch R = 1 ,10619.14,108.79,102.91,91.37
BEGIN DESCRIPTION:
Lowered underwater portion by 0.5'.  No survey data available.
END DESCRIPTION:
XS GIS Cut Line= 3
1638134.70561583719446.8004351561637657.20262797719381.021962315
1637303.16645075719345.958844587
#Sta/Elev= 30
       0  113.88   14.13  113.24   35.33  111.53   77.73  110.37  127.19  108.26
  141.32  107.13  183.72   105.3  261.45  102.78  296.78  100.69  325.04   98.13
   345.5   96.87  367.44   95.73   395.7   95.68  423.97   95.08   438.1   94.26
  445.16   93.27  452.23   91.96   459.3    90.7  466.36    90.7  474.27   92.22
  478.63   93.21  489.05   94.59  503.11    95.5  538.29   96.25  714.14  104.83
  728.21  105.26  742.28  106.75  763.38  108.04  812.62  112.64  837.78  116.54
#Mann= 4 ,-1 , 0
       0     .06       0   345.5      .1       0  452.23    .045       0
  474.27      .1       0
#XS Ineff= 1 ,-1
       0  412.89  95.998
Permanent Ineff=
       F
Bank Sta=445.16,478.63
XS Rating Curve= 0 ,0
Exp/Cntr=0.5,0.3

Type RM Length L Ch R = 1 ,10516.23,355.16,362.59,367.39
XS GIS Cut Line= 4
1638150.98581988719356.780481458 1637741.2248109719274.405845627
1637622.94328251719303.9762277451637282.88388845719259.620654598
#Sta/Elev= 30
       0  113.46    7.42  113.02   21.42  112.07   42.84  111.99    71.4  110.65
  121.38  109.45   142.8  108.34   178.5  107.32  292.74  101.68  371.28   98.63
  406.98   95.14  417.96   94.43  439.61   93.84  454.04   92.13  461.25   91.32
  475.68   90.62  490.11   91.22  497.33   92.01  526.19   95.25  539.88   96.37
  575.18   97.68  631.65   99.09  666.95  101.02  716.36   102.1   744.6  103.87
  765.78  105.81  808.13  108.76  850.49  112.56  871.67  117.38  882.82  119.02
#Mann= 4 ,-1 , 0
       0     .06       0    7.42      .1       0  461.25    .045       0
  490.11      .1       0
Bank Sta=454.04,497.33
XS Rating Curve= 0 ,0
Exp/Cntr=0.3,0.1

Type RM Length L Ch R = 1 ,10153.64,263.18,269.9,262.18
XS GIS Cut Line= 2
1638222.84270145718967.9266185461637074.87109806718890.484089747
#Sta/Elev= 30
       0  110.25   14.03   108.9   63.14   108.9   98.22  106.26  147.33  103.93
  182.41  103.15  228.62  101.17  336.76   97.74  385.87   97.19     442    95.4
  463.05   93.61  498.13   91.85  505.15    91.2  516.42   88.73  519.18   88.27
  526.19   87.02  533.21   86.66  547.24   88.35  550.49   88.79   575.3   91.53
  624.42   93.28  701.59  100.74   750.7   104.3   792.8  106.61  891.02  109.97
  933.12  112.48  991.92   114.7 1017.31  116.03 1080.45  120.99 1150.58  123.61
#Mann= 5 ,-1 , 0
       0     .06       0  228.62      .1       0  519.18    .045       0
  547.24      .1       0  991.92     .06       0
Bank Sta=516.42,550.49
XS Rating Curve= 0 ,0
Exp/Cntr=0.3,0.1

Type RM Length L Ch R = 1 ,9883.739,239.46,249.85,246.7
XS GIS Cut Line= 2
1638277.97291473718755.0436158931637384.34775802718627.761694446
#Sta/Elev= 30
       0  110.96   28.28  107.87   66.53  106.13   84.85  105.65  141.41  102.38
   169.7  101.28  190.91  101.24  233.33   98.93  339.39      95   360.6   93.36
  388.89   93.89  424.24   92.78  466.66   89.19  509.09   87.59  519.08   86.73
  522.27   86.16   530.3    85.2  537.37   85.02  542.67   85.06  551.51    85.4
  561.67   86.82  572.72   87.95  622.22   89.31  657.57   91.32  671.71    93.6
  692.92   99.86  728.28  106.65  742.42  108.69  758.49  109.62  902.65  117.69
#Mann= 5 ,-1 , 0
       0     .06       0   66.53      .1       0  522.27    .045       0
  542.67      .1       0  758.49     .06       0
Bank Sta=519.08,561.67
XS Rating Curve= 0 ,0
Exp/Cntr=0.3,0.1

Type RM Length L Ch R = 1 ,9633.884,71.17,65.48,64.52
XS GIS Cut Line= 4
1638341.08113334718478.1176992651637855.09313329718456.006922066
1637773.08983484718441.8684223151637456.38744085 718439.04072237
#Sta/Elev= 30
       0  113.13   21.02  111.64   49.05  111.95  105.11  110.47  112.12  109.97
  140.14  106.43  155.21  105.46  182.19  101.47  203.21   99.38  245.25   96.44
  378.39    90.6  434.45   87.06  493.59   85.67   507.8   84.87   514.9   84.27
  522.01   82.95  529.11   82.82  536.21      84  540.27   85.19  541.26   85.64
  557.52   90.04   569.7   92.45  611.71   97.39  646.71  102.13  680.68  105.59
  702.71  108.05  737.71   110.1  758.71  112.02  821.71  116.63  886.42  120.21
#Mann= 5 ,-1 , 0
       0     .06       0  155.21      .1       0   507.8    .045       0
  540.27      .1       0  680.68     .06       0
Bank Sta=493.59,541.26
XS Rating Curve= 0 ,0
Exp/Cntr=0.5,0.3

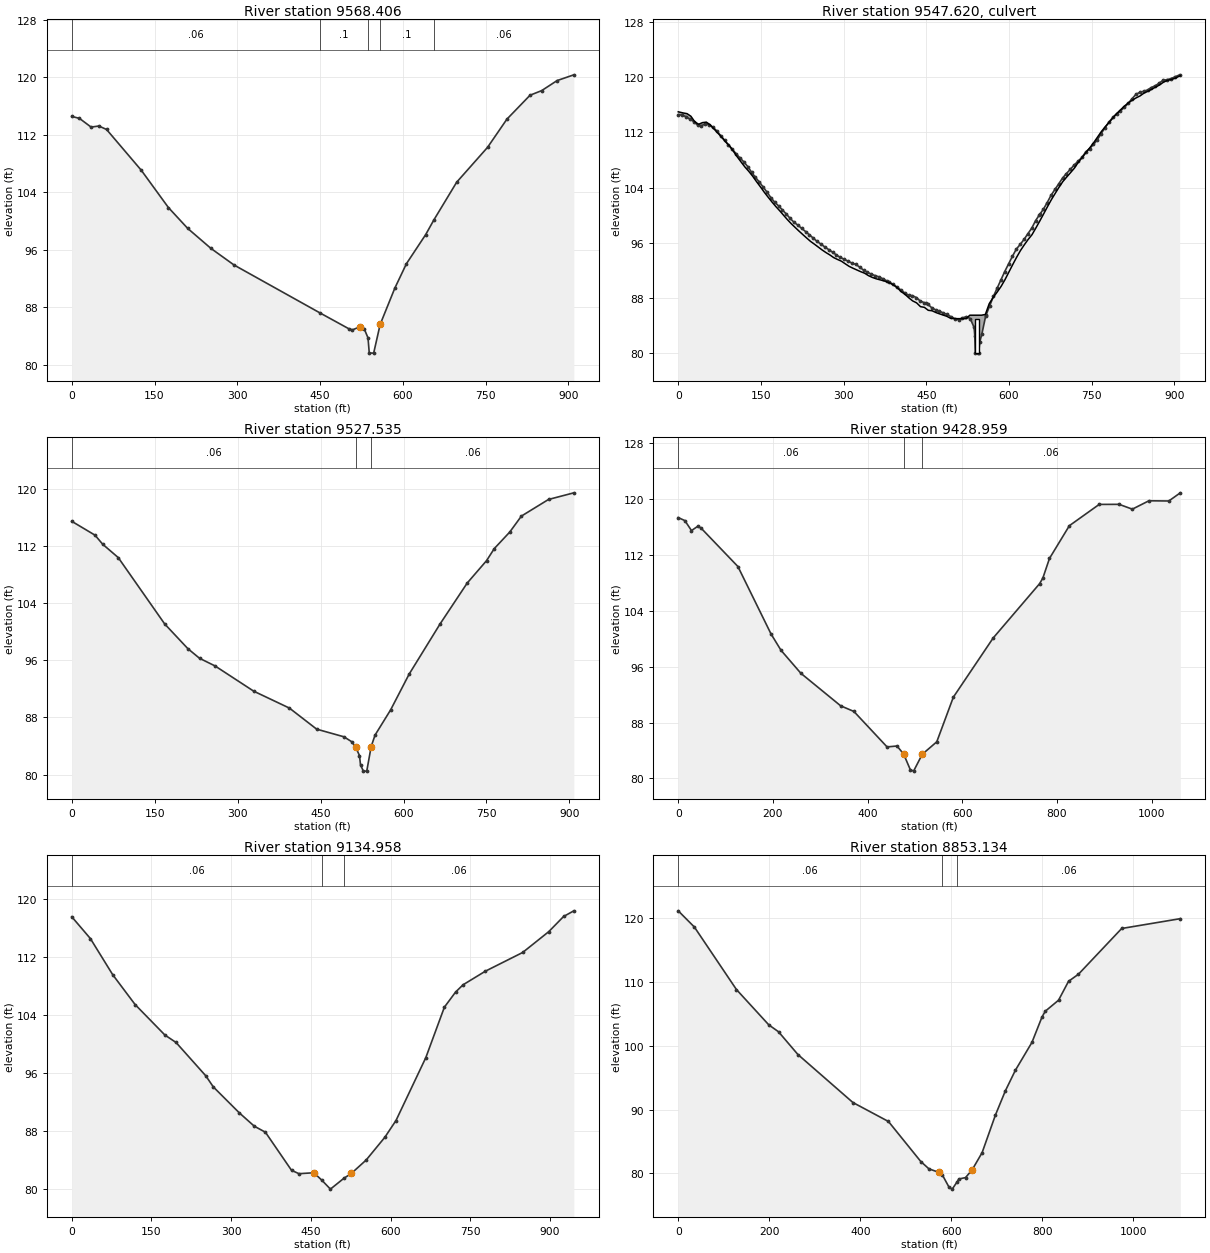
Type RM Length L Ch R = 1 ,9568.406,40.21,40.87,39.86
BEGIN DESCRIPTION:
Lowered under water portion by 1' as per bridge inspection note on flow depth
END DESCRIPTION:
XS GIS Cut Line= 5
 1638370.9037251718392.5708883851637988.48367448718402.161359876
1637898.20496713718391.0644624981637786.83656757718380.878128573
1637462.51433462718375.856229246
#Sta/Elev= 30
       0  114.57      14  114.29   35.01  113.08   49.02  113.23   63.02  112.75
  126.04  107.06  175.05  101.88  210.07   98.97  252.08   96.19  294.09   93.87
  449.48   87.21  501.62   85.01  508.64   84.84   522.7   85.29  529.73   85.01
  536.76   83.72     539   81.62     547    81.6  558.73   85.59  585.33   90.65
  606.33   94.05  641.34   98.12  656.07  100.15  697.35   105.4  753.35  110.26
  788.36  114.18  830.36  117.52  851.36  118.16  879.37  119.56  909.69  120.36
#Mann= 5 ,-1 , 0
       0     .06       0  449.48      .1       0  536.76    .045       0
  558.73      .1       0  656.07     .06       0
Bank Sta=522.7,558.73
XS Rating Curve= 0 ,0
Exp/Cntr=0.5,0.3

Type RM Length L Ch R = 2 ,9547.620,,,
BEGIN DESCRIPTION:
CE050807FS-8  Unnamed Rd  Modified internal xsection underwater portion 1.6' to account for box culvert geometry.  Assumed top of road elevation was 85.5 with 6" cover over the top of the box culvert.  Bridge Inspection viewer has conflicting dimensions for the bridge opening.  Top bank, flow width, bottom width and channel depth all =5'.  Length of span identified in the Structure Information report indicates a lenght of span =10'.  This does not seem reasonable based on photogrphs.  Assumed opening of 7ft
END DESCRIPTION:
Bridge Culvert--1,0,-1,-1, 0
Deck Dist Width WeirC Skew NumUp NumDn MinLoCord MaxHiCord MaxSubmerge Is_Ogee
15,12,2.6,0, 127, 130, , , 0.95, 0, 2,0,,
       0       9      16   23.01   30.01   37.01   44.01   51.02   58.02   65.02
   72.02   79.02   86.03   93.03  100.03  107.03  114.04  121.04  128.04  135.04
  142.04  149.05  156.05  163.05  170.05  177.05  184.06  191.06  198.06  205.06
  212.07  219.07  226.07  233.07  240.07  247.08  254.08  261.08  268.08  275.09
  282.09  289.09  296.09  303.09   310.1   317.1   324.1   331.1  338.11  345.11
  352.11  359.11  366.11  373.12  383.06  390.12  397.17  404.22  411.27  418.33
  425.38  432.43  439.49  446.54  453.59  460.64   467.7  472.86  479.89  486.91
  493.94  500.97     508  522.06  529.09  550.18  557.21  564.24  571.27  578.29
  585.76  592.76  599.76  606.76  613.76  620.76  627.76  634.76  641.77  648.77
  655.77  662.77  669.77  676.77  683.77  690.77  697.77  704.77  711.77  718.77
  725.78  732.78  739.78  746.78  753.78  760.78  767.78  774.78  781.78  788.78
  795.78  802.78  809.79  816.79  823.79  830.79  837.79  844.79  851.79  858.79
  865.79  872.79  879.79  886.79   893.8   900.8  910.88
     115  114.83  114.73  114.35  113.55  113.19  113.43   113.5   113.1   112.5
   111.9  111.29  110.66  110.05  109.28  108.47  107.72  106.99  106.36  105.66
  104.87  104.12  103.34  102.62  101.92  101.26  100.65     100   99.36   98.77
   98.23    97.7   97.19   96.69    96.2    95.8   95.38   94.96   94.58   94.24
   93.85   93.58   93.33   92.95   92.58   92.31   92.06   91.81   91.59   91.24
   90.98   90.78   90.63   90.48   90.21    89.9   89.51   88.93   88.54   88.02
   87.57   87.29   86.74   86.64   86.21   86.14   85.88   85.73   85.54   85.35
   85.06      85      85      85    85.5    85.5   85.61   87.18   88.07   88.82
   89.68   90.65   91.74   92.83   93.88   94.86    95.7   96.48   97.17   98.14
   99.14  100.17  101.22  102.23  103.15  104.05  104.88  105.54  106.18  106.83
  107.68  108.36  109.09  109.79  110.53  111.34  112.15  112.84  113.47  114.12
  114.76  115.31  115.85  116.29  116.69  117.02   117.3   117.7  117.97  118.26
  118.58  118.87  119.26  119.54  119.67  119.85  120.23
                                                                                
                                                                                
                                                                                
                                                                                
                                                                                
                                                                                
                                                                                
                                                                                
                                                                                
                                                                                
                                                                                
                                                                                
                                                        
     -10      -3       4   11.01   18.01   25.01   32.01   39.02   46.02   53.02
   60.02   67.02   74.03   81.03   88.03   95.03  102.04  109.04  116.04  123.04
  130.04  137.05  144.05  151.05  158.05  165.05  172.06  179.06  186.06  193.06
  200.07  207.07  214.07  221.07  228.07  235.08  242.08  249.08  256.08  263.09
  270.09  277.09  284.09  291.09   298.1   305.1   312.1   319.1  326.11  333.11
  340.11  347.11  354.11  361.12  371.06  378.12  385.17  392.22  399.27  406.33
  413.38  420.43  427.49  434.54  441.59  448.64   455.7  460.86  467.89  474.91
  481.94  488.97     496  503.03  510.06  517.09  524.12  531.15  538.18  545.21
  552.24  559.27  566.29  573.76  580.76  587.76  594.76  601.76  608.76  615.76
  622.76  629.77  636.77  643.77  650.77  657.77  664.77  671.77  678.77  685.77
  692.77  699.77  706.77  713.78  720.78  727.78  734.78  741.78  748.78  755.78
  762.78  769.78  776.78  783.78  790.78  797.79  804.79  811.79  818.79  825.79
  832.79  839.79  846.79  853.79  860.79  867.79  874.79   881.8   888.8  908.04
     115  114.83  114.73  114.35  113.55  113.19  113.43   113.5   113.1   112.5
   111.9  111.29  110.66  110.05  109.28  108.47  107.72  106.99  106.36  105.66
  104.87  104.12  103.34  102.62  101.92  101.26  100.65     100   99.36   98.77
   98.23    97.7   97.19   96.69    96.2    95.8   95.38   94.96   94.58   94.24
   93.85   93.58   93.33   92.95   92.58   92.31   92.06   91.81   91.59   91.24
   90.98   90.78   90.63   90.48   90.21    89.9   89.51   88.93   88.54   88.02
   87.57   87.29   86.74   86.64   86.21   86.14   85.88   85.73   85.54   85.35
   85.06      85    85.5    85.5    85.5    85.5    85.5    85.5    85.5   85.61
   87.18   88.07   88.82   89.68   90.65   91.74   92.83   93.88   94.86    95.7
   96.48   97.17   98.14   99.14  100.17  101.22  102.23  103.15  104.05  104.88
  105.54  106.18  106.83  107.68  108.36  109.09  109.79  110.53  111.34  112.15
  112.84  113.47  114.12  114.76  115.31  115.85  116.29  116.69  117.02   117.3
   117.7  117.97  118.26  118.58  118.87  119.26  119.54  119.67  119.85  120.23
                                                                                
                                                                                
                                                                                
                                                                                
                                                                                
                                                                                
                                                                                
                                                                                
                                                                                
                                                                                
                                                                                
                                                                                
                                                                                
BR Coef=-1 , 0 , 0 ,, 0 ,,,0.8,0,,0,
WSPro=,,,, 1 ,,,, 0 ,,,, 0 ,,,,-1 ,-1 ,-1 , 0 , 0 , 0 , 0 , 0
Culvert=2,5,7,20,0.015,0.4,1,8,1,80,542,80,530,Culvert #1  , 0 ,10
Culvert Bottom n=0.02
BR U #Sta/Elev= 138
       0  114.57       7  114.52      14  114.29   21.01  113.94   28.01  113.58
   35.01  113.08   42.01  112.98   49.02  113.23   56.02  113.13   63.02  112.75
   70.02  112.22   77.02  111.54   84.03  110.87   91.03  110.19   98.03  109.58
  105.03  108.91  112.04   108.3  119.04  107.73  126.04  107.06  133.04  106.24
  140.04  105.49  147.05  104.82  154.05  104.08  161.05  103.35  168.05  102.55
  175.05  101.88  182.06  101.35  189.06  100.77  196.06  100.17  203.06   99.54
  210.07   98.97  217.07   98.56  224.07   98.08  231.07   97.63  238.07   97.15
  245.08   96.67  252.08   96.19  259.08    95.8  266.08   95.39  273.09   95.01
  280.09   94.63  287.09   94.23  294.09   93.87  301.09   93.61   308.1   93.33
   315.1   93.06   322.1   92.87   329.1   92.48  336.11   92.04  343.11   91.73
  350.11   91.46  357.11   91.24  364.11   91.06  371.12   90.79  378.12   90.48
  382.54   90.29  389.59   89.99  396.65   89.58   403.7   89.17  410.75   88.74
   417.8   88.39  424.86   88.33  431.91   88.06  438.96   87.57  446.01   87.33
  449.48   87.21  453.07   87.08  460.12   86.56  467.17   86.27   473.5    86.1
  480.53   85.84  487.56   85.61  494.59   85.29  501.62   85.01  508.64   84.84
  515.67   85.11   522.7   85.29  529.73   85.01  536.76   83.72  537.99   82.53
     539      80  543.79      80     545      80     547    81.6  550.82   82.75
  557.85   85.41  558.73   85.59  564.88   86.85  571.91   88.25  578.94   89.49
  585.33   90.65  592.33   91.83  599.33   92.94  606.33   94.05  613.33   95.08
  620.34   95.76  627.34   96.49  634.34   97.32  641.34   98.12  648.34   99.22
  655.34  100.07  656.07  100.15  662.34  100.85  669.34  101.83  676.34  102.88
  683.34  103.73  690.34  104.55  697.35   105.4  704.35  106.05  711.35  106.65
  718.35  107.28  725.35  107.82  732.35  108.38  739.35  109.18  746.35  109.67
  753.35  110.26  760.35  110.94  767.35  111.85  774.35  112.71  781.36   113.5
  788.36  114.18  795.36  114.72  802.36  115.15  809.36  115.64  816.36  116.23
  823.36   116.9  830.36  117.52  837.36  117.82  844.36  117.97  851.36  118.16
  858.36  118.52  865.37  118.77  872.37  119.14  879.37  119.56  886.37  119.65
  893.37  119.79  900.37  120.03  909.69  120.36
BR U #Mann= 5
       0     .06  449.48      .1  537.99    .035  558.73      .1  656.07     .06
BR D #Sta/Elev= 134
       0  115.48       7  115.19      14  114.87   21.01  114.57   28.01  114.21
   35.01  113.88   42.01  113.54   49.02   112.9   56.02  112.26   63.02  111.84
   70.02  111.43   77.02  110.98   84.03   110.4   91.03  109.75   98.03  109.05
  105.03  108.22  112.04   107.4  119.04  106.65  126.04  105.86  133.04  105.01
  140.04  104.24  147.05  103.48  154.05  102.66  161.05  101.84  168.05   101.1
  175.05  100.51  182.06   99.93  189.06   99.28  196.06   98.71  203.06   98.18
  210.07   97.63  217.07   97.24  224.07   96.73  231.07   96.29  238.07   96.05
  245.08   95.71  252.08   95.45  259.08   95.22  266.08   94.85  273.09   94.41
  280.09      94  287.09   93.67  294.09   93.34  301.09   92.94   308.1   92.65
   315.1   92.41   322.1   92.09   329.1   91.68  336.11    91.4  343.11   91.19
  350.11   90.91  357.11   90.61  364.11   90.25  371.12   90.02  379.59   89.84
  386.63   89.62  393.66   89.31   400.7   88.88  407.74   88.41  414.78   88.02
  421.82   87.69  428.86   87.25   435.9   86.74  442.93   86.36  449.97   86.21
  457.01      86  464.05   85.82  471.09    85.7  478.13    85.6  485.17   85.46
  492.21   85.29  499.24   85.04  506.28    84.6  513.32   83.86  520.36   82.66
  522.21   81.35   527.4      80   533.5      80  534.44   81.01  541.48   83.92
  542.92   84.25  548.51   85.53  555.55   86.49  562.59   87.35  569.63   88.18
  576.67   89.06  582.16   89.85  589.16   90.92  596.16   92.04  603.16   93.07
  610.16   94.07  617.17   94.95  624.17   95.75  631.17    96.6  638.17   97.48
  645.17   98.33  652.17   99.23  659.17  100.19  666.17  101.11  673.17  101.94
  680.17  102.67  687.17  103.39  694.17  104.21  701.18  105.12  708.18  106.02
  715.18  106.83  722.18  107.48  729.18  108.06  736.18  108.79  743.18  109.35
  750.18  109.97  757.18  110.92  764.18  111.66  771.18  112.26  778.18  112.89
  785.19  113.43  792.19  113.98  799.19  114.73  806.19  115.62  813.19  116.21
  820.19  116.45  827.19  116.67  834.19  117.09  841.19  117.51  848.19  117.79
  855.19  118.18   862.2  118.54   869.2  118.65   876.2  118.79   883.2  118.92
   890.2  118.95   897.2  119.06   904.2  119.31  908.04  119.47
BR D #Mann= 3
       0     .06  522.21    .035  542.92     .06
BC Design=,, 0 ,, 0 ,,,,,,
BC Use User HTab Curves=0
BC User HTab FreeFlow(D)= 0

Type RM Length L Ch R = 1 ,9527.535,93.88,98.57,90.01
BEGIN DESCRIPTION:
Lowered under water portion by 1' as per bridge inspection note on flow depth.
END DESCRIPTION:
XS GIS Cut Line= 4
1638369.90090559718352.583460957 1637990.4328301718362.099901691
1637788.97097485718340.9063833651637463.13363191718335.861023664
#Sta/Elev= 30
       0  115.48   42.01  113.54   56.02  112.26   84.03   110.4  168.05   101.1
  210.07   97.63  231.07   96.29  259.08   95.22   329.1   91.68  393.66   89.31
  442.93   86.36  492.21   85.29  506.28    84.6  513.32   83.86  520.36   82.66
  522.21   81.35   527.4   80.48   533.5   80.48  541.48   83.92  548.51   85.53
  576.67   89.06  610.16   94.07  666.17  101.11  715.18  106.83  750.18  109.97
  764.18  111.66  792.19  113.98  813.19  116.21   862.2  118.54  908.04  119.47
#Mann= 3 , 0 , 0
       0     .06       0  513.32    .045       0  541.48     .06       0
Bank Sta=513.32,541.48
XS Rating Curve= 0 ,0
Exp/Cntr=0.5,0.3

Type RM Length L Ch R = 1 ,9428.959,253.88,294,278.87
XS GIS Cut Line= 2
 1638389.6610468718275.3493649071637329.35163169718250.003323093
#Sta/Elev= 30
       0  117.37      14  116.94   28.01  115.51   42.01  116.16   49.01  115.81
  126.04  110.36  196.06  100.69  217.06   98.36  259.07   95.06   343.1    90.4
  371.11   89.59  441.13   84.51  462.13   84.64  476.14   83.49  490.14   81.26
  497.14   81.04  515.56   83.46  546.16   85.24  581.17   91.64  665.19  100.11
  763.22  107.89  770.22   108.7  784.23  111.52  826.24  116.21  889.26  119.26
  931.27  119.27  959.28  118.58  994.29  119.78  1036.3  119.75 1060.61  120.92
#Mann= 3 , 0 , 0
       0     .06       0  476.14    .045       0  515.56     .06       0
Bank Sta=476.14,515.56
XS Rating Curve= 0 ,0
Exp/Cntr=0.3,0.1

Type RM Length L Ch R = 1 ,9134.958,299.8,281.82,243.75
XS GIS Cut Line= 4
1638397.29971606718036.4311011281637935.90275091718012.565740868
1637893.47544372717986.0486738981637461.24725223718009.914034158
#Sta/Elev= 30
       0  117.53   35.05  114.52    77.1  109.53  119.16  105.42  175.23  101.21
  196.26  100.18  252.34   95.57  266.36   94.05  315.42   90.46  343.46   88.63
  364.49   87.79  413.55   82.54  427.57   82.07  455.61    82.2  470.27    81.2
  486.78   79.94  512.05   81.43  526.07    82.1  554.11   83.96  589.16   87.09
   610.2   89.41  666.28   98.08  701.33  105.06  722.37  107.14  736.39  108.14
  778.45  110.02  848.56   112.6  897.63  115.47  925.68  117.57  944.93  118.35
#Mann= 3 ,-1 , 0
       0     .06       0  470.27    .045       0  512.05     .06       0
Bank Sta=455.61,526.07
XS Rating Curve= 0 ,0
Exp/Cntr=0.3,0.1

Type RM Length L Ch R = 1 ,8853.134,43.58,73.73,88.04
XS GIS Cut Line= 3
1638480.47087216717812.0284829441637937.82083252717716.617486939
  1637408.339498 717873.89655064
#Sta/Elev= 30
       0  121.19   35.54  118.64  127.93  108.84  199.01   103.3  220.33  102.22
  262.97   98.65   383.8   91.12  461.98   88.14  533.05   81.86  550.97   80.71
  572.88   80.16  580.18   79.79  594.79   77.87  602.09   77.53  612.23   78.61
  616.69   79.12   631.3   79.34   645.9   80.56  667.81   83.26  697.02   89.15
  718.93   92.96  740.83   96.17  777.34  100.56  799.25  104.51  806.55  105.44
  835.76  107.17  857.67  110.13  879.58  111.25  974.51  118.42 1103.32  119.96
#Mann= 3 ,-1 , 0
       0     .06       0  580.18    .045       0  612.23     .06       0
Bank Sta=572.88,645.9
XS Rating Curve= 0 ,0
Exp/Cntr=0.5,0.3