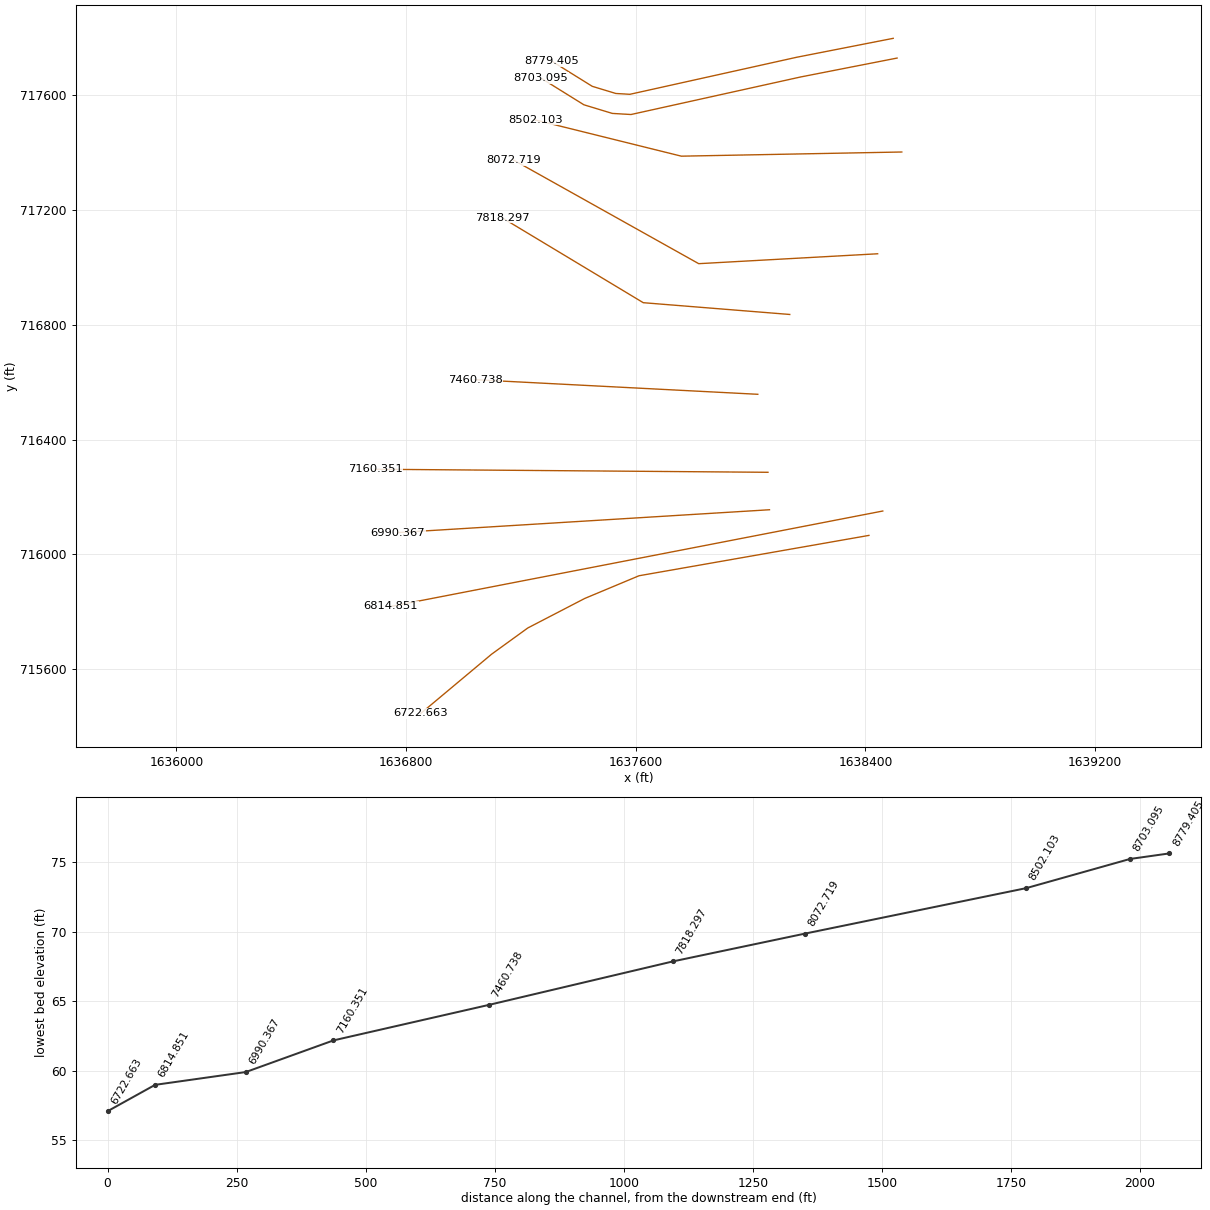
HEC-RAS study Dogwood.prj: Dogwood Run

--- Dogwood.g13 (geometry) --- (continued)

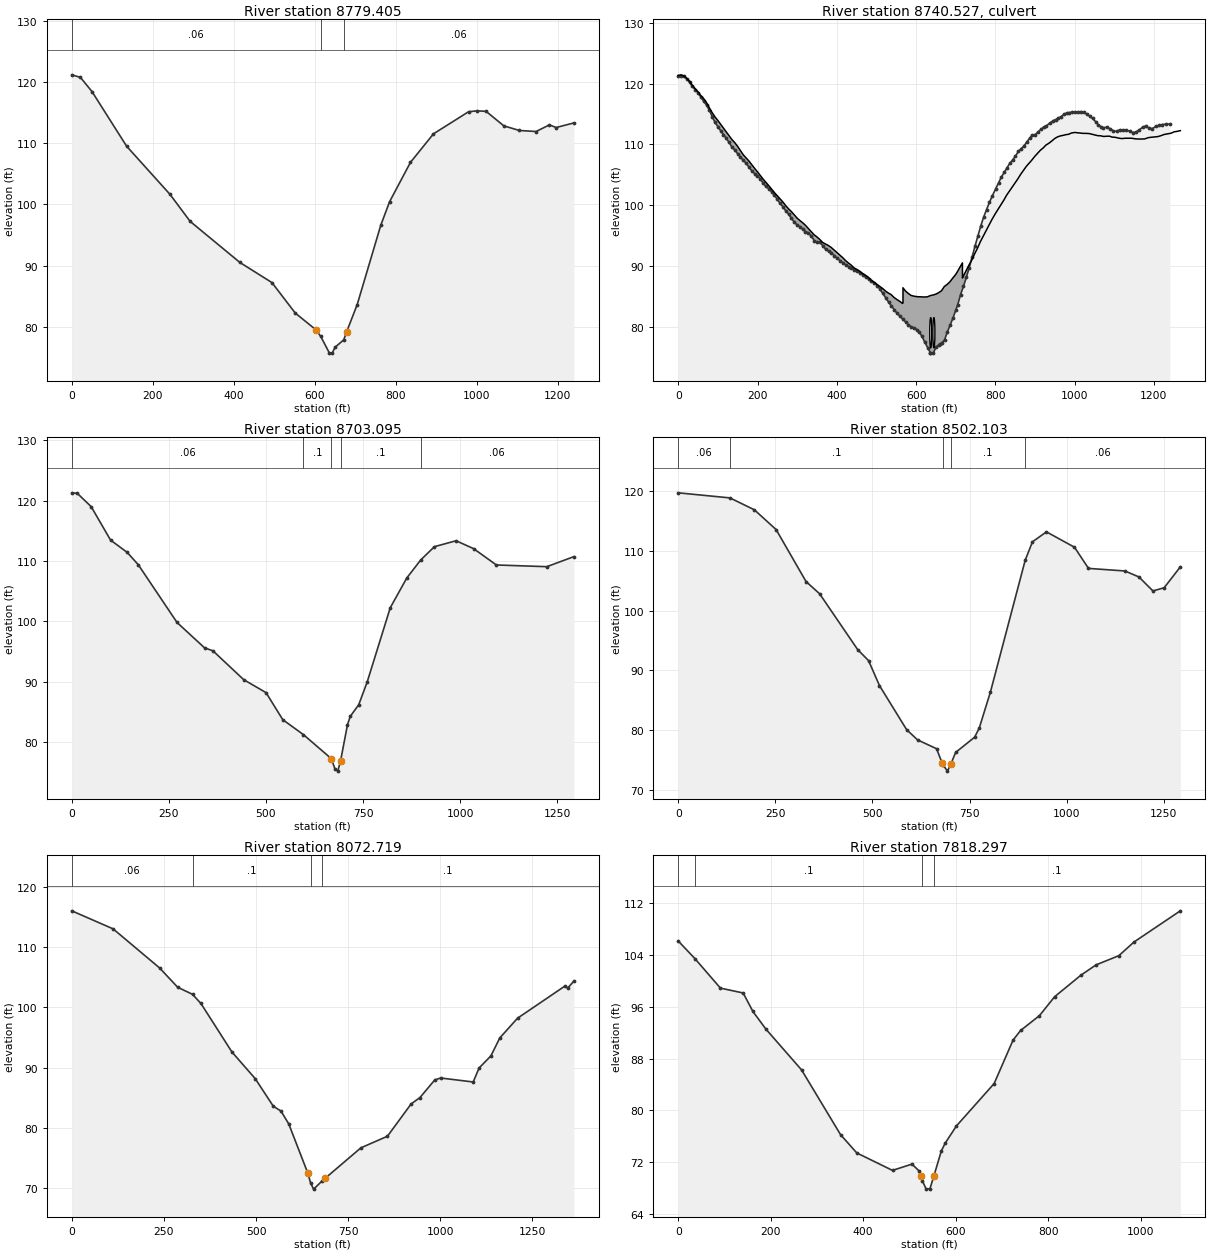
Type RM Length L Ch R = 1 ,8779.405,88,76.31,73.87
BEGIN DESCRIPTION:
Lowered under water portion -0.5 ft
END DESCRIPTION:
XS GIS Cut Line= 6
1638496.59534079717797.6751193551638159.65241113717731.608798027
1637579.41065092717602.7377803031637530.59139828717605.594423577
1637448.50022663717630.5027998541637306.27631876717718.923241183
#Sta/Elev= 30
       0  121.25    21.4  120.83   49.93  118.51  135.53  109.55  242.53  101.67
  292.46   97.23  415.32    90.5  494.49    87.2  552.06   82.21  602.43    79.5
  614.88    78.4  636.23   75.68  643.35   75.64  650.47   76.61  671.82   77.81
  678.94   79.12  705.12    83.6   763.3   96.59  785.11  100.46  836.64   106.9
   893.5  111.58  980.19   115.2 1001.65  115.35  1023.6  115.26 1067.49  112.88
 1105.78  112.13 1146.99  111.96 1179.96  113.05 1196.45  112.61 1240.28  113.37
#Mann= 3 ,-1 , 0
       0     .06       0  614.88    .045       0  671.82     .06       0
Bank Sta=602.43,678.94
XS Rating Curve= 0 ,0
Exp/Cntr=0.5,0.3

Type RM Length L Ch R = 2 ,8740.527,,,
BEGIN DESCRIPTION:
CE050807FS-7  Carriage Lane  Culvert   Top of road from lidar.  Invert at approx water surface.  Invert is above channel bottom.  Assumed 2x  60" culvert.  Added 2.5' railing as indicated in bridge inspection notes.
END DESCRIPTION:
Bridge Culvert--1,0,-1,-1, 0
Deck Dist Width WeirC Skew NumUp NumDn MinLoCord MaxHiCord MaxSubmerge Is_Ogee
25,28,2.6,0, 179, 179, , , 0.95, 0, 0,0,,
       0    7.13   14.27    21.4   28.53   35.67    42.8   49.93   57.07    64.2
   71.33   78.47    85.6   92.73   99.87     107  114.13  121.27   128.4  135.53
  142.67   149.8  156.93  164.07   171.2  178.33  185.47   192.6  199.73  206.87
     214  221.13  228.27   235.4  242.53  249.67   256.8  263.93  271.07   278.2
  285.33  292.46   299.6  306.73  313.86     321  328.13  335.26  342.65  349.84
  357.04  364.24  371.43  378.63  385.83  393.02  400.22  407.42  414.61  421.81
  429.01   436.2   443.4   450.6  457.79  464.99  472.19  479.38  486.58  493.78
  500.97  508.17  515.37  522.56  529.76  536.95  544.15  551.35  558.54  565.74
  566.99     567  572.94  580.13  587.33  594.53  601.72  607.24  614.36  621.48
   628.6  635.71  642.83  649.95  657.07  664.19  671.31  678.42  685.54  692.66
  699.78   703.9  711.17     717  717.01  718.44  725.71  732.99  740.26  747.53
   754.8  762.08  769.35  776.62  783.89  791.16  800.01  807.12  814.23  821.34
  828.44  835.55  842.66  849.77  856.88  863.98  871.09   878.2  885.31  892.42
  899.52  906.63  913.74  920.85  927.96  935.07  942.88  949.89   956.9  963.92
  970.93  977.94  984.95  991.96 1000.03 1007.35 1014.66 1021.98 1029.29 1036.61
 1043.92 1051.24 1058.55 1065.87 1073.18  1080.5 1087.81 1094.58 1102.82 1111.06
  1119.3 1127.55 1135.79 1144.03 1152.27 1160.52 1168.76    1177 1185.24 1193.49
 1201.73 1209.97 1218.21 1226.46  1234.7 1242.94 1251.18 1259.43 1266.65
  121.35  121.46  121.28  120.87  120.41  119.71  119.18  118.66  118.03  117.54
  116.88  116.03  115.23  114.53  113.95  113.32  112.68  112.07  111.41  110.79
  110.29  109.68  108.98  108.29  107.78  107.27  106.65  106.06   105.5  104.89
   104.3  103.77  103.22  102.65  102.08  101.56  101.04  100.53   99.93    99.4
   98.95   98.43   97.89   97.48   97.11   96.68   96.17   95.67   95.13   94.77
   94.36   93.86   93.62   93.36   93.04   92.63   92.24   91.82   91.38    90.9
   90.49   90.14   89.68   89.42   89.13   88.77   88.47   88.13   87.67   87.32
   86.95   86.63    86.3   85.88   85.54   85.29   84.82   84.48   84.18   83.83
    83.9    86.4   85.89   85.48   85.14   85.02   84.94   84.92   84.88   84.88
   84.91   85.11   85.21   85.35    85.6   85.91   86.61   86.95   87.39   88.01
   88.57   89.01   89.84    90.5      88   88.22   89.15   90.08   90.93   91.96
   92.89   93.97   94.89   95.78    96.7   97.61   98.61   99.35  100.11  100.82
  101.64  102.31  102.99  103.64  104.34  105.09  105.73  106.39  106.91  107.45
  108.04  108.54  109.05  109.43  109.91  110.19  110.59  110.98  111.24   111.4
  111.49  111.61  111.67  111.88  111.97  111.92  111.88  111.82  111.82  111.79
  111.67  111.54  111.44  111.42  111.31  111.35  111.36  111.21  111.17  111.04
  110.96  111.02  111.02  111.02  110.93  110.89  110.89  110.91  111.11  111.18
  111.23  111.29  111.45  111.65  111.75  111.84  112.08  112.16  112.27
                                                                                
                                                                                
                                                                                
                                                                                
                                                                                
                                                                                
                                                                                
                                                                                
                                                                                
                                                                                
                                                                                
                                                                                
                                                                                
                                                                                
                                                                                
                                                                                
                                                                                
                                                                        
       0    7.13   14.27    21.4   28.53   35.67    42.8   49.93   57.07    64.2
   71.33   78.47    85.6   92.73   99.87     107  114.13  121.27   128.4  135.53
  142.67   149.8  156.93  164.07   171.2  178.33  185.47   192.6  199.73  206.87
     214  221.13  228.27   235.4  242.53  249.67   256.8  263.93  271.07   278.2
  285.33  292.46   299.6  306.73  313.86     321  328.13  335.26  342.65  349.84
  357.04  364.24  371.43  378.63  385.83  393.02  400.22  407.42  414.61  421.81
  429.01   436.2   443.4   450.6  457.79  464.99  472.19  479.38  486.58  493.78
  500.97  508.17  515.37  522.56  529.76  536.95  544.15  551.35  558.54  565.74
  566.99     567  572.94  580.13  587.33  594.53  601.72  607.24  614.36  621.48
   628.6  635.71  642.83  649.95  657.07  664.19  671.31  678.42  685.54  692.66
  699.78   703.9  711.17     717  717.01  718.44  725.71  732.99  740.26  747.53
   754.8  762.08  769.35  776.62  783.89  791.16  800.01  807.12  814.23  821.34
  828.44  835.55  842.66  849.77  856.88  863.98  871.09   878.2  885.31  892.42
  899.52  906.63  913.74  920.85  927.96  935.07  942.88  949.89   956.9  963.92
  970.93  977.94  984.95  991.96 1000.03 1007.35 1014.66 1021.98 1029.29 1036.61
 1043.92 1051.24 1058.55 1065.87 1073.18  1080.5 1087.81 1094.58 1102.82 1111.06
  1119.3 1127.55 1135.79 1144.03 1152.27 1160.52 1168.76    1177 1185.24 1193.49
 1201.73 1209.97 1218.21 1226.46  1234.7 1242.94 1251.18 1259.43 1293.02
  121.35  121.46  121.28  120.87  120.41  119.71  119.18  118.66  118.03  117.54
  116.88  116.03  115.23  114.53  113.95  113.32  112.68  112.07  111.41  110.79
  110.29  109.68  108.98  108.29  107.78  107.27  106.65  106.06   105.5  104.89
   104.3  103.77  103.22  102.65  102.08  101.56  101.04  100.53   99.93    99.4
   98.95   98.43   97.89   97.48   97.11   96.68   96.17   95.67   95.13   94.77
   94.36   93.86   93.62   93.36   93.04   92.63   92.24   91.82   91.38    90.9
   90.49   90.14   89.68   89.42   89.13   88.77   88.47   88.13   87.67   87.32
   86.95   86.63    86.3   85.88   85.54   85.29   84.82   84.48   84.18   83.83
    83.9    86.4   85.89   85.48   85.14   85.02   84.94   84.92   84.88   84.88
   84.91   85.11   85.21   85.35    85.6   85.91   86.61   86.95   87.39   88.01
   88.57   89.01   89.84    90.5      88   88.22   89.15   90.08   90.93   91.96
   92.89   93.97   94.89   95.78    96.7   97.61   98.61   99.35  100.11  100.82
  101.64  102.31  102.99  103.64  104.34  105.09  105.73  106.39  106.91  107.45
  108.04  108.54  109.05  109.43  109.91  110.19  110.59  110.98  111.24   111.4
  111.49  111.61  111.67  111.88  111.97  111.92  111.88  111.82  111.82  111.79
  111.67  111.54  111.44  111.42  111.31  111.35  111.36  111.21  111.17  111.04
  110.96  111.02  111.02  111.02  110.93  110.89  110.89  110.91  111.11  111.18
  111.23  111.29  111.45  111.65  111.75  111.84  112.08  112.16  112.27
                                                                                
                                                                                
                                                                                
                                                                                
                                                                                
                                                                                
                                                                                
                                                                                
                                                                                
                                                                                
                                                                                
                                                                                
                                                                                
                                                                                
                                                                                
                                                                                
                                                                                
                                                                        
BR Coef=-1 , 0 , 0 ,, 0 ,,,0.8,0,,0,
WSPro=,,,, 1 ,,,, 0 ,,,, 0 ,,,,-1 ,-1 ,-1 , 0 , 0 , 0 , 0 , 0
Culvert=1,5,,48,0.021,0.5,1,2,1,76.5,637,76.2,677,Culvert #1  , 0 ,20
Culvert Bottom n=0.021
Culvert=1,5,,48,0.021,0.5,1,2,1,76.5,645,76.2,685,Culvert #2  , 0 ,20
Culvert Bottom n=0.021
BR U #Sta/Elev= 173
       0  121.25    7.13  121.32   14.27  121.22    21.4  120.83   28.53  120.23
   35.67  119.55    42.8  119.04   49.93  118.51   57.07  117.81    64.2  117.11
   71.33  116.48   78.47  115.63    85.6  114.59   92.73  113.65   99.87  112.93
     107  112.26  114.13  111.59  121.27     111   128.4  110.32  135.53  109.55
  142.67  109.09   149.8  108.49  156.93  107.87  164.07   107.4   171.2  106.92
  178.33  106.28  185.47  105.65   192.6   105.2  199.73  104.84  206.87  104.33
     214  103.66  221.13  103.08  228.27  102.71   235.4  102.21  242.53  101.67
  249.67  100.97   256.8  100.32  263.93   99.75  271.07   99.08   278.2   98.53
  285.33   97.86  292.46   97.23   299.6   96.75  306.73   96.43  313.86   96.05
     321   95.66  328.13   95.43  335.26   94.95  343.36   94.14  350.56   93.89
  357.75   93.87  364.95   93.31  372.15   92.71  379.34   92.43  386.54   92.13
  393.73   91.69  400.93   91.23  408.13   90.89  415.32    90.5  422.52   90.18
  429.72   89.88  436.91   89.61  444.11   89.39  451.31   89.16   458.5   88.86
   465.7    88.5   472.9   88.14  480.09   87.85  487.29   87.54  494.49    87.2
  501.68   86.77  508.88   86.17  516.08   85.47  523.27   84.77  530.47   84.06
  537.67   83.41  544.86   82.79  552.06   82.21  559.26   81.72  566.45   81.23
  573.65   80.77  580.85   80.31  588.04   79.93  595.24   79.76  602.43    79.5
  607.76   79.14  614.88    78.4     622   77.45  629.11   76.55  636.23   75.68
  636.39   75.68  643.35   75.64  650.47   76.61  657.59   77.04  661.19   77.17
   664.7   77.29  671.82   77.81  678.94   79.12  686.06   80.29  693.18   81.42
   700.3   82.72  705.12    83.6  712.39   85.29  719.66   86.64  726.94   88.13
  734.21   89.73  741.48   91.51  748.75   93.27  756.03   94.96   763.3   96.59
  770.57   98.04  777.84   99.28  785.11  100.46  792.39  101.54  801.09  102.71
   808.2  103.66  815.31  104.65  822.42  105.38  829.53  106.16  836.64   106.9
  843.74  107.46  850.85  108.08  857.96  108.84  865.07  109.28  872.18  109.75
  879.28  110.37  886.39  111.01   893.5  111.58  900.61  111.61  907.72  112.04
  914.82  112.47  921.93  112.85  929.04  113.08  938.12  113.53  945.13  113.88
  952.14  114.09  959.15  114.33  966.17  114.59  973.18  114.94  980.19   115.2
  987.02  115.24  994.34   115.3 1001.65  115.35 1008.97  115.36 1016.28   115.4
  1023.6  115.26 1030.91  114.98 1038.23  114.65 1045.54  114.27 1052.86  113.76
 1060.17  113.21 1067.49  112.88 1072.81  112.73 1081.05  112.86 1089.29  112.59
 1097.53  112.26 1105.78  112.13 1114.02  112.41 1122.26  112.31 1130.51  112.35
 1138.75  112.18 1146.99  111.96 1155.23  112.06 1163.48  112.41 1171.72  112.85
 1179.96  113.05  1188.2  112.66 1196.45  112.61 1204.69  112.97 1212.93  113.13
 1221.17  113.28 1229.42  113.32 1240.28  113.37
BR U #Mann= 3
       0     .06  614.88    .035  671.82     .06
BR D #Sta/Elev= 182
       0  121.29    7.13  121.35   14.27   121.2    21.4  120.78   28.53   120.4
   35.67  120.03    42.8  119.55   49.93  119.01   57.07  118.41    64.2  117.76
   71.33  116.96   78.47  115.98    85.6  115.02   92.73   114.1   99.87  113.47
     107   113.1  114.13  112.73  121.27  112.38   128.4   112.1  135.53  111.79
  142.67  111.44   149.8  111.02  156.93   110.5  164.07  109.96   171.2   109.4
  178.33  108.74  185.47     108   192.6  107.28  199.73  106.63  206.87  105.93
     214   105.2  221.13   104.6  228.27  104.04   235.4  103.34  242.53  102.56
  249.67  101.83   256.8  101.17  263.93  100.51  271.07   99.84   278.2   99.39
  285.33   99.08  292.46   98.62   299.6   98.15  306.73   97.74  313.86   97.28
     321   96.81  328.13   96.42  335.26   96.02  341.94   95.64  349.13   95.37
  356.33   95.26  363.53   95.15  370.72   94.62  377.92   94.03  385.12   93.45
  392.31   93.07  399.51   92.68  406.71   92.27   413.9   91.94   421.1    91.6
   428.3   91.24  435.49   90.79  442.69   90.38  449.88    90.1  457.08   89.78
  464.28   89.54  471.47   89.49  478.67   89.41  485.87   88.96  493.06   88.52
  500.26   88.23  507.46    87.8  514.65   86.87  521.85   85.88  529.05    85.2
  536.24    84.5  543.44   83.75  550.64   83.31  557.83   82.94  565.03   82.66
  572.23   82.34  579.42   81.95  586.62   81.74  593.82   81.47   596.6   81.28
  601.01   80.98  606.72   80.63  613.84   80.23  620.96   79.95  628.08   79.62
   635.2    79.1  642.31   78.84  649.43    78.5  656.55   78.08  663.67   77.79
  668.36   77.31  670.79   77.06  677.91   75.59  685.02   75.24  689.44      76
  689.57      76  692.14    76.9  702.68   80.62  709.95   82.88  717.22    84.3
  724.49   85.13  731.76   85.57  739.04   86.23  746.31   87.46  753.58   88.79
  760.85      90  768.13   91.39   775.4   92.85  782.67   94.68  789.94    96.3
  798.93    98.1  806.04   99.53  813.14  101.04  820.25  102.28  827.36  103.21
  834.47  104.16  841.58  104.83  848.68  105.61  855.79  106.39   862.9  107.21
  870.01   107.8  877.12  108.35  884.22   108.9  891.33  109.48  898.44  110.16
  898.78  110.19  905.55   110.7  912.66  111.13  919.77  111.43  926.87  111.99
  933.98  112.38  941.09  112.38  947.64  112.52  954.65  112.63  961.67  112.84
  968.68  113.08  975.69  113.15   982.7  113.25  989.71  113.36  996.73  113.18
 1003.74  112.58 1013.04  112.39 1020.36  112.42 1027.67  112.22 1034.99  112.05
 1042.31  111.76 1049.62  111.39 1056.94  111.02 1064.25  110.58 1071.57  110.13
 1078.88  109.78  1086.2  109.52 1093.51  109.35 1100.83  109.34 1108.14  109.26
 1116.35  109.34 1124.59  109.39 1132.83  109.23 1141.07  109.15 1149.32  109.13
 1157.56  109.15  1165.8  109.23 1174.04   109.2 1182.29  109.08 1190.53  109.03
 1198.77  109.06 1207.01  109.13 1215.26  109.25  1223.5  109.07 1231.74  109.22
 1239.98  109.44 1248.23  109.73 1256.47  109.84 1264.71  110.06 1272.95  110.28
  1281.2  110.48 1293.02  110.73
BR D #Mann= 5
       0     .06   596.6      .1  668.36    .035  692.14      .1  898.78     .06
BC Design=,, 0 ,, 0 ,,,,,,
BC Use User HTab Curves=0
BC User HTab FreeFlow(D)= 0

Type RM Length L Ch R = 1 ,8703.095,212.68,200.99,199.55
BEGIN DESCRIPTION:
Lowered under water portion -0.5 ft
END DESCRIPTION:
XS GIS Cut Line= 6
1638510.06417248717728.9831214851638174.51711378717663.190496519
1637583.50341782717532.3785568331637518.21279398717536.199017257
1637419.36279334717566.1924131511637269.31761844717659.475327238
#Sta/Elev= 30
       0  121.29   14.27   121.2   49.93  119.01   99.87  113.47  142.67  111.44
   171.2   109.4  271.07   99.84  341.94   95.64  363.53   95.15  442.69   90.38
  500.26   88.23  543.44   83.75   596.6   81.28  668.36   77.31  677.91   75.59
  685.02   75.24  692.14    76.9  709.95   82.88  717.22    84.3  739.04   86.23
  760.85      90  820.25  102.28   862.9  107.21  898.78  110.19  933.98  112.38
  989.71  113.36 1034.99  112.05 1093.51  109.35  1223.5  109.07 1293.02  110.73
#Mann= 5 ,-1 , 0
       0     .06       0   596.6      .1       0  668.36    .045       0
  692.14      .1       0  898.78     .06       0
Bank Sta=668.36,692.14
XS Rating Curve= 0 ,0
Exp/Cntr=0.5,0.3

Type RM Length L Ch R = 1 ,8502.103,403.91,429.38,323.45
XS GIS Cut Line= 3
1638526.43710721717401.8108934311637758.76365334717387.280796513
1637249.32117137717513.620654359
#Sta/Elev= 30
       0  119.69  133.15  118.84  196.04  116.85  252.05  113.54  329.06  104.85
  364.07   102.8  462.08   93.46  490.09   91.62  518.09   87.45  588.11   80.07
  616.11   78.37  665.12   76.89  679.12   74.55  681.63    74.2  693.12   73.14
  702.06   74.36  714.13   76.26  763.14   78.82  775.02   80.34  803.87   86.39
  893.38  108.43  912.05   111.5  948.11  113.16 1020.23  110.59 1056.29  107.05
 1150.05  106.62 1186.11  105.62 1222.17  103.28 1251.02  103.81 1292.69   107.3
#Mann= 5 ,-1 , 0
       0     .06       0  133.15      .1       0  681.63    .045       0
  702.06      .1       0  893.38     .06       0
Bank Sta=679.12,702.06
XS Rating Curve= 0 ,0
Exp/Cntr=0.3,0.1

Type RM Length L Ch R = 1 ,8072.719,193.14,254.42,212.71
XS GIS Cut Line= 3
1638442.37872989717047.3445033581637819.22765626717012.872316301
  1637174.862929717373.504427016
#Sta/Elev= 30
       0  115.99  112.17     113  238.36  106.52  287.44  103.32  327.69  102.15
  350.54  100.63  434.66   92.59  497.76   88.18  546.83   83.61  567.87   82.79
   588.9   80.66  640.15   72.58  648.17   70.89  656.19   69.86  680.26   71.26
  688.28   71.69  784.54    76.7  856.73   78.63  920.91   83.98  944.97   85.04
  985.08   87.96 1001.12   88.28 1089.36   87.62 1105.41   89.94 1137.49   91.95
 1161.56   94.92 1209.69   98.19 1338.04  103.51 1346.06   103.2 1362.52  104.34
#Mann= 4 ,-1 , 0
       0     .06       0  327.69      .1       0  648.17    .045       0
  680.26      .1       0
Bank Sta=640.15,688.28
XS Rating Curve= 0 ,0
Exp/Cntr=0.3,0.1

Type RM Length L Ch R = 1 ,7818.297,306.22,357.56,343.64
XS GIS Cut Line= 3
1638136.28928691716835.979355142 1637626.0796854716876.978340968
1637134.09185535717173.082127571
#Sta/Elev= 30
       0  106.14   35.95  103.43   91.29   98.87  140.45   98.12  161.52   95.27
  189.61   92.55  266.86   86.25  351.13   76.27  386.24   73.45  463.49   70.76
  505.62   71.73  520.02   70.74  524.93   69.84  528.19   69.15  536.36   67.87
  544.53   67.94  552.92   69.88  569.04   73.74  577.21   74.93  601.72   77.61
  683.42   84.16  724.27   90.85  740.61   92.34  781.46   94.63  814.14   97.54
  871.33  100.88  904.01  102.46  953.03  103.87  985.71  105.97 1086.07  110.79
#Mann= 4 ,-1 , 0
       0     .06       0   35.95      .1       0  528.19    .045       0
  552.92      .1       0
Bank Sta=524.93,552.92
XS Rating Curve= 0 ,0
Exp/Cntr=0.3,0.1

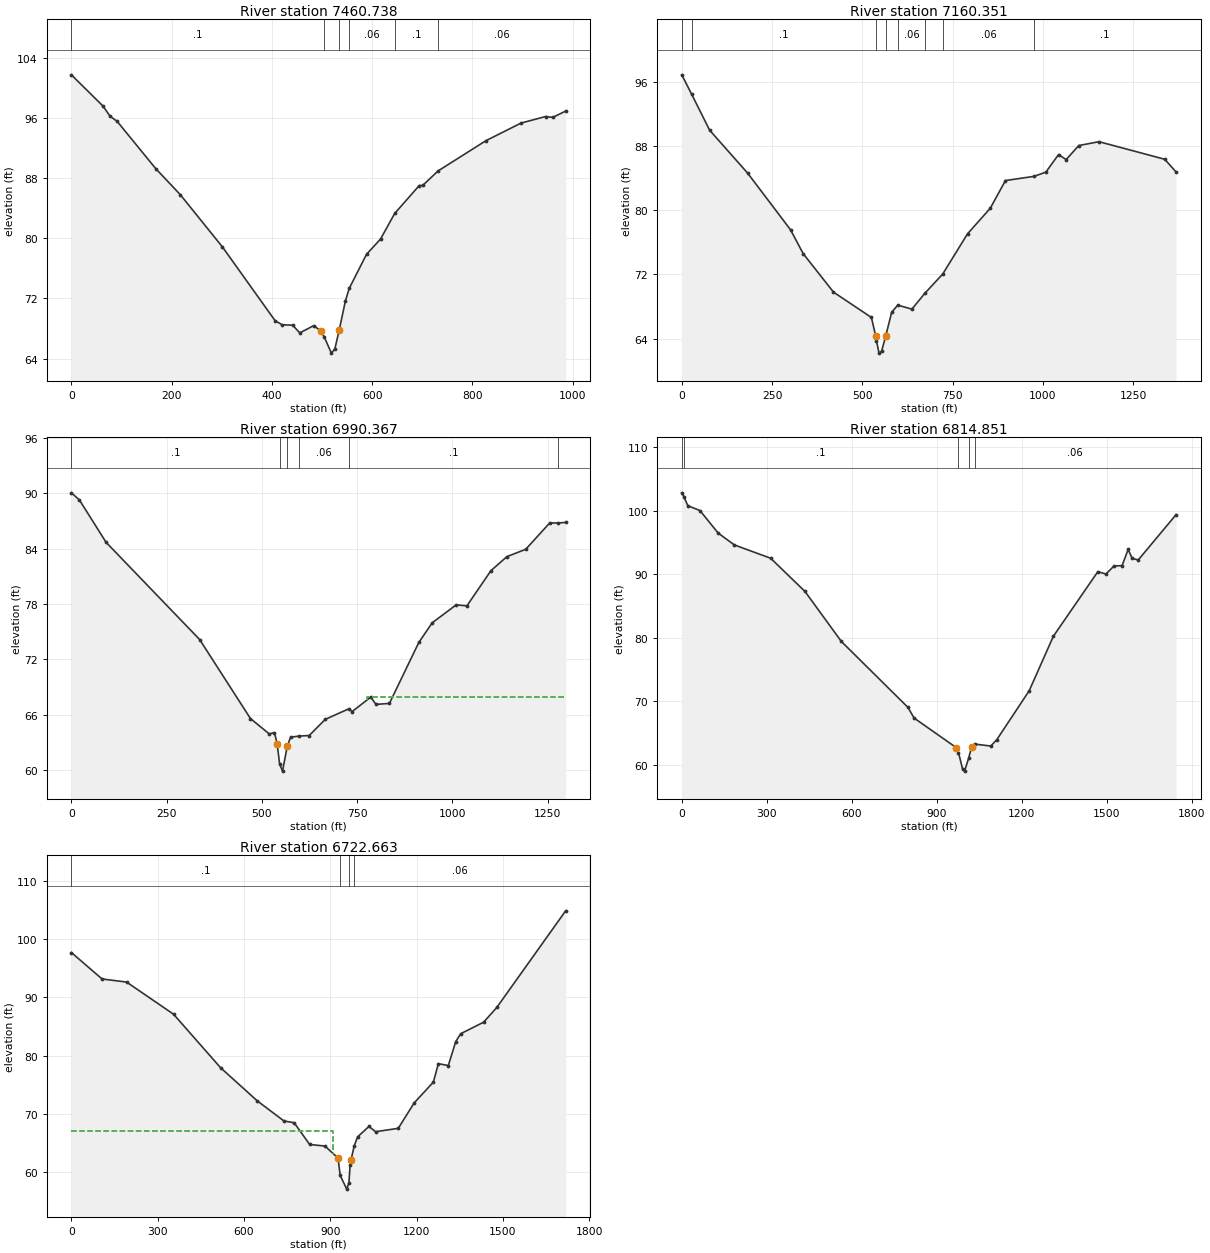
Type RM Length L Ch R = 1 ,7460.738,297.56,300.39,306.5
XS GIS Cut Line= 2
1638025.05074413716557.9399286961637040.29064542716608.824189112
#Sta/Elev= 30
       0  101.72   63.08   97.57    77.1   96.22   91.12   95.55  168.22   89.26
  217.29   85.79   301.4   78.84  406.54   69.03  420.56    68.5  441.59   68.44
  455.61   67.42  483.64   68.39  497.66   67.66  504.67   66.85  518.69   64.73
   525.7    65.3  534.25   67.78  546.73   71.67  554.27   73.33  588.78   77.86
  616.82    79.9  644.99   83.29  693.92      87  700.93   87.02  731.67   88.95
   827.1   92.97   897.2   95.31  946.26   96.18  960.28   96.06  986.07    96.9
#Mann= 6 ,-1 , 0
       0      .1       0  504.67    .045       0  534.25      .1       0
  554.27     .06       0  644.99      .1       0  731.67     .06       0
Bank Sta=497.66,534.25
XS Rating Curve= 0 ,0
Exp/Cntr=0.3,0.1

Type RM Length L Ch R = 1 ,7160.351,169.77,169.98,177.16
XS GIS Cut Line= 2
 1638060.5329656716286.3046814651636692.25231023716296.911508247
#Sta/Elev= 30
       0   96.85   27.37   94.43      77   89.96  182.01   84.62  301.01   77.55
  336.01   74.58  420.01   69.78  525.02   66.62  536.75   64.32  539.02   63.71
  546.02   62.18  553.02    62.4   564.5    64.3  565.66   64.51  581.02   67.26
  597.82   68.16  637.02   67.66  673.08   69.64  722.47   72.04  791.02   77.04
  854.02   80.23  896.03   83.68  975.07    84.2 1008.03   84.73 1043.03   86.92
 1064.03   86.29 1099.03   88.04 1155.03   88.52 1337.04   86.33 1368.32   84.75
#Mann= 8 ,-1 , 0
       0     .06       0   27.37      .1       0  539.02     .04       0
  565.66      .1       0  597.82     .06       0  673.08      .1       0
  722.47     .06       0  975.07      .1       0
Bank Sta=536.75,564.5
XS Rating Curve= 0 ,0
Exp/Cntr=0.3,0.1

Type RM Length L Ch R = 1 ,6990.367,151.51,175.52,175.32
XS GIS Cut Line= 2
1638065.73137043716155.8630548121636771.11733893716076.347413719
#Sta/Elev= 30
       0   90.06   21.04   89.29   91.17   84.69  336.63   74.16  469.88    65.6
  518.98   63.94     533   64.07  540.02   62.87  546.32   60.71  554.04    59.9
  566.42   62.58  575.08   63.58   598.2    63.7  624.17   63.76  666.25   65.51
  728.94   66.67  736.38   66.34  785.48   67.92   799.5   67.13  834.57   67.24
  911.71   73.84  946.78   75.97  1009.9   77.92 1037.95   77.81 1101.07   81.63
 1143.15   83.15 1192.24   83.94 1255.36    86.8 1276.43   86.79 1297.05   86.85
#Mann= 6 ,-1 , 0
       0      .1       0  546.32    .045       0  566.42      .1       0
   598.2     .06       0  728.94      .1       0 1276.43     .06       0
#XS Ineff= 2 , 0
                          776.81           67.91
Permanent Ineff=
       F       F
Bank Sta=540.02,566.42
XS Rating Curve= 0 ,0
Exp/Cntr=0.3,0.1

Type RM Length L Ch R = 1 ,6814.851,91.23,92.19,98.86
XS GIS Cut Line= 2
1638460.22092181716151.4314656851636747.20261894715819.213778883
#Sta/Elev= 30
       0   102.8    6.98  102.22   21.39  100.77   64.17  100.01  128.35   96.47
  185.39    94.6  313.74    92.5  434.96   87.27   563.3    79.4  798.61   69.01
     820   67.34  969.74   62.66  976.87   61.91  991.13   59.35  998.26   58.98
 1012.52   60.99 1023.17   62.76 1033.52   63.24 1090.96   62.93 1112.35   63.95
 1226.43   71.63    1312   80.23 1468.87   90.39 1497.39   90.01 1525.91   91.28
 1554.43   91.34 1575.82   93.89 1590.08   92.48 1611.47   92.23 1744.93   99.36
#Mann= 5 ,-1 , 0
       0      .1       0    6.98      .1       0  976.87    .045       0
 1012.52      .1       0 1033.52     .06       0
Bank Sta=969.74,1023.17
XS Rating Curve= 0 ,0
Exp/Cntr=0.5,0.3

Type RM Length L Ch R = 1 ,6722.663,104.19,80.87,79.11
BEGIN DESCRIPTION:
Lowered channel in proximity of bridge as per bridge inspection notes.
END DESCRIPTION:
XS GIS Cut Line= 6
1638412.15708898716066.5262705241637611.23231274715925.938410848
1637422.06778626715846.8285286281637224.03994389715744.157823443
1637098.07305515715652.940421224 1636851.3951568715446.666661397
#Sta/Elev= 30
       0   97.67  106.61   93.13  191.89    92.6  355.35   87.08  518.81    77.9
  646.74    72.2  739.13   68.77  774.66   68.47  828.34   64.74  881.46   64.47
  926.98   62.41  934.57   59.42  957.33   57.08  964.92    58.2  968.98   61.15
  972.51   62.14  983.41   64.53  995.27   66.05 1034.38   67.83 1057.63   66.93
 1136.48   67.51 1191.68   71.87 1258.56   75.44 1275.84    78.6 1310.41   78.28
 1336.34    82.4 1353.62   83.74  1433.3   85.72 1478.92   88.24 1718.35  104.82
#Mann= 4 ,-1 , 0
       0      .1       0  934.57     .04       0  964.92      .1       0
  983.41     .06       0
#XS Ineff= 2 ,-1
       0   910.1   67.05 1033.72 1718.35   67.05
Permanent Ineff=
       F       F
Bank Sta=926.98,972.51
XS Rating Curve= 0 ,0
Exp/Cntr=0.5,0.3