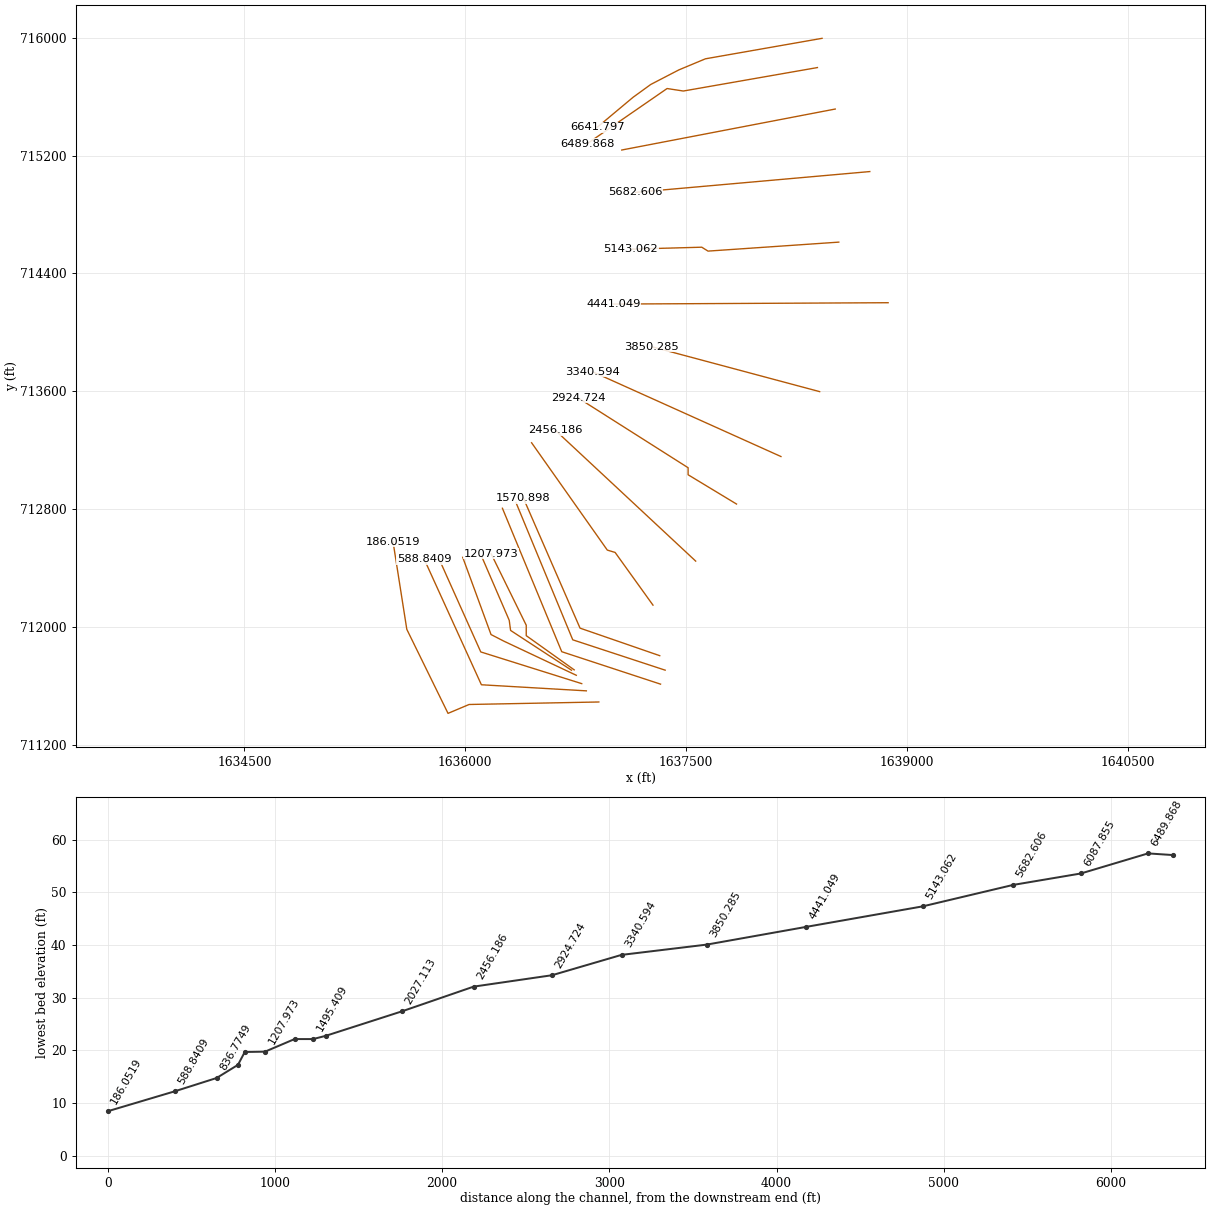
HEC-RAS study Dogwood.prj: Dogwood Run

--- Dogwood.g13 (geometry) --- (continued)

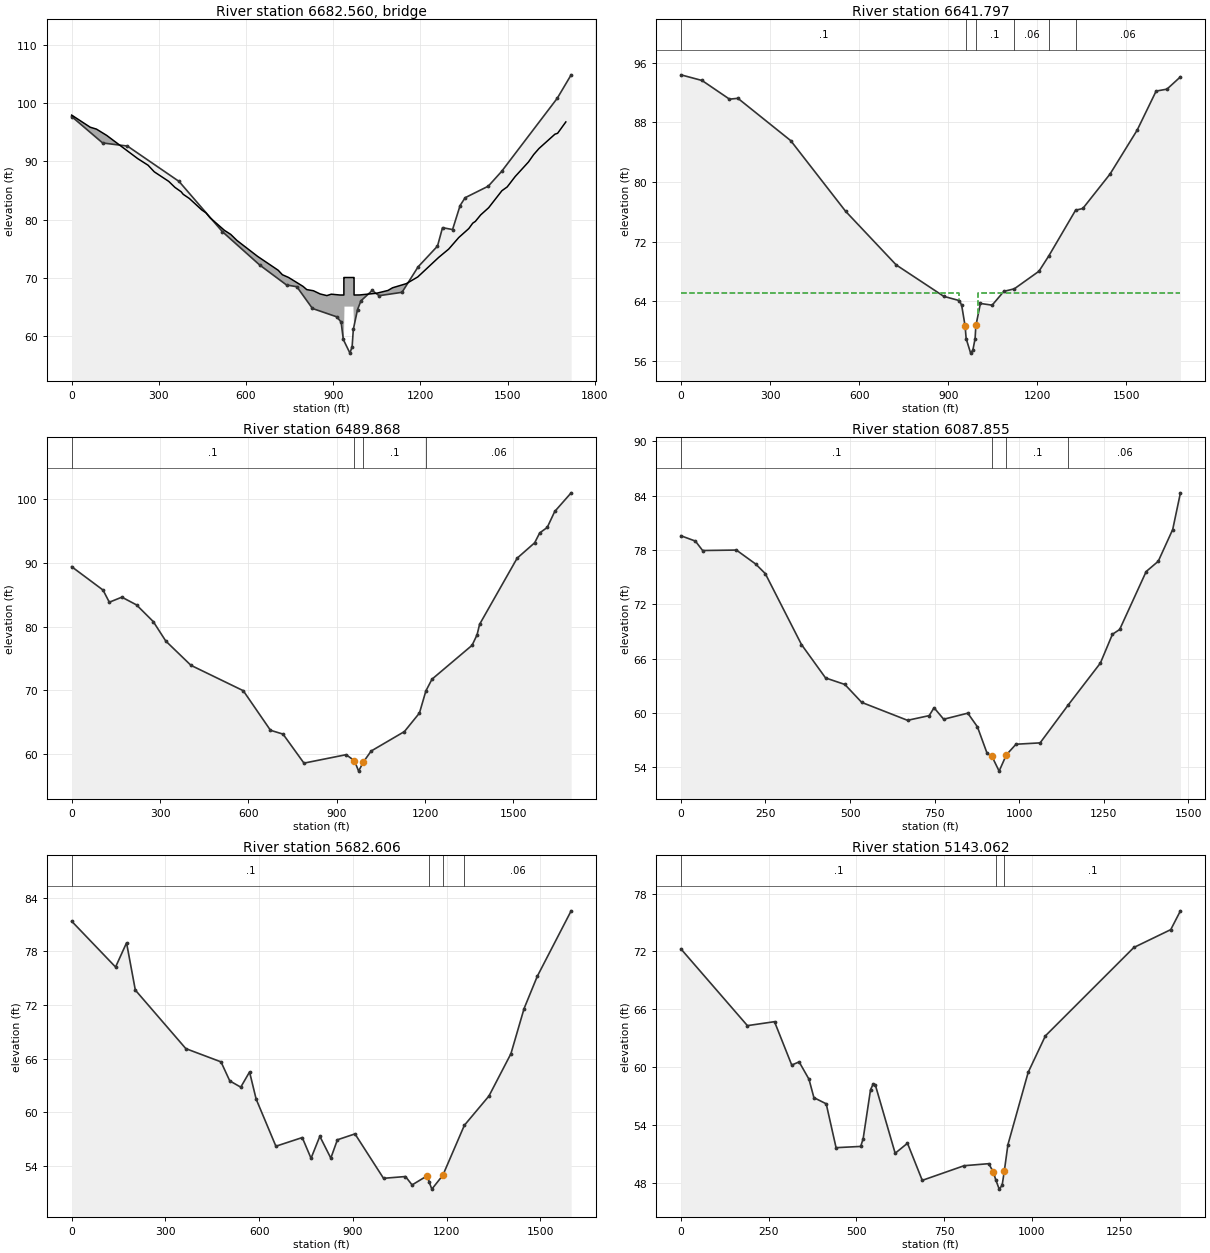
Type RM Length L Ch R = 3 ,6682.560,,,
BEGIN DESCRIPTION:
CE050807PF-4  Dogwood Rd.
Opening is 31'.  Overall ht including rail is 14'.
Underclearance = 8'
END DESCRIPTION:
Bridge Culvert--1,0,-1,-1, 0
Deck Dist Width WeirC Skew NumUp NumDn MinLoCord MaxHiCord MaxSubmerge Is_Ogee
35,31,2.6,0, 60, 60, , , 0.95, 0, 2,2,,
       0   63.96   85.28  120.82  227.42  262.96  284.28  334.03  355.35  376.67
  383.78   405.1  447.74  461.96  476.17  525.92  547.24  568.56  639.63   710.7
  724.92  746.24  795.99  808.72  831.79  854.86  877.92  893.04  923.15 936.499
   936.5  938.49   938.5   969.5  969.51   971.5  971.51  990.89 1048.77 1088.19
 1103.96 1151.27  1190.7 1262.59 1297.16 1331.73  1366.3 1379.72 1388.85  1407.1
 1434.47  1480.1 1498.35 1525.72 1571.35  1589.6 1607.85 1662.59 1671.72 1700.06
   97.91   95.83   95.51   94.42   90.44   89.31   88.18   86.54   85.51   84.76
   84.32    83.6   81.64   81.15    80.3   78.13   77.45   76.41   73.68   71.29
   70.53   70.06   68.53   67.98   67.78   67.23   66.95   67.19   67.05   67.05
   70.05   70.05   70.05   70.05   70.05   70.05   67.05   67.06   67.35   67.83
   68.29      69   70.15    73.5   74.93   76.91   78.45   79.37   79.68   80.79
   82.02   84.94   85.59   87.37   89.86   91.15   92.19   94.64   94.79   96.74
                                                                                
                                                                                
                                                                               1
       1           65.06   65.06               1       1
                                                                                
                                                                                
       0   63.96   85.28  120.82  227.42  262.96  284.28  334.03  355.35  376.67
  383.78   405.1  447.74  461.96  476.17  525.92  547.24  568.56  639.63   710.7
  724.92  746.24  795.99  808.72  831.79  854.86  877.92  893.04  957.49  959.49
   959.5   990.5  990.51   992.5  992.51 1048.77 1088.19 1103.96 1111.85 1151.27
  1190.7 1206.47 1222.24 1262.59 1297.16 1331.73  1366.3 1379.72 1388.85  1407.1
 1434.47  1480.1 1498.35 1525.72 1571.35  1589.6 1607.85 1662.59 1671.72 1700.06
   97.91   95.83   95.51   94.42   90.44   89.31   88.18   86.54   85.51   84.76
   84.32    83.6   81.64   81.15    80.3   78.13   77.45   76.41   73.68   71.29
   70.53   70.06   68.53   67.98   67.78   67.23   66.95   67.19   67.06   70.06
   70.06   70.06   70.06   70.06   67.06   67.35   67.83   68.29   68.29      69
   70.15   70.95   71.48    73.5   74.93   76.91   78.45   79.37   79.68   80.79
   82.02   84.94   85.59   87.37   89.86   91.15   92.19   94.64   94.79   96.74
                                                                                
                                                                                
                                                                               1
   65.06   65.06
                                                                                
                                                                                
BR Coef=-1 , 0 , 0 ,, 0 ,,,0.8,0,,0,
WSPro=,,,, 1 ,,,, 0 ,,,, 0 ,,,,-1 ,-1 ,-1 , 0 , 0 , 0 , 0 , 0
BR U #Sta/Elev= 30
       0   97.67  106.61   93.13  191.89    92.6  369.57   86.53  518.81    77.9
  646.74    72.2  739.13   68.77  774.66   68.47  828.34   64.74  911.81   63.31
  926.98   62.41  934.57   59.42  957.33   57.08  964.92    58.2  968.98   61.15
  983.41   64.53  995.27   66.05 1033.98   67.83 1057.63   66.93 1136.48   67.51
 1191.68   71.87 1258.56   75.44 1275.84    78.6 1310.41   78.28 1336.34    82.4
 1353.62   83.74  1433.3   85.72 1478.92   88.24 1670.54   100.8 1718.35  104.82
BR U #Mann= 4
       0      .1  934.57    .038  964.92      .1  983.41     .06
BR D #Sta/Elev= 30
       0   94.37   42.64   93.43   71.07   93.61  163.46   91.11  191.89   91.22
  291.39   87.51  369.57   85.55  554.35   76.08  724.92   68.88  885.02   64.67
  937.71    64.1  952.76   62.06  960.29      59  975.34   57.06  982.87   57.46
   990.4   59.01  992.88    60.7 1008.31   63.72 1047.73   63.49 1087.15   65.34
 1122.37   65.68 1205.43   68.04 1238.91   70.12 1328.72   76.22 1352.99   76.45
 1444.71   81.07 1535.96   86.95 1599.84   92.19 1636.34   92.45 1681.71    94.1
BR D #Mann= 6
       0      .1  960.29    .038  992.88      .1 1122.37     .06 1238.91      .1
 1328.72     .06
BC Design=,, 0 ,, 0 ,,,,,,
BC Use User HTab Curves=0
BC User HTab FreeFlow(D)= 0

Type RM Length L Ch R = 1 ,6641.797,156.47,151.93,144.01
BEGIN DESCRIPTION:
Lowered channel in proximity of bridge as per bridge inspection
END DESCRIPTION:
XS GIS Cut Line= 6
1638424.25929421715997.5803741371637632.09829327715858.530836746
1637451.11929616715783.0418155191637260.88014588715684.409282461
1637141.10507974715597.6756138211636896.29906811715392.967138603
#Sta/Elev= 30
       0   94.37   71.07   93.61  163.46   91.11  191.89   91.22  369.57   85.55
  554.35   76.08  724.92   68.88  885.02   64.67  937.71    64.1  945.24   63.46
   956.7   60.71  960.29      59  975.34   57.06  982.87   57.46   990.4   59.01
  992.88    60.7  993.22   60.78 1008.31   63.72 1047.73   63.49 1087.15   65.34
 1122.37   65.68 1205.43   68.04 1238.91   70.12 1328.72   76.22 1352.99   76.45
 1444.71   81.07 1535.96   86.95 1599.84   92.19 1636.34   92.45 1681.71    94.1
#Mann= 6 ,-1 , 0
       0      .1       0  960.29     .04       0  992.88      .1       0
 1122.37     .06       0 1238.91      .1       0 1328.72     .06       0
#XS Ineff= 2 ,-1
       0  935.26   65.06 1000.98 1681.71   65.06
Permanent Ineff=
       F       F
Bank Sta=956.7,993.22
XS Rating Curve= 0 ,0
Exp/Cntr=0.5,0.3

Type RM Length L Ch R = 1 ,6489.868,314.54,402.01,361.46
XS GIS Cut Line= 4
1638392.78661005715799.0221581161637481.83674037715639.617775381
1637371.55644242715656.5839750621636828.63805272715281.913732141
#Sta/Elev= 30
       0   89.36   106.6    85.7  127.91    83.8  170.55   84.59   220.3   83.38
  277.15   80.77  319.79   77.72  405.06   73.93  582.72   69.96   675.1   63.77
  717.74   63.17  788.81   58.63  931.87   59.95   960.2   59.01  974.37   57.38
   990.3   58.79 1016.86   60.52 1129.93   63.57 1180.96   66.47 1202.81   69.93
 1223.48   71.76 1359.56   77.06 1376.57    78.7 1385.08   80.34 1512.65   90.69
 1572.19    93.1  1589.2   94.64 1614.71   95.49 1640.23   97.99 1696.02  100.91
#Mann= 4 ,-1 , 0
       0      .1       0   960.2     .04       0   990.3      .1       0
 1202.81     .06       0
Bank Sta=960.2,990.3
XS Rating Curve= 0 ,0
Exp/Cntr=0.3,0.1

Type RM Length L Ch R = 1 ,6087.855,355.75,405.25,354.83
XS GIS Cut Line= 2
 1638513.9748107715517.3097394851637063.49124777715238.880536363
#Sta/Elev= 30
       0   79.56   42.77   78.97   64.15   77.93  163.94   77.98  220.96   76.44
  249.47   75.38  356.39   67.55  427.67   63.86  484.69   63.14  534.59   61.16
  670.01   59.18  734.16    59.7  748.42   60.57  776.93    59.3  848.21   59.97
  876.72   58.46  905.23   55.54  919.49   55.21  940.87   53.57  962.25   55.37
  990.76   56.54 1062.04   56.69 1145.83   60.91 1240.24    65.5 1275.88   68.68
 1297.26   69.21 1375.67   75.61 1411.31   76.74 1454.07   80.25 1476.97    84.3
#Mann= 4 ,-1 , 0
       0      .1       0  919.49     .04       0  962.25      .1       0
 1145.83     .06       0
Bank Sta=919.49,962.25
XS Rating Curve= 0 ,0
Exp/Cntr=0.3,0.1

Type RM Length L Ch R = 1 ,5682.606,471.47,539.54,455.15
XS GIS Cut Line= 2
1638748.64631639715092.457835734 1637156.6512465714951.072838396
#Sta/Elev= 30
       0   81.38  140.55   76.25  175.69   78.96   203.8   73.67  365.43   67.12
  477.87   65.64  505.98   63.51  541.12   62.81  569.23   64.51  590.31   61.48
  653.56    56.2  737.89   57.17     766   54.85  794.11   57.31  829.25   54.87
  850.33   56.92  906.55   57.58  997.91   52.61 1068.19   52.81 1089.27   51.87
 1138.46   52.91 1143.88   52.19 1152.52    51.4 1187.66   52.95 1256.55   58.54
 1335.23   61.82 1405.51   66.55 1447.68   71.61 1489.84   75.21 1598.26   82.54
#Mann= 4 ,-1 , 0
       0      .1       0 1143.88     .04       0 1187.66      .1       0
 1256.55     .06       0
Bank Sta=1138.46,1187.66
XS Rating Curve= 0 ,0
Exp/Cntr=0.3,0.1

Type RM Length L Ch R = 1 ,5143.062,369,702.01,508.97
XS GIS Cut Line= 4
1638537.84017096714613.0777559731637649.51842767714552.088501975
1637607.09112054714578.6055689161637124.48050177714565.347035438
#Sta/Elev= 30
       0   72.26  189.44    64.3  266.63   64.71  315.74   60.21  336.79   60.54
  364.86   58.74  378.89   56.83  413.97   56.19  442.04   51.64   512.2   51.77
  519.22   52.57  540.27   57.66  547.29    58.2   554.3    58.1  610.43   51.06
  645.52    52.1  687.61   48.25   806.9   49.77  877.06   49.98  890.41   49.09
  896.78   48.33  906.92   47.34  915.18   47.73  921.26   49.18  931.69   51.95
  989.46   59.46 1038.48   63.24 1290.58   72.41 1395.62   74.26 1423.24   76.21
#Mann= 3 ,-1 , 0
       0      .1       0  896.78     .04       0  921.26      .1       0
Bank Sta=890.41,921.26
XS Rating Curve= 0 ,0
Exp/Cntr=0.3,0.1

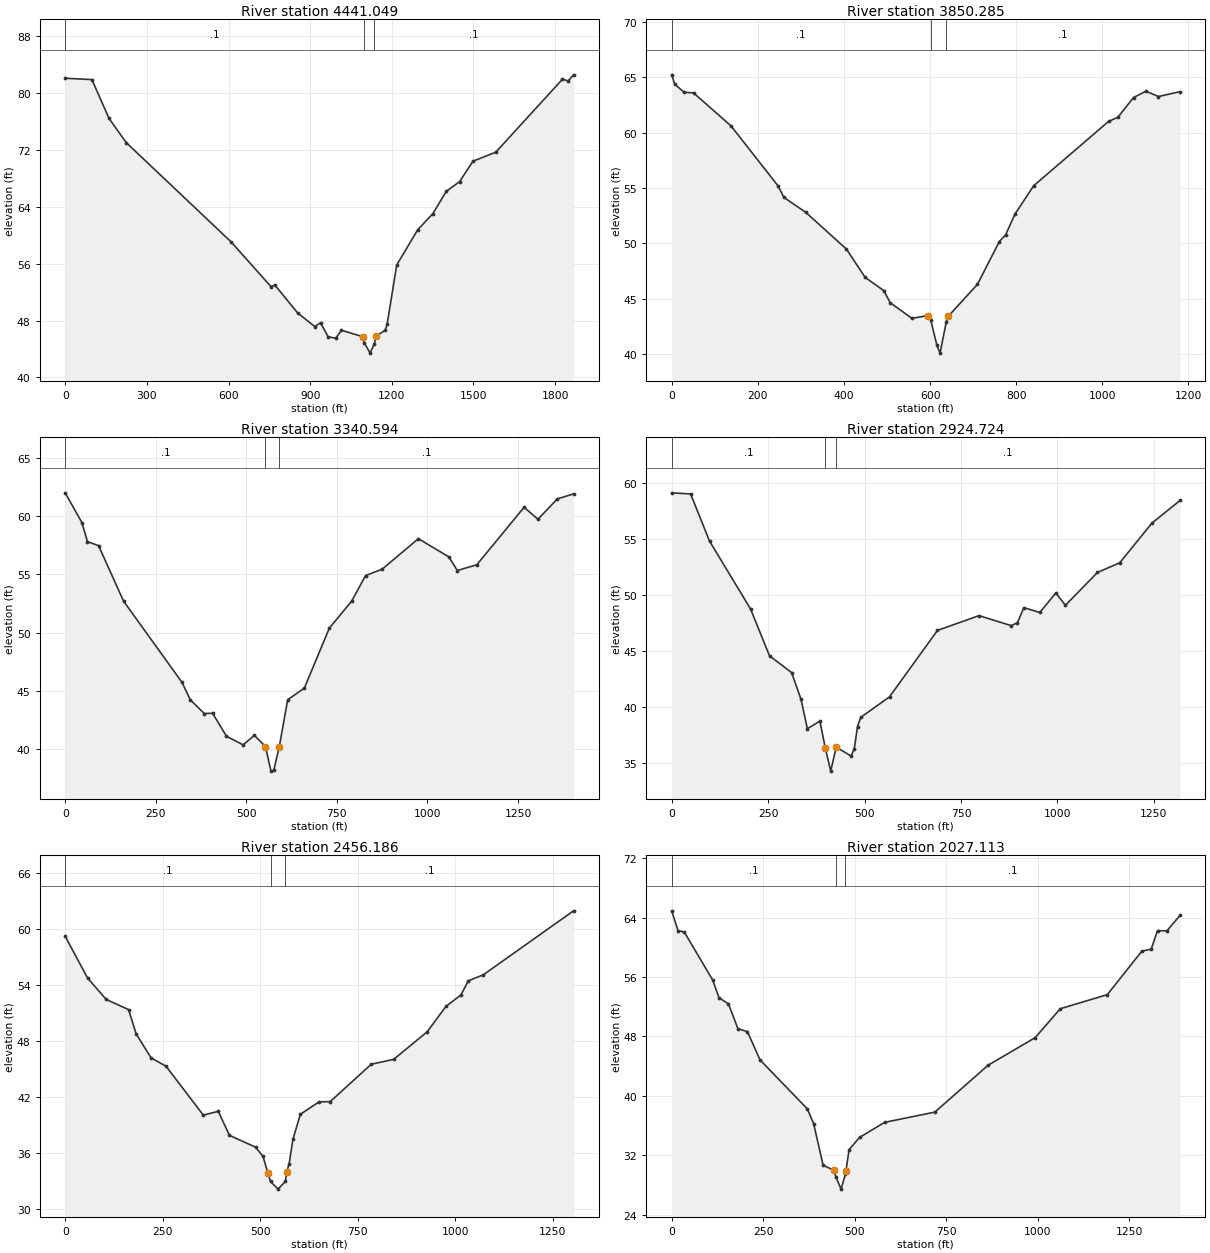
Type RM Length L Ch R = 1 ,4441.049,470.23,590.76,442.49
XS GIS Cut Line= 2
1638873.20348592714201.4677069491637005.66362789714192.328033909
#Sta/Elev= 30
       0   82.02      98   81.83     161   76.38     224   72.99  609.01   59.06
  756.01   52.76  770.01   52.99  854.01   49.06  917.01   47.15  938.01   47.69
  966.01   45.71  994.01   45.52 1015.01   46.64 1093.31   45.72 1099.01   44.87
 1120.01   43.42 1135.48   44.71 1142.94   45.81 1176.01   46.65 1183.01   47.54
 1218.01    55.8 1295.02   60.74 1351.02   63.02 1400.02   66.14 1449.02    67.5
 1498.02   70.37 1582.02   71.64 1827.02   81.89 1848.03   81.64 1867.57    82.5
#Mann= 3 ,-1 , 0
       0      .1       0 1099.01    .045       0 1135.48      .1       0
Bank Sta=1093.31,1142.94
XS Rating Curve= 0 ,0
Exp/Cntr=0.3,0.1

Type RM Length L Ch R = 1 ,3850.285,425.59,509.69,443.35
XS GIS Cut Line= 2
1638407.90654287713597.4740912321637267.67266338 713902.42036134
#Sta/Elev= 30
       0   65.22    7.25   64.37   28.98   63.64   50.72   63.59  137.67   60.61
  246.36   55.22  260.86   54.14  311.58   52.79  405.78   49.48  449.25   46.92
  492.73   45.72  507.22   44.64  557.94   43.22  594.17   43.47  601.42   43.09
  615.91   40.78  623.16   40.08  637.65   42.91  642.06    43.4  710.11    46.3
  760.83   50.16  775.32   50.76  797.06   52.63  840.54    55.2 1014.44   61.01
 1036.18   61.39 1072.41   63.17 1101.39   63.74 1130.38   63.26 1180.31    63.7
#Mann= 3 ,-1 , 0
       0      .1       0  601.42    .045       0  637.65      .1       0
Bank Sta=594.17,642.06
XS Rating Curve= 0 ,0
Exp/Cntr=0.3,0.1

Type RM Length L Ch R = 1 ,3340.594,382.6,415.87,365.21
XS GIS Cut Line= 2
1638145.07620032713156.4984226231636865.52197458713732.297824174
#Sta/Elev= 30
       0   61.99   46.06   59.44   61.41   57.81   92.11   57.46   161.2    52.7
   322.4   45.74  345.42   44.24   383.8   43.07  406.83   43.09  445.21   41.12
  491.27   40.38  521.97    41.2  552.68   40.24  568.03   38.13  575.71   38.21
  591.06   40.24  614.09   44.25  660.14   45.25  729.23    50.4  790.64    52.7
  829.02   54.89  875.07   55.45  974.86   58.06  1059.3   56.49 1082.33   55.33
 1136.06   55.82 1266.56   60.75 1304.94   59.73 1358.67   61.47 1403.14    61.9
#Mann= 3 , 0 , 0
       0      .1       0  552.68    .045       0  591.06      .1       0
Bank Sta=552.68,591.06
XS Rating Curve= 0 ,0
Exp/Cntr=0.3,0.1

Type RM Length L Ch R = 1 ,2924.724,415.91,468.54,448.08
XS GIS Cut Line= 4
1637843.09301654712833.7825626581637514.28138617713032.660564885
1637514.28138617713080.3912854191636766.50009774713555.046784073
#Sta/Elev= 30
       0   59.11   49.08   59.01   98.17    54.8  204.52   48.74  253.61   44.56
  310.87   43.07  335.41   40.67  351.77   38.06  384.28   38.74  398.28   36.33
  412.28   34.27  426.28   36.38  427.07    36.4  465.17   35.62  473.46   36.28
  481.76   38.25  490.05   39.07  564.67    40.9  689.03   46.83  796.82   48.15
  879.73   47.26  896.31   47.51  912.89   48.86  954.35   48.43  995.81   50.17
 1020.68   49.07 1103.59      52 1161.63   52.87 1244.54   56.39 1317.72   58.43
#Mann= 3 ,-1 , 0
       0      .1       0  398.28    .045       0  426.28      .1       0
Bank Sta=398.28,427.07
XS Rating Curve= 0 ,0
Exp/Cntr=0.3,0.1

Type RM Length L Ch R = 1 ,2456.186,386.75,429.07,375.66
XS GIS Cut Line= 2
 1637565.6594902712446.1457152661636612.40393892713334.773771495
#Sta/Elev= 30
       0   59.17   57.42    54.7  105.27   52.41  162.69   51.32  181.83   48.73
  220.11   46.16  258.38   45.27  354.08   40.03  392.36   40.44  421.07   37.87
  488.06    36.6   507.2   35.61  519.25   33.87  526.34   32.93  545.48   32.11
  564.62   32.94   567.7   33.92  574.19   34.84  583.76   37.43   602.9   40.12
  650.75   41.45  679.46   41.48  784.72   45.48  842.14      46  928.27   48.96
  976.12   51.67  1014.4   52.89 1033.54   54.41 1071.82   55.05 1303.21    61.9
#Mann= 3 ,-1 , 0
       0      .1       0  526.34    .045       0  564.62      .1       0
Bank Sta=519.25,567.7
XS Rating Curve= 0 ,0
Exp/Cntr=0.3,0.1

Type RM Length L Ch R = 1 ,2027.113,464.27,456.21,441.32
XS GIS Cut Line= 4
1637275.62778349712146.9905282711637018.41223387712504.970932275
1636965.37809999712520.8811724631636450.94700083 713250.10051398
#Sta/Elev= 30
       0   64.92   17.24   62.26   34.48   62.06  112.05   55.59  129.29   53.21
  155.15   52.38  181.01   49.04  206.87   48.64  241.35   44.83  370.64   38.23
  387.88   36.23  413.74   30.63  443.48   29.96  448.11   29.12  462.73   27.42
  474.48   29.41  476.01   29.88  484.65   32.74  513.31   34.39  581.84   36.42
   718.9    37.8  864.54   44.12  993.03   47.83 1061.57   51.73 1190.06   53.63
  1284.3   59.48    1310   59.76 1327.13   62.25 1352.83   62.22 1388.59    64.3
#Mann= 3 ,-1 , 0
       0      .1       0  448.11    .045       0  474.48      .1       0
Bank Sta=443.48,476.01
XS Rating Curve= 0 ,0
Exp/Cntr=0.3,0.1

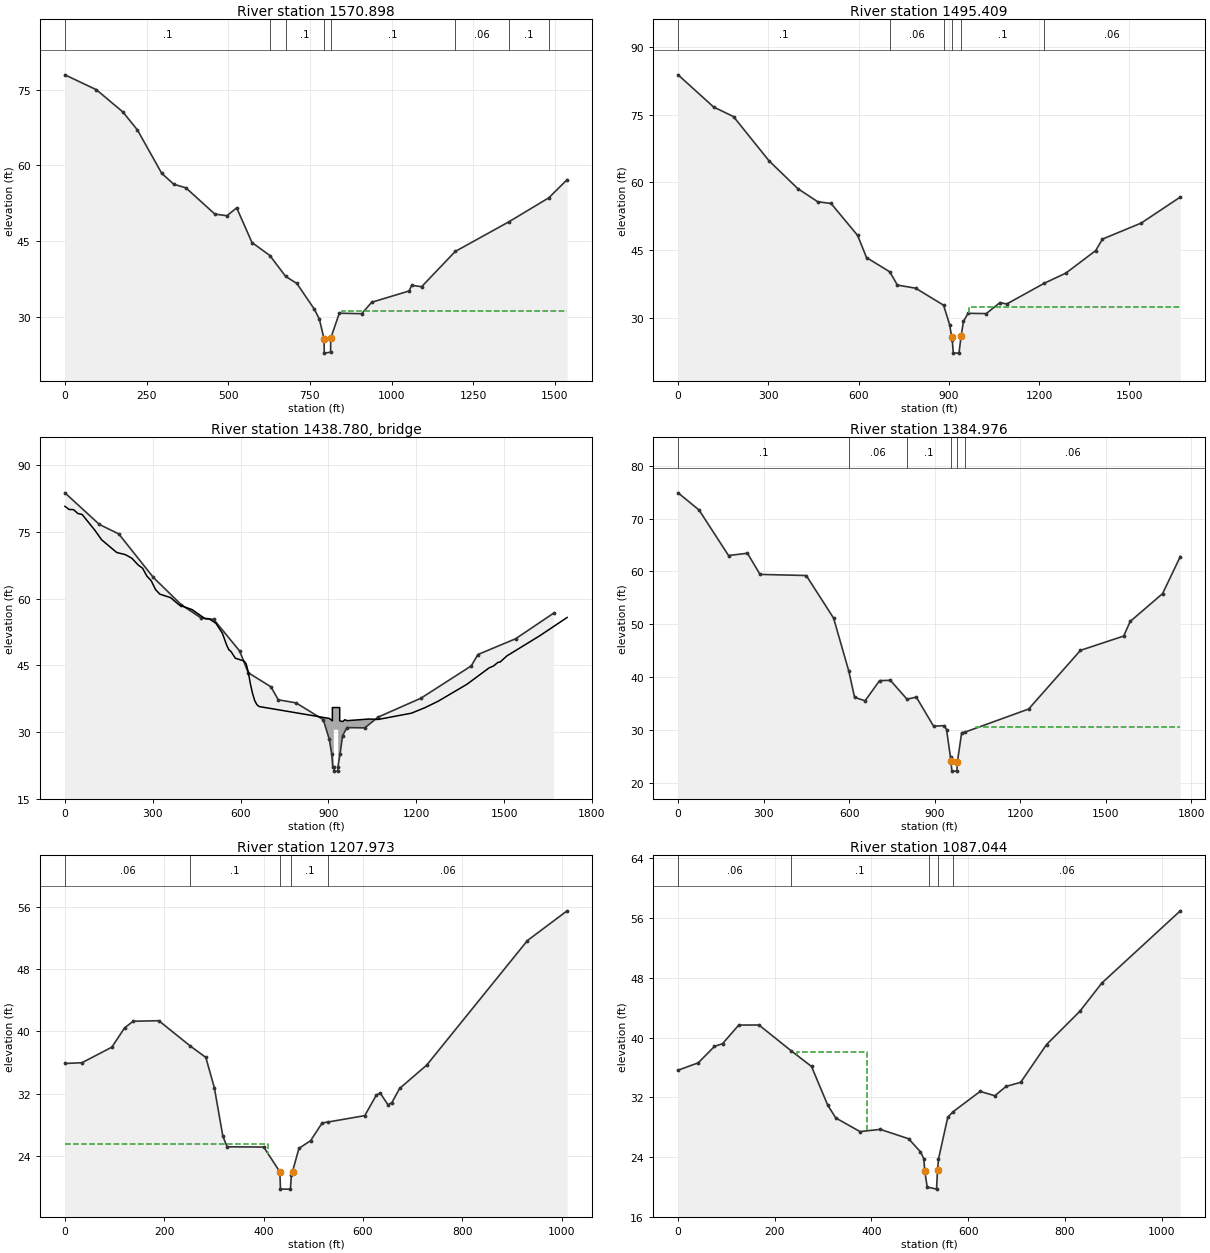
Type RM Length L Ch R = 1 ,1570.898,75.92,75.49,74.68
BEGIN DESCRIPTION:
underwater portion from hec2 section 301.4.  Ineffective flow limits are included on this section because a portion of the flow on the right bank is a backwater area, and thus ineffective.
END DESCRIPTION:
XS GIS Cut Line= 3
1637321.52124289711803.5707412811636780.20024237711990.624071285
1636394.75701691712874.876176789
#Sta/Elev= 30
       0   77.96   96.28   75.01  177.75   70.58  222.18   67.01  296.25   58.44
  333.28   56.26  370.31   55.55  459.18   50.34  496.21   50.02  525.84   51.59
  572.73    44.7  627.39   42.13  675.66   37.99  710.18   36.58  763.63   31.48
   778.9   29.52  793.37   25.58     794   22.77  813.33   22.96  813.81   25.73
  839.99   30.69  908.72   30.59  939.26   32.86  1053.8    35.1 1061.44   36.22
 1091.98   35.94 1194.82   42.93 1359.31   48.82 1481.53   53.58 1537.33   57.17
#Mann= 8 ,-1 , 0
       0      .1       0  627.39     .06       0  675.66      .1       0
  793.37    .045       0  813.33      .1       0 1194.82     .06       0
 1359.31      .1       0 1481.53     .06       0
#XS Ineff= 1 ,-1
  848.34 1537.33  31.088
Permanent Ineff=
       F
Bank Sta=793.37,813.81
XS Rating Curve= 0 ,0
Exp/Cntr=0.5,0.3

Type RM Length L Ch R = 1 ,1495.409,110.12,110.43,117.44
BEGIN DESCRIPTION:
underwater portion from hec2 section 301.3
END DESCRIPTION:
XS GIS Cut Line= 3
1637358.29315466711705.1948666271636730.61339277 711911.29866904
1636345.16524518712843.324927628
#Sta/Elev= 30
       0   83.82  117.88    76.7  184.19   74.56  302.08   64.78  397.86   58.61
  464.17    55.7  508.37   55.32  596.78   48.23  626.26   43.33  703.58   40.17
  728.83   37.24  789.43   36.55  882.36   32.78  903.05   28.34  908.78   25.79
  911.42   24.98  914.67   22.19  933.58   22.16  940.73   25.97   948.5   29.19
  963.65   30.98 1024.25   30.92  1069.7   33.35 1092.43   33.05  1216.2   37.61
 1289.38   39.91 1387.85   44.87 1410.58   47.43 1539.35   50.98 1669.23   56.74
#Mann= 6 ,-1 , 0
       0      .1       0  703.58     .06       0  882.36      .1       0
  911.42    .045       0  940.73      .1       0  1216.2     .06       0
#XS Ineff= 2 ,-1
  965.42 1669.23   32.35       0  859.37   32.35
Permanent Ineff=
       F       F
Bank Sta=908.78,940.73
XS Rating Curve= 0 ,0
Exp/Cntr=0.5,0.3

Type RM Length L Ch R = 3 ,1438.780,,,
BEGIN DESCRIPTION:
Blue Ball Road  CE050807FS-9.   Top of road from LIDAR.  Bridge railing was measured to be 3'.  Deck to low chord was 2'.  Width of opening measured 15'.  It appears that the channel is 1' lower than what was coded on HEC2 section, and the footing has been exposed.  The flow width narrows to 13 feet at the bottom of the channel.  Internal cross section ground surface was adjusted -1 foot to show narrowed portion - and get down to the elevation that the 2007 bridge inspection notes indicated..
END DESCRIPTION:
Bridge Culvert--1,0,-1,-1, 0
Deck Dist Width WeirC Skew NumUp NumDn MinLoCord MaxHiCord MaxSubmerge Is_Ogee
50,29,2.6,0, 60, 60, , , 0.95, 0, 2,2,,
       0   14.74   29.47   44.21   58.94  103.15  125.25  176.82   206.3   228.4
   250.5  265.24  279.97  294.71  309.44  324.18  361.02  390.49  434.69   478.9
  493.64  515.74  537.84  552.58  559.95  567.31  582.05  611.52  618.89  626.26
  633.62  640.99  648.36  655.73  663.09   903.3  913.49   913.5 918.499   918.5
   933.5  933.51   938.5  938.51  948.75  956.33   963.9 1039.65 1069.95 1183.57
 1229.02 1274.47 1372.95  1448.7 1463.85    1479 1486.57  1509.3 1622.92 1715.18
   80.78   80.07   80.04   79.17   78.94   75.33   73.26    70.4   69.91   69.11
   67.56   66.85   65.09   64.04   62.06   61.02   60.23   58.58   57.53   55.48
   55.42   54.46   52.22   49.53   48.51    48.1    46.6   45.98   45.36   43.49
   40.79   38.63   37.04   36.14   35.73   33.05    32.5    35.5    35.5    35.5
    35.5    35.5    35.5    32.5   32.35   32.76   32.55   32.92   32.82   34.23
   35.45   36.91   40.73   44.42   44.85   45.67   45.75   47.11    51.7   55.77
                                                                                
                                                                                
                                                                                
                                                                            30.5
    30.5
                                                                                
       0   14.74   29.47   44.21   58.94  125.25  176.82   206.3   228.4   250.5
  265.24  279.97  294.71  309.44  324.18  361.02  390.49  434.69   478.9  493.64
  515.74  537.84  552.58  559.95  567.31  582.05  611.52  618.89  626.26  633.62
  640.99  648.36  655.73  663.09  736.65  789.68  804.83  857.85  948.75  955.49
   955.5 960.499   960.5   975.5  975.51   980.5  980.51 1069.95 1130.55 1183.57
 1229.02 1274.47 1372.95  1448.7 1463.85    1479 1486.57  1509.3 1622.92 1715.18
   80.78   80.07   80.04   79.17   78.94   73.26    70.4   69.91   69.11   67.56
   66.85   65.09   64.04   62.06   61.02   60.23   58.58   57.53   55.48   55.42
   54.46   52.22   49.53   48.51    48.1    46.6   45.98   45.36   43.49   40.79
   38.63   37.04   36.14   35.73   34.76   34.44   34.02   33.63   32.35    32.6
    35.5    35.5    35.5    35.5    35.5   35.61   32.61   32.82    33.5   34.23
   35.45   36.91   40.73   44.42   44.85   45.67   45.75   47.11    51.7   55.77
                                                                                
                                                                                
                                                                                
                                                                                
                    30.5    30.5
                                                                                
BR Coef=-1 , 0 , 0 ,, 0 ,,,0.8,0,,0,
WSPro=,,,, 1 ,,,, 0 ,,,, 0 ,,,,-1 ,-1 ,-1 , 0 , 0 , 0 , 0 , 0
BR U #Sta/Elev= 30
       0   83.82  117.88    76.7  184.19   74.56  302.08   64.78  397.86   58.61
  464.17    55.7  508.37   55.32  596.78   48.23  626.26   43.33  703.58   40.17
  728.83   37.24  789.43   36.55  882.36   32.78  903.05   28.34  911.42   24.98
  914.67   22.19   919.5   22.19 919.501   21.19   932.5   21.19  932.51   22.16
   939.7      25   948.5   29.19  963.65   30.98 1024.25   30.92  1069.7   33.35
  1216.2   37.61 1387.85   44.87 1410.58   47.43 1539.35   50.98 1669.23   56.74
BR U #Mann= 8
       0      .1  703.58     .06  882.36      .1  903.05    .035  911.42    .035
   939.7      .1   948.5      .1  1216.2     .06
BR U Banks=911.42,939.7
BR D #Sta/Elev= 30
       0    74.9   73.68   71.63  176.82   63.02  243.13   63.45  287.34   59.44
  449.43   59.23  545.21   51.16  598.61   41.11  618.89   36.14  655.73   35.49
   706.6   39.31  744.47   39.37  802.72   35.79  835.37   36.19  895.97   30.67
  933.85   30.78     955    25.2 961.501   21.16   977.8   22.17  980.54    25.5
  982.36   25.49  994.45   29.44 1007.54   29.58 1229.27   33.93 1411.07   45.05
  1524.7   48.41 1562.57   47.76  1585.3   50.52 1698.92    55.8 1761.13   62.82
BR D #Mann= 8
       0      .1  598.61     .06  802.72      .1     955    .035   977.8    .035
  980.54      .1  982.36      .1 1007.54     .06
BR D Banks=955,980.54
BC Design=,, 0 ,, 0 ,,,,,,
BC Use User HTab Curves=0
BC User HTab FreeFlow(D)= 0

Type RM Length L Ch R = 1 ,1384.976,180.1,177,164.74
BEGIN DESCRIPTION:
underwater portion from hec2 301.2
END DESCRIPTION:
XS GIS Cut Line= 3
1637327.09611024711610.1856859031636655.76322259711830.623350531
1636252.75593121712805.108194396
#Sta/Elev= 30
       0    74.9   73.68   71.63  176.82   63.02  243.13   63.45  287.34   59.44
  449.43   59.23  545.21   51.16  598.61   41.11  618.89   36.14  655.73   35.49
   706.6   39.31  744.47   39.37  802.72   35.79  835.37   36.19  895.97   30.67
  933.85   30.78  941.42   30.01  955.27   24.75  956.77   24.04  960.08   22.16
   977.8   22.17  979.43   23.94  994.45   29.44 1007.54   29.58 1229.27   33.93
 1411.07   45.05 1562.57   47.76  1585.3   50.52 1698.92    55.8 1761.13   62.82
#Mann= 6 ,-1 , 0
       0      .1       0  598.61     .06       0  802.72      .1       0
  955.27    .045       0   977.8      .1       0 1007.54     .06       0
#XS Ineff= 2 ,-1
       0  912.23    30.5 1045.58 1761.13    30.5
Permanent Ineff=
       F       F
Bank Sta=956.77,979.43
XS Rating Curve= 0 ,0
Exp/Cntr=0.5,0.3

Type RM Length L Ch R = 1 ,1207.973,121.86,120.93,116.43
BEGIN DESCRIPTION:
under water portion adjusted with hec2 section 301.1 adjusted -3 ft vertically.  roughly match banks to determine vertical adjustment.  Ineffective area set on the left bank limits flow from small ineffective ponds along the section.
END DESCRIPTION:
XS GIS Cut Line= 4
1636740.52226329711707.2099349051636414.59600648711939.609526724
1636414.59600648712010.4630608411636176.52813193712495.101234034
#Sta/Elev= 30
       0   35.89   34.39   35.99   94.57   37.99  120.36   40.48  137.56   41.31
  189.14   41.38  252.07   38.15  283.71   36.67   300.9   32.78   318.1   26.53
   326.7    25.2   400.3   25.17  432.85   21.98     434   19.77     454   19.77
  455.89   21.53  458.33   22.03  471.15      25  494.55   25.98  517.94   28.26
  530.53   28.39  603.73    29.2  627.13   31.85  634.93   32.08  650.53   30.59
  658.33   30.88  673.92   32.69  728.52   35.69  931.29   51.67  1011.1   55.48
#Mann= 5 ,-1 , 0
       0     .06       0  252.07      .1       0  432.85    .045       0
  455.89      .1       0  530.53     .06       0
#XS Ineff= 1 ,-1
       0  408.91   25.62
Permanent Ineff=
       F
Bank Sta=432.85,458.33
XS Rating Curve= 0 ,0
Exp/Cntr=0.3,0.1

Type RM Length L Ch R = 1 ,1087.044,36.15,40.74,42.33
BEGIN DESCRIPTION:
underwater portion adjusted to hec2 section 300.11
END DESCRIPTION:
XS GIS Cut Line= 4
 1636722.0412792711704.8508016321636308.31145915 711975.07973814
   1636298.99322712044.0347081571636110.76478833712480.128302261
#Sta/Elev= 30
       0   35.63    41.8   36.62   75.25   38.82   91.97   39.18  125.41   41.67
  167.22   41.68   233.4   38.25  275.91   36.13  309.35   30.97  326.07   29.24
  376.24   27.41  418.04   27.71  476.57   26.46  501.23   24.71  508.29   23.77
  510.03    22.2  515.17      20  534.49   19.71  536.65   22.32  538.58   23.74
  557.73   29.32  567.77   30.02  624.74   32.79  655.23   32.21  678.11   33.45
   708.6   34.01  761.97   39.06  830.59   43.49  876.34   47.29 1038.72   56.96
#Mann= 5 ,-1 , 0
       0     .06       0   233.4      .1       0  518.22    .045       0
  538.58      .1       0  567.77     .06       0
#XS Ineff= 1 ,-1
  245.81  390.5838.00217
Permanent Ineff=
       F
Bank Sta=510.03,536.65
XS Rating Curve= 0 ,0
Exp/Cntr=0.3,0.1

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
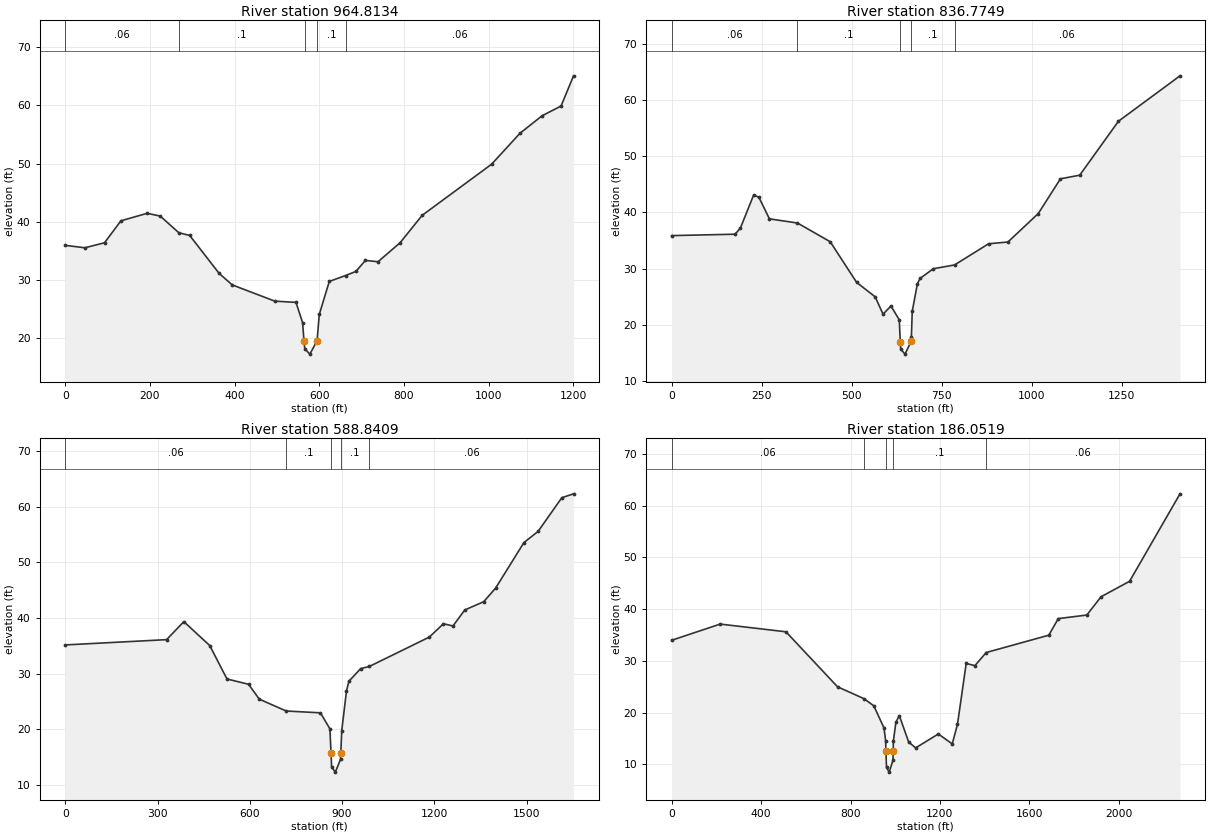
Type RM Length L Ch R = 1 ,964.8134,125.6,128.04,129.2
BEGIN DESCRIPTION:
underwater portion from hec2 section 300.1
END DESCRIPTION:
XS GIS Cut Line= 4
1636754.69297013711670.366097167 1636261.5523728711902.765689015
1636175.38503784711947.0921518061635983.17680596712471.768676609
#Sta/Elev= 30
       0   35.96   46.43   35.54   92.86    36.4  131.55   40.17  193.46   41.46
  224.41   40.99  268.51   38.12  294.06   37.66   363.7   31.13  394.66   29.16
  495.26   26.37  545.16   26.16   560.9   22.65  563.98    19.6     566   18.17
     578   17.27     595   19.57  600.26   24.11  623.88   29.76  662.26   30.77
  686.79   31.48  709.15   33.37  738.97   33.14  791.16   36.41  843.34   41.12
 1007.35    49.9 1074.45   55.22 1126.63   58.22 1171.36   59.89 1200.84   65.08
#Mann= 5 ,-1 , 0
       0     .06       0  268.51      .1       0     566    .045       0
     595      .1       0  662.26     .06       0
Bank Sta=563.98,595
XS Rating Curve= 0 ,0
Exp/Cntr=0.3,0.1

Type RM Length L Ch R = 1 ,836.7749,254.2,247.93,239.18
BEGIN DESCRIPTION:
underwater portion from hec2 section 300.01
END DESCRIPTION:
XS GIS Cut Line= 3
1636791.53680786711613.6832698881636105.67459784711829.078013539
1635822.26046143712461.091537684
#Sta/Elev= 30
       0   35.85  176.09    36.1  190.76   37.18  227.45   43.04  242.12   42.68
  271.47   38.83  349.36   38.09  440.22   34.76   513.6   27.53  564.95   24.97
  586.97   21.88  608.98   23.33     632   20.87  634.83   16.95     636   15.67
     648   14.77     665   17.07  665.69   17.88     668   22.37  682.35   27.28
  689.69   28.23  726.56   29.96  785.52   30.63  879.99    34.4  933.69   34.71
 1018.08   39.78 1079.45   45.95 1133.16    46.6 1240.56   56.19 1411.54   64.27
#Mann= 5 ,-1 , 0
       0     .06       0  349.36      .1       0  634.83    .045       0
  665.69      .1       0  785.52     .06       0
Bank Sta=634.83,665
XS Rating Curve= 0 ,0
Exp/Cntr=0.3,0.1

Type RM Length L Ch R = 1 ,588.8409,334.71,402.79,419.03
BEGIN DESCRIPTION:
underwater portion from hec2 section 300
END DESCRIPTION:
XS GIS Cut Line= 3
1636823.02494514711564.6137579531636109.95101632711605.975354761
1635721.15200639712459.678712696
#Sta/Elev= 30
       0   35.16  329.55   36.11  385.65   39.35  469.79   35.05  525.88   29.03
     596   28.08  631.06   25.39  718.44   23.27  829.65   22.94  860.42   20.06
  864.08   15.67     866   13.17     878   12.27     895   14.57  895.85   15.67
  898.88   19.73  914.26   26.84  921.95   28.61  960.41    30.9  988.43   31.28
 1183.47   36.57 1229.62   38.97 1260.39   38.57 1298.85   41.45 1360.38   42.94
 1398.84   45.37 1491.14   53.58 1537.29    55.6 1614.21   61.65 1652.34   62.35
#Mann= 5 ,-1 , 0
       0     .06       0  718.44      .1       0  864.08    .045       0
     895      .1       0  988.43     .06       0
Bank Sta=864.08,895.85
XS Rating Curve= 0 ,0
Exp/Cntr=0.3,0.1

Type RM Length L Ch R = 1 ,186.0519,243.78,186.05,120.23
BEGIN DESCRIPTION:
underwater portion from hec2 section 1
END DESCRIPTION:
XS GIS Cut Line= 5
1636907.73660375711488.9810498951636026.31863964711471.976201713
1635883.25250702711411.6023007781635603.23012644711982.601743594
1635509.91602819712576.418732375
#Sta/Elev= 30
       0   33.98  217.04   37.11   511.1   35.62  742.14   24.97     860   22.69
  904.37   21.29  949.96      17     957   14.57  958.49   12.54     961    9.37
     973    8.47     990   10.77  990.87   12.59     992   14.57 1003.15   18.14
 1018.34   19.39 1060.25   14.29 1091.44   13.16 1192.79   15.85 1255.16   13.93
 1278.55   17.72 1317.53    29.5 1356.52   29.07 1407.11   31.61    1687   34.96
 1729.51   38.17 1857.06   38.86 1920.83    42.4 2048.38   45.39 2273.93   62.31
#Mann= 5 ,-1 , 0
       0     .06       0     860      .1       0     957    .045       0
     992      .1       0 1407.11     .06       0
Bank Sta=958.49,990.87
XS Rating Curve= 0 ,0
Exp/Cntr=0.3,0.1

Chan Stop Cuts=-1
Use User Specified Reach Order=0
User Specified Reach Order=DogwoodRun      ,One