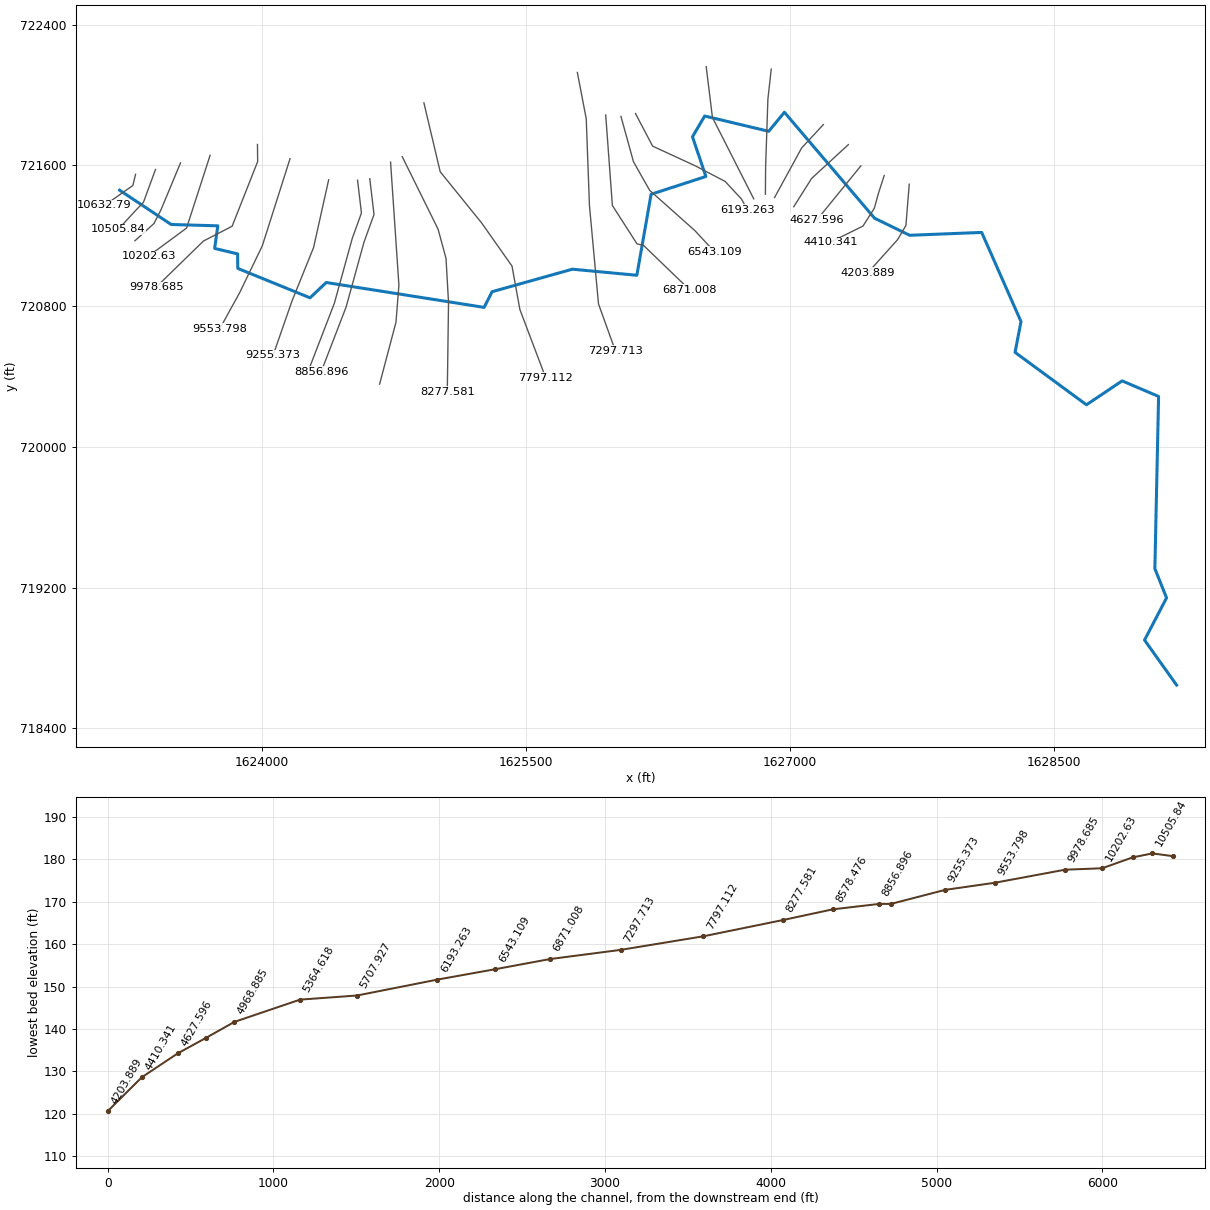
--- East_Branch_Laurel.prj (project) ---

Proj Title=East_Branch_Laurel
Current Plan=p01
Default Exp/Contr=0.3,0.1
English Units
Geom File=g01
Flow File=f01
Plan File=p01
Y Axis Title=Elevation
X Axis Title(PF)=Main Channel Distance
X Axis Title(XS)=Station
BEGIN DESCRIPTION:
East Branch Laurel Run - Georeferenced HEC-RAS model.  This was formerly an approximate method stream.  Projection:  MD Stateplane.  Horizontal datum:  NAD83.  Vertrial datum: NAVD88.  Units:Feet.  Created by: Aaron W. Buesing, USACE- St Paul District as part of FEMA Map Modernization study for Cecil County, MD.
END DESCRIPTION:
DSS File=dss
DSS Export Rating Curves= 0
DSS Export Rating Curve Sorted= 0
DSS Export Volume Flow Curves= 0
DXF OffsetX= 0
DXF OffsetY= 0
DXF ScaleX= 1
DXF ScaleY= 10

--- East_Branch_Laurel.p01 (plan) ---

Plan Title=EastBranchLaurelRun_100yr
Program Version=4.00
Short Identifier=EBLaurel100
Geom File=g01
Flow File=f01
Subcritical Flow
K Sum by GR= 0
Std Step Tol= 0.01
Critical Tol= 0.01
Num of Std Step Trials= 20
Max Error Tol= 0.3
Flow Tol Ratio= 0.001
Split Flow NTrial= 30
Split Flow Tol= 0.02
Split Flow Ratio= 0.02
Log Output Level= 0
Friction Slope Method= 1
Unsteady Friction Slope Method= 2
Unsteady Bridges Friction Slope Method= 1
Secant Critical Depth
Global Vel Dist= 0 , 0 , 0
Global Log Level= 0
CheckData=True
Encroach Param=-1 ,0,0, 0
Computation Interval=1HOUR
Output Interval=1HOUR
Run HTab= 0
Run UNet= 0
Run PostProcess= 0
Run WQNet= 0
UNET Theta= 1
UNET Theta Warmup= 1
UNET ZTol= 0.02
UNET ZSATol= 0.05
UNET MxIter= 20
UNET MaxInSteps= 0
UNET DtIC= 0
UNET DtMin= 0
UNET MaxCRTS= 20
UNET WFStab= 2
UNET SFStab= 1
UNET WFX= 1
UNET SFX= 1
UNET DSS MLevel= 4
UNET DZMax Abort= 100
UNET Convert EG Bridges= 0
UNET Use Existing IB Tables=-1
UNET Froude Reduction=False
UNET Froude Limit= 1
UNET Froude Power= 10
UNET Time Slicing=0,0, 5
Instantaneous Interval=1HOUR
DSS File=dss
Write IC File= 0
Echo Input=False
Echo Output=False
Write Detailed= 0
Detailed Automatic Start=False, 10
WQ ULTIMATE=-1
WQ Max Comp Step=1HOUR
WQ Output Interval=15MIN
WQ Output Selected Increments= 0
WQ Output face flow=0
WQ Output face velocity=0
WQ Output face area=0
WQ Output face dispersion=0
WQ Output cell volume=0
WQ Output cell surface area=0
WQ Output cell continuity=0
WQ Output face conc=0
WQ Output face dconc_dx=0
WQ Output face courant=0
WQ Output face peclet=0
WQ Output face adv mass=0
WQ Output face disp mass=0
WQ Output cell mass=0
WQ Output cell source sink temp=0
WQ Output cell source sink nsm=0
WQ Output MaxMinRange=-1
WQ Create Restart=0
WQ Fixed Restart=0
Sorting and Armoring Iterations= 10
XS Update Threshold= 0.02
Hydraulics Update Threshold= 0.02
Energy Slope Method= 0
Volume Change Method= 0
XS Weighting Method= 0
Number of US Weighted Cross Sections= 1
Number of DS Weighted Cross Sections= 1
Upstream XS Weight=0.25
Main XS Weight=0.5
Downstream XS Weight=0.25
Number of DS XS's Weighted with US Boundary= 1
Upstream Boundary Weight= 1
Weight of XSs Associated with US Boundary= 0
Number of US XS's Weighted with DS Boundary= 1
Downstream Boundary Weight= 0.5
Weight of XSs Associated with DS Boundary= 0.5
Sediment Output Level= 4
Mass or Volume Output= 0
Output Increment Type= 1
Profile and TS Output Increment= 10
XS Output Flag= 0
XS Output Increment= 10
Disregard all LS=0
Disregard all Conn=0
Disregard all Breaches=0
Disregard all Pumps=0

--- East_Branch_Laurel.f01 (steady flow) ---

Flow Title=EastBranchLaurelRun_100yr
Program Version=4.00
Number of Profiles= 2
Profile Names=100CUR,100ULT
River Rch & RM=EastBrachLaurel,Reach1          ,10632.79
    1050    1060
River Rch & RM=EastBrachLaurel,Reach1          ,7297.713
    1080    1090
River Rch & RM=EastBrachLaurel,Reach1          ,6871.008
    1150    1170
River Rch & RM=EastBrachLaurel,Reach1          ,1951.487
    1370    1420
Boundary for River Rch & Prof#=EastBrachLaurel,Reach1          , 1
Up Type= 0
Dn Type= 3
Dn Slope=0.0087
Boundary for River Rch & Prof#=EastBrachLaurel,Reach1          , 2
Up Type= 0
Dn Type= 3
Dn Slope=0.0087
DSS Import GetInterval= 0
DSS Import GetPeak= 0
DSS Import FillOption= 0

--- East_Branch_Laurel.g01 (geometry) ---

Geom Title=EastBranchLaurelRun
Program Version=4.00

River Reach=EastBrachLaurel ,Reach1
Reach XY= 30
 1623191.1007691721458.4982661161623484.04792723721263.626575798
1623749.27810532721255.9511044031623731.36867209721127.600166127
 1623861.8516857 721096.471865491623862.70451589721013.960548043
1624273.68336737 720846.805837751624365.36260898720933.794513494
 1625262.9663467 720792.437915371625308.59275997720881.558666542
1625764.77160966721009.4831897321626131.31801015720974.943568468
1626212.16630876721435.2586444171626523.70516428721536.532225251
1626447.37686546721762.3190087081626516.88252302 721880.22277756
  1626880.870433721793.2341018021626969.99118418721901.543531448
1627482.54210708721299.2322347461627682.10436326721202.222804666
1628091.46283744721218.4265775981628314.90433799720711.845465779
1628281.04698081720536.8020765331628686.99413441720238.737937495
1628889.79714516720374.7643471511629097.03487276720286.070011094
1629075.79940189719307.0209936051629142.32015398 719141.14552854
1629017.12360936718901.4672545791629199.34603386718645.506518513

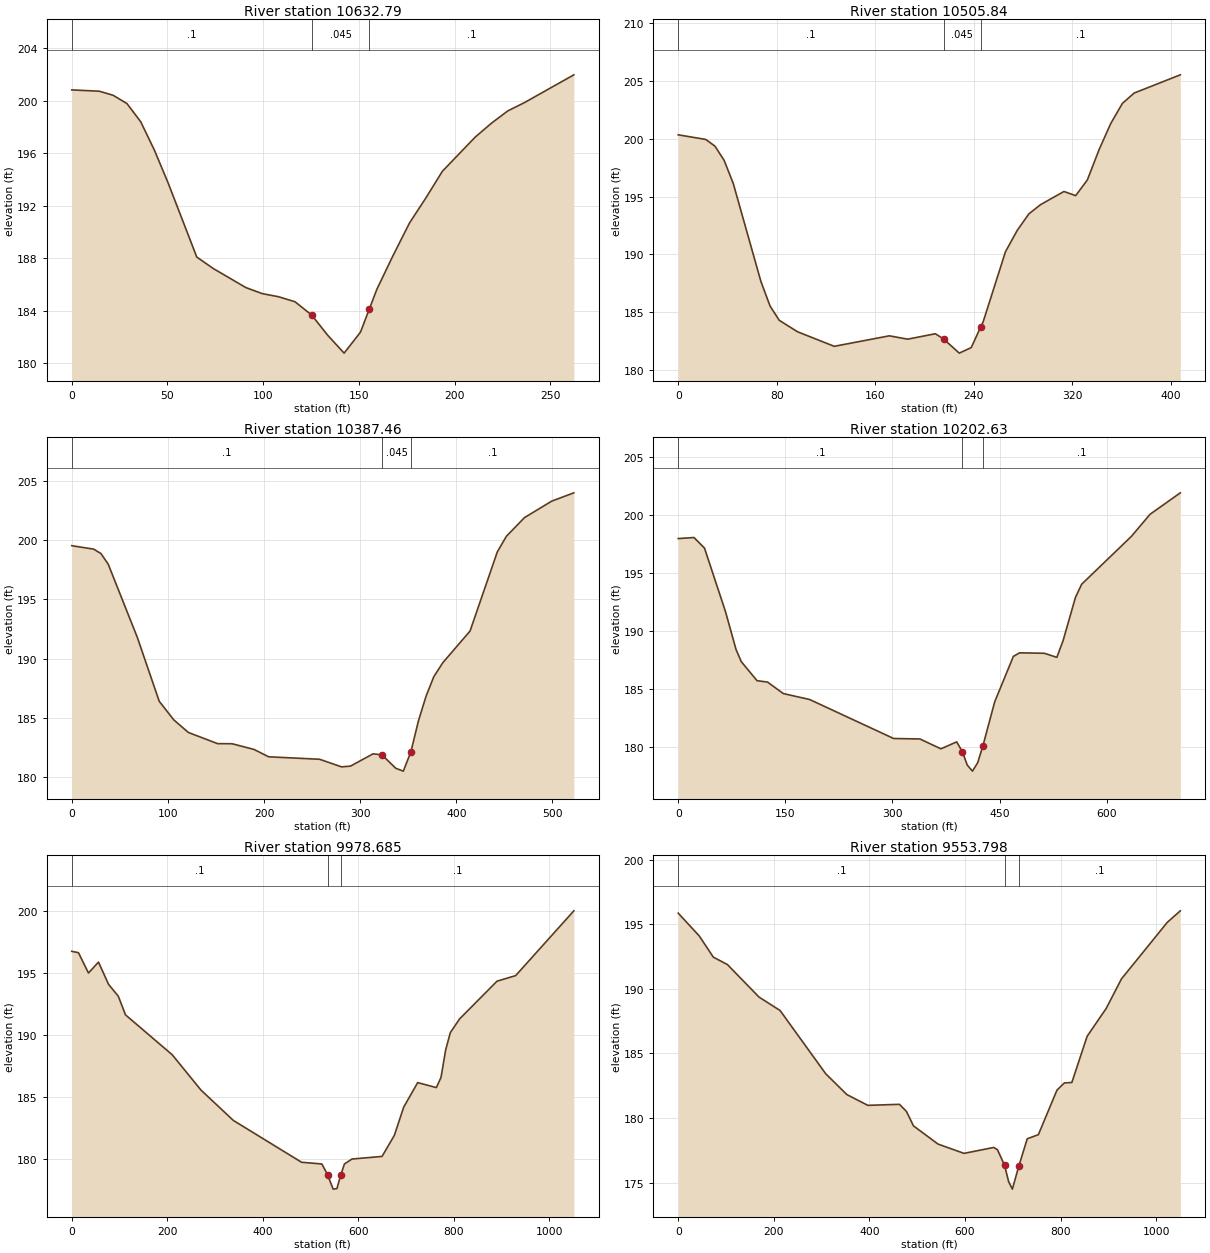
Type RM Length L Ch R = 1 ,10632.79,116.03,126.95,130.92
XS GIS Cut Line= 3
1623281.80654356721548.6117574131623266.37007454721485.150718138
1623105.14473154 721371.94994539
#Sta/Elev= 28
       0  200.84   14.41  200.74   21.61  200.43   28.82   199.8   36.02  198.41
   43.22  196.23   50.43  193.71   65.31  188.09   73.86  187.22   90.97  185.76
   99.52   185.3  108.08  185.06  116.63  184.68  125.38  183.66  133.74  182.12
  142.29  180.76  150.84  182.36  155.47  184.13   159.4  185.63  167.95  188.23
   176.5   190.7  185.06  192.61  193.61  194.63  210.71  197.23  219.27   198.3
  227.82  199.24  236.37  199.86  262.31  201.99
#Mann= 3 , 0 , 0
       0      .1       0  125.38    .045       0  155.47      .1       0
Bank Sta=125.38,155.47
XS Rating Curve= 0 ,0
Exp/Cntr=0.3,0.1

Type RM Length L Ch R = 1 ,10505.84,109.66,118.38,124.91
XS GIS Cut Line= 4
1623395.00731628721576.0543689731623326.40078734 721389.10157761
1623280.09138033721341.0770073531623184.04223982721236.452050731
#Sta/Elev= 30
       0  200.35   22.37  199.95   29.83  199.37   37.28  198.14   44.74  196.12
   67.11  187.66   74.56  185.52   82.02  184.28   96.93  183.28  126.76  182.02
   171.5  182.93  186.41  182.64  208.87  183.11  215.53  182.66  228.32  181.43
  238.04  181.91  245.71  183.69  247.77  184.16  265.86  190.22  275.36  192.06
  284.86   193.5  294.37   194.3  313.37  195.44  322.87  195.08  332.38  196.44
  341.88  199.06  351.38  201.33  360.88  203.08  370.39  203.97  407.89  205.55
#Mann= 3 , 0 , 0
       0      .1       0  215.53    .045       0  245.71      .1       0
Bank Sta=215.53,245.71
XS Rating Curve= 0 ,0
Exp/Cntr=0.3,0.1

Type RM Length L Ch R = 1 ,10387.46,167.94,184.82,186.62
XS GIS Cut Line= 4
1623537.36586386721613.7879599031623425.88025431721346.222497046
1623386.43150018721269.040151984 1623278.3762171721171.275848225
#Sta/Elev= 30
       0  199.52   22.75  199.23   30.33  198.86   37.92  197.96   68.25  191.77
      91  186.39  106.17  184.82  121.33  183.76  151.67  182.82  166.83  182.81
  189.58  182.33  204.75  181.71  257.83   181.5  280.58  180.86  289.86  180.92
  313.45  181.96   322.7  181.87  337.03  180.74  344.89   180.5  352.79  182.14
  360.61  184.74  368.48  186.81  376.54  188.46  385.98  189.65   414.3  192.32
  442.62  198.99  452.06  200.31  470.94  201.89  499.26  203.28  522.26  203.98
#Mann= 3 , 0 , 0
       0      .1       0   322.7    .045       0  352.79      .1       0
Bank Sta=322.7,352.79
XS Rating Curve= 0 ,0
Exp/Cntr=0.3,0.1

Type RM Length L Ch R = 1 ,10202.63,257.06,223.95,163.42
XS GIS Cut Line= 3
1623705.45185973721656.667040497 1623571.6691283721243.312703609
1623355.55856214721083.802523851
#Sta/Elev= 30
       0  197.95   22.07  198.04   36.79  197.13   66.22  191.65   80.93   188.4
   88.29  187.35  110.36  185.71  125.08  185.59  147.15   184.6  183.94  184.09
  301.66  180.73  338.44  180.69  367.87  179.84  389.95  180.44  397.94  179.58
  404.66  178.45  412.02  177.92  419.38  178.65  426.73  180.12  443.16  183.89
  469.27   187.8  477.97  188.11  512.77  188.07  530.17  187.72  538.87  189.15
  556.27  192.89  564.97  194.02  634.57  198.14  660.67  200.04  703.07  201.89
#Mann= 3 , 0 , 0
       0      .1       0  397.94    .045       0  426.73      .1       0
Bank Sta=397.94,426.73
XS Rating Curve= 0 ,0
Exp/Cntr=0.3,0.1

Type RM Length L Ch R = 1 ,9978.685,246.21,424.89,343.59
XS GIS Cut Line= 5
1623974.73248588721718.4129165411623975.73188363721620.892977715
1623830.65877506 721253.603682981623667.71826883721169.560684994
1623398.43764274720907.140711799
#Sta/Elev= 30
       0  196.78      14  196.67      35  195.03      56  195.91      77  194.12
   97.53  193.15  112.58  191.65  210.42  188.43  270.63  185.58  338.37  183.13
  481.36  179.75  523.93  179.61  535.77  178.75  547.56  177.58  555.44  177.62
  563.31   178.7  571.19  179.61  586.94  180.01  649.95  180.22  675.76  181.92
  695.31   184.2  724.64  186.18  763.73  185.78  773.51   186.6  783.28  188.83
  793.05  190.22   812.6  191.33   890.8  194.37  929.89  194.82 1051.76  200.05
#Mann= 3 , 0 , 0
       0      .1       0  535.77    .045       0  563.31      .1       0
Bank Sta=535.77,563.31
XS Rating Curve= 0 ,0
Exp/Cntr=0.3,0.1

Type RM Length L Ch R = 1 ,9553.798,283.13,298.43,288.53
XS GIS Cut Line= 4
1624159.97011399721637.8002450471624002.17509745721142.118073419
1623873.53785566720876.2677737921623760.33708289720670.448186964
#Sta/Elev= 30
       0  195.87   44.08   194.1   73.46  192.46  102.85  191.89  168.96  189.37
  213.04  188.33  308.54  183.43  352.61  181.82  396.69  180.98  462.81  181.06
   477.5  180.51  492.19  179.39  543.52  177.98  597.96  177.26  660.17  177.72
  667.94  177.54  682.67  176.34  691.27  175.07  699.05  174.49  712.71  176.29
  730.16  178.39  753.49  178.71  792.37  182.16  807.92  182.72  823.52  182.75
  855.47  186.33  895.42  188.49  927.37  190.78 1023.24  195.16 1050.43  196.05
#Mann= 3 , 0 , 0
       0      .1       0  682.67    .045       0  712.71      .1       0
Bank Sta=682.67,712.71
XS Rating Curve= 0 ,0
Exp/Cntr=0.3,0.1

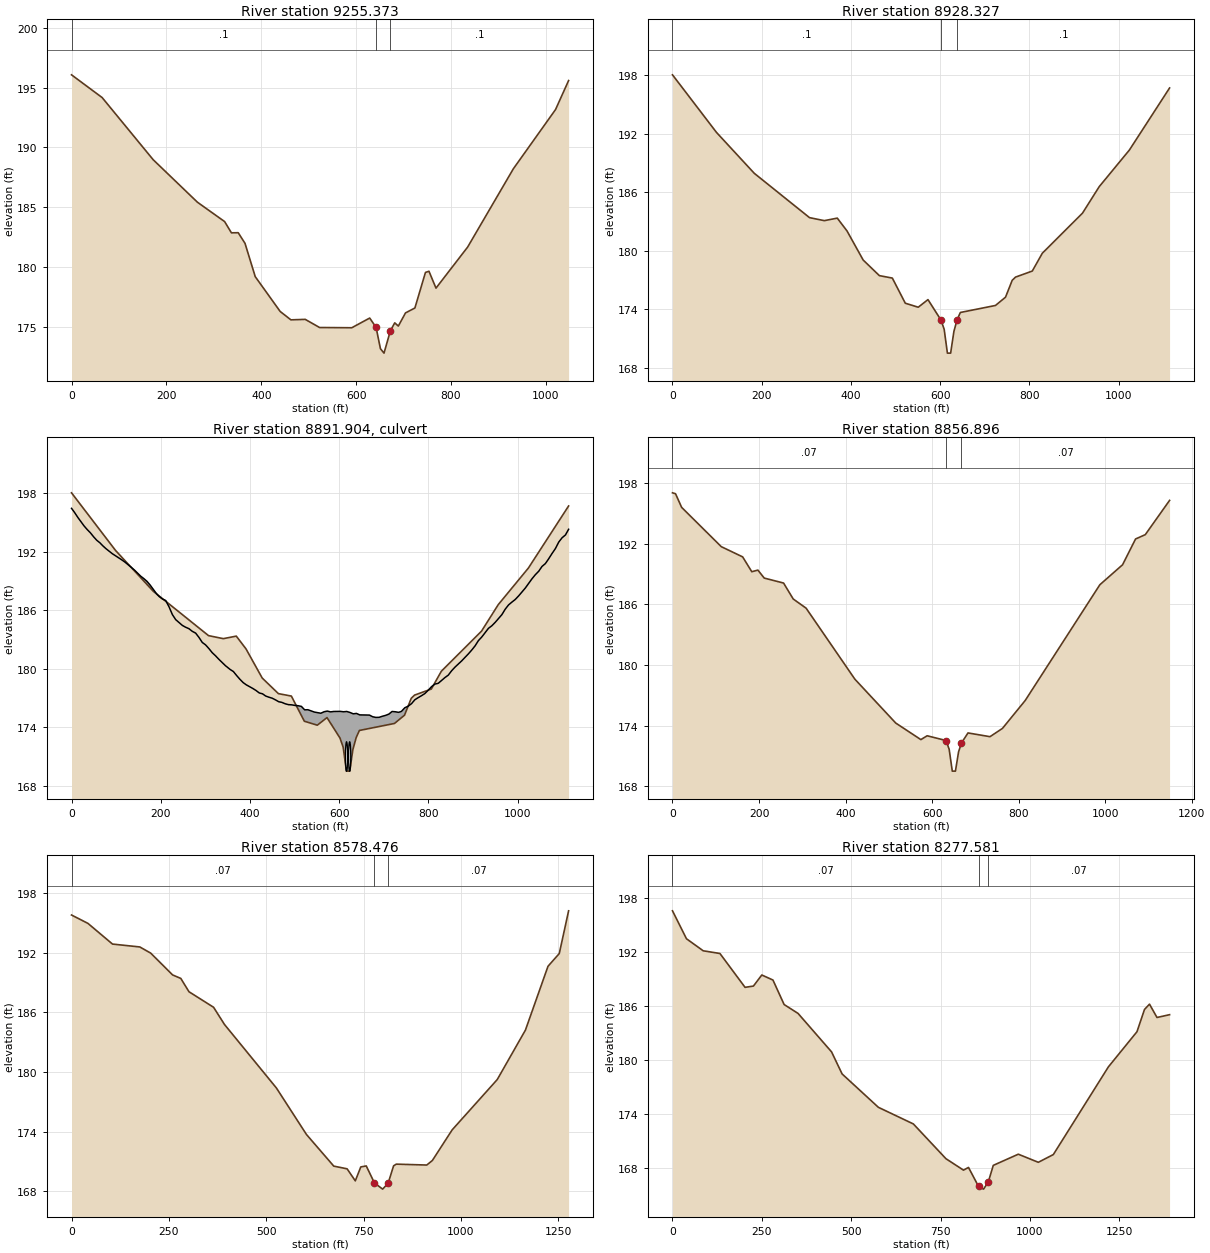
Type RM Length L Ch R = 1 ,9255.373,229.52,327.05,268.69
XS GIS Cut Line= 4
1624379.51100661721517.7388193761624293.64965446 721132.59749037
 1624170.4971375720827.2150539611624063.92097346720521.228986517
#Sta/Elev= 30
       0  196.07   64.55  194.17  172.12  188.98  265.36  185.43  322.73  183.81
  337.08  182.87  351.42  182.88  365.76  181.99  387.28  179.21  439.88   176.3
  462.53   175.6  492.72  175.64  522.91  174.96  590.84  174.94  628.58  175.75
  642.04  174.97  651.22  173.19  658.77  172.82  672.12  174.68  681.41  175.35
  688.96  175.08  704.06  176.18  723.88  176.59  746.11  179.56  753.53  179.66
  768.35  178.25  835.06  181.68  931.43  188.22 1020.38  193.17 1047.89  195.59
#Mann= 3 , 0 , 0
       0      .1       0  642.04    .045       0  672.12      .1       0
Bank Sta=642.04,672.12
XS Rating Curve= 0 ,0
Exp/Cntr=0.5,0.3

Type RM Length L Ch R = 1 ,8928.327,70.24,71.43,70.09
BEGIN DESCRIPTION:
Center of channel lowered about 1.5 feet based on culvert survey info
END DESCRIPTION:
XS GIS Cut Line= 5
1624543.71073078721515.3555272221624565.72599234721328.642968148
 1624513.8276024721185.4644688071624411.79637134720815.601256311
 1624271.3877811720451.494118497
#Sta/Elev= 30
       0  198.05   98.68  192.14  183.26  187.95  307.14   183.4   340.3  183.09
  369.35  183.35  391.13  182.04  427.44  179.05  463.75  177.45  492.79   177.2
  521.84  174.62  550.88  174.21  572.67  174.99  601.71   172.9  608.97  171.95
  616.24   169.5   623.5   169.5  630.76  171.72  638.02  172.93  645.28  173.67
  723.98  174.39  746.49  175.24  761.49  176.97  768.99   177.3  806.51  177.92
  829.01  179.75  919.04  183.86  956.55  186.58 1024.08  190.33 1114.22   196.7
#Mann= 3 , 0 , 0
       0      .1       0  601.71    .045       0  638.02      .1       0
Bank Sta=601.71,638.02
XS Rating Curve= 0 ,0
Exp/Cntr=0.5,0.3

Type RM Length L Ch R = 2 ,8891.904,,,
BEGIN DESCRIPTION:
Deaver Road, CE050307FS-1
Top of road obtained from DEM.
Culverts from MDE2 bridge/culvert surveys.
END DESCRIPTION:
Bridge Culvert--1,0,-1,-1, 0
Deck Dist Width WeirC Skew NumUp NumDn MinLoCord MaxHiCord MaxSubmerge Is_Ogee
26,19,2.6,0, 153, 156, , , 0.95, 0, 3,3,,
       0    7.05    14.1   21.15   28.19   35.24   42.29   49.34   56.39   63.44
   70.48   77.53   84.58   91.63   98.68  105.73  112.78  119.82  126.87  133.92
  140.97  148.02  155.07  162.12  169.16  176.21  183.26  190.31   196.3  203.74
  211.19  218.63  226.08  233.52  240.97  248.42  255.86  263.31  270.75   278.2
  285.64  293.09  300.53  307.98  315.43  322.87  330.32  337.76  345.21   355.5
  362.76  370.03  377.29  384.55  391.81  399.07  406.33   413.6  420.86  428.12
  435.38  442.64   449.9  457.16  464.43  471.69  478.95  486.21  493.47  500.73
  507.99  515.26  522.52  529.78  537.04   544.3  551.56  558.82  566.09  573.35
  580.61  587.87  595.13  602.39  609.65  616.92  624.18  631.44   638.7  645.96
  653.22  660.49  667.75  675.01  682.27  689.53  696.79  704.05  711.32  718.58
  725.84   733.1  739.54  747.04  754.54  762.05  769.55  777.05  784.55  792.06
  799.56  807.06  814.56  822.07  829.57  837.07  844.57  852.08  859.58  867.08
  874.58  882.08  889.59  897.09  904.59  912.09   919.6   927.1   934.6   942.1
  949.61  957.11  964.61  972.11  979.62  987.12  994.62 1002.12 1009.63 1017.13
 1024.63 1032.13 1039.64 1047.14 1054.64 1062.14 1069.65 1077.15 1084.65 1092.15
 1099.66 1107.16 1114.22
  196.46  196.02  195.53  195.08  194.65  194.28  193.95  193.55  193.19  192.93
   192.6  192.31  192.06   191.8  191.59  191.38  191.17  190.94  190.68  190.41
  190.13  189.81   189.5  189.25  188.97  188.59  188.15  187.71  187.42  187.16
     187  186.35  185.56  185.04  184.75  184.45  184.26  184.11  183.84  183.66
  183.22   182.7  182.45  182.07  181.65  181.33  180.97  180.64  180.31  179.93
  179.72  179.31  178.93  178.59  178.35  178.17  177.98  177.77  177.52  177.43
   177.2  177.08  176.98  176.81  176.62  176.55  176.41  176.32   176.3  176.24
  176.21  176.14  175.79   175.8  175.68  175.56   175.5  175.44  175.59  175.66
  175.58  175.62  175.63  175.63  175.59  175.62  175.52  175.38  175.42  175.27
  175.26  175.24  175.25  175.08  175.01  175.02  175.13  175.22  175.35  175.62
  175.59  175.53  175.63     176  176.16  176.42  176.82  177.04  177.24  177.46
   177.8  178.17  178.43  178.51  178.81   179.1  179.35   179.8  180.17  180.49
  180.81  181.17  181.53  181.92  182.35  182.89  183.26   183.7  184.15  184.41
  184.76  185.16  185.55  186.11  186.55  186.84  187.11  187.47  187.87  188.28
  188.75  189.23  189.65     190   190.5  190.79  191.29  191.83  192.33     193
  193.44  193.73  194.31
                                                                                
                                                                                
                                                                                
                                                                                
                                                                                
                                                                                
                                                                                
                                                                                
                                                                                
                                                                                
                                                                                
                                                                                
                                                                                
                                                                                
                                                                                
                        
       0    7.05    14.1   21.15   28.19   35.24   42.29   49.34   56.39   63.44
   70.48   77.53   84.58   91.63   98.68  105.73  112.78  119.82  126.87  133.92
  140.97  148.02  155.07  162.12  169.16  176.21  183.26  190.31   196.3  203.74
  211.19  218.63  226.08  233.52  240.97  248.42  255.86  263.31  270.75   278.2
  285.64  293.09  300.53  307.98  315.43  322.87  330.32  337.76  345.21   355.5
  362.76  370.03  377.29  384.55  391.81  399.07  406.33   413.6  420.86  428.12
  435.38  442.64   449.9  457.16  464.43  471.69  478.95  486.21  493.47  500.73
  507.99  515.26  522.52  529.78  537.04   544.3  551.56  558.82  566.09  573.35
  580.61  587.87  595.13  602.39  609.65  616.92  624.18  631.44   638.7  645.96
  653.22  660.49  667.75  675.01  682.27  689.53  696.79  704.05  711.32  718.58
  725.84   733.1  739.54  747.04  754.54  762.05  769.55  777.05  784.55  792.06
  799.56  807.06  814.56  822.07  829.57  837.07  844.57  852.08  859.58  867.08
  874.58  882.08  889.59  897.09  904.59  912.09   919.6   927.1   934.6   942.1
  949.61  957.11  964.61  972.11  979.62  987.12  994.62 1002.12 1009.63 1017.13
 1024.63 1032.13 1039.64 1047.14 1054.64 1062.14 1069.65 1077.15 1084.65 1092.15
 1099.66 1107.16 1114.66 1122.16 1131.51  1148.8
  196.46  196.02  195.53  195.08  194.65  194.28  193.95  193.55  193.19  192.93
   192.6  192.31  192.06   191.8  191.59  191.38  191.17  190.94  190.68  190.41
  190.13  189.81   189.5  189.25  188.97  188.59  188.15  187.71  187.42  187.16
     187  186.35  185.56  185.04  184.75  184.45  184.26  184.11  183.84  183.66
  183.22   182.7  182.45  182.07  181.65  181.33  180.97  180.64  180.31  179.93
  179.72  179.31  178.93  178.59  178.35  178.17  177.98  177.77  177.52  177.43
   177.2  177.08  176.98  176.81  176.62  176.55  176.41  176.32   176.3  176.24
  176.21  176.14  175.79   175.8  175.68  175.56   175.5  175.44  175.59  175.66
  175.58  175.62  175.63  175.63  175.59  175.62  175.52  175.38  175.42  175.27
  175.26  175.24  175.25  175.08  175.01  175.02  175.13  175.22  175.35  175.62
  175.59  175.53  175.63     176  176.16  176.42  176.82  177.04  177.24  177.46
   177.8  178.17  178.43  178.51  178.81   179.1  179.35   179.8  180.17  180.49
  180.81  181.17  181.53  181.92  182.35  182.89  183.26   183.7  184.15  184.41
  184.76  185.16  185.55  186.11  186.55  186.84  187.11  187.47  187.87  188.28
  188.75  189.23  189.65     190   190.5  190.79  191.29  191.83  192.33     193
  193.44  193.73  194.31  194.91  195.63   196.3
                                                                                
                                                                                
                                                                                
                                                                                
                                                                                
                                                                                
                                                                                
                                                                                
                                                                                
                                                                                
                                                                                
                                                                                
                                                                                
                                                                                
                                                                                
                                                
BR Coef=-1 , 0 , 0 ,, 0 ,,,0.8,0,,0,
WSPro=,,,, 1 ,,,, 0 ,,,, 0 ,,,,-1 ,-1 ,-1 , 0 , 0 , 0 , 0 , 0
Multiple Barrel Culv=3,3,4.83,28,0.025,0.9,1,34,3,169.5,169.5, 2,Culvert #1  , 0 ,22
   616.5   646.7   623.5   653.7
Culvert Bottom n=0.025
BC Design=,, 0 ,, 0 ,,,,,,
BC Use User HTab Curves=0
BC User HTab FreeFlow(D)= 0

Type RM Length L Ch R = 1 ,8856.896,264.34,278.42,283.1
BEGIN DESCRIPTION:
Center of channel lowered about 1.5 feet based on culvert survey info
END DESCRIPTION:
XS GIS Cut Line= 5
1624613.22915031721523.5524380211624637.18577491721320.375080034
1624580.57536246721164.1969422251624478.35473019720793.647150248
1624336.69986849720426.308185101
#Sta/Elev= 30
       0  197.05    7.05  196.96   21.15  195.61  112.78  191.72  162.12  190.71
  183.26  189.24  197.36   189.4  212.03  188.61   256.7  188.12  279.04  186.54
  308.82  185.63  421.54   178.6  515.94  174.26  574.03  172.62  588.55     173
  632.12  172.53  639.38  171.67  646.64   169.5   653.9   169.5  661.17  171.41
  667.91  172.29  682.95  173.28  733.78  172.91   762.6  173.73  815.12  176.49
  987.67  187.95 1040.19  189.93  1070.2  192.48 1092.71  192.91  1148.8   196.3
#Mann= 3 , 0 , 0
       0     .07       0  632.12    .045       0  667.91     .07       0
Bank Sta=632.12,667.91
XS Rating Curve= 0 ,0
Exp/Cntr=0.5,0.3

Type RM Length L Ch R = 1 ,8578.476,280.93,300.89,294.03
XS GIS Cut Line= 4
 1624731.3327364721618.1554683451624778.73251864720919.008680105
1624762.14259489720708.0796490611624668.86028029720355.957721502
#Sta/Elev= 30
       0  195.77    42.1  194.93  105.24  192.85   175.4  192.56  203.47  191.94
  259.59  189.75  280.64   189.4  301.69  188.06  364.84   186.5   392.9  184.77
  526.21  178.39  603.38  173.72  673.54  170.54  707.77  170.27  728.84  169.06
  742.88  170.46  756.92  170.56  777.99  168.85  799.05  168.23   813.1  168.82
  827.14  170.57  834.16  170.74  912.33  170.65  926.81  171.11   977.5  174.18
 1093.37  179.24 1165.78  184.21 1223.71  190.62 1252.68   191.9  1276.6  196.19
#Mann= 3 , 0 , 0
       0     .07       0  777.99    .045       0   813.1     .07       0
Bank Sta=777.99,813.1
XS Rating Curve= 0 ,0
Exp/Cntr=0.3,0.1

Type RM Length L Ch R = 1 ,8277.581,392.14,480.47,415.11
XS GIS Cut Line= 6
1624797.69243155721648.9653268311625001.51149525 721236.58722122
1625046.54128841721070.6879833041625060.76122306720819.469137371
1625056.02124482720473.4507269111625053.65125574720312.291467249
#Sta/Elev= 30
       0  196.62   39.04  193.52   85.89  192.18  132.74  191.88  203.02  188.12
  226.44  188.26  249.87  189.49   281.1  188.93  312.33  186.21  351.37  185.22
  445.07  180.95   474.5   178.5  576.05  174.79  673.97  172.94  765.11  169.08
  814.19  167.81  828.21  168.11  856.26     166  870.28   165.7  883.52  166.49
  897.52  168.34  967.53  169.58 1023.53  168.68 1065.54  169.54 1219.55  179.28
 1299.58  183.19 1320.58  185.66 1334.58  186.25 1355.58  184.77 1390.75  185.08
#Mann= 3 , 0 , 0
       0     .07       0  856.26    .045       0  883.52     .07       0
Bank Sta=856.26,883.52
XS Rating Curve= 0 ,0
Exp/Cntr=0.3,0.1

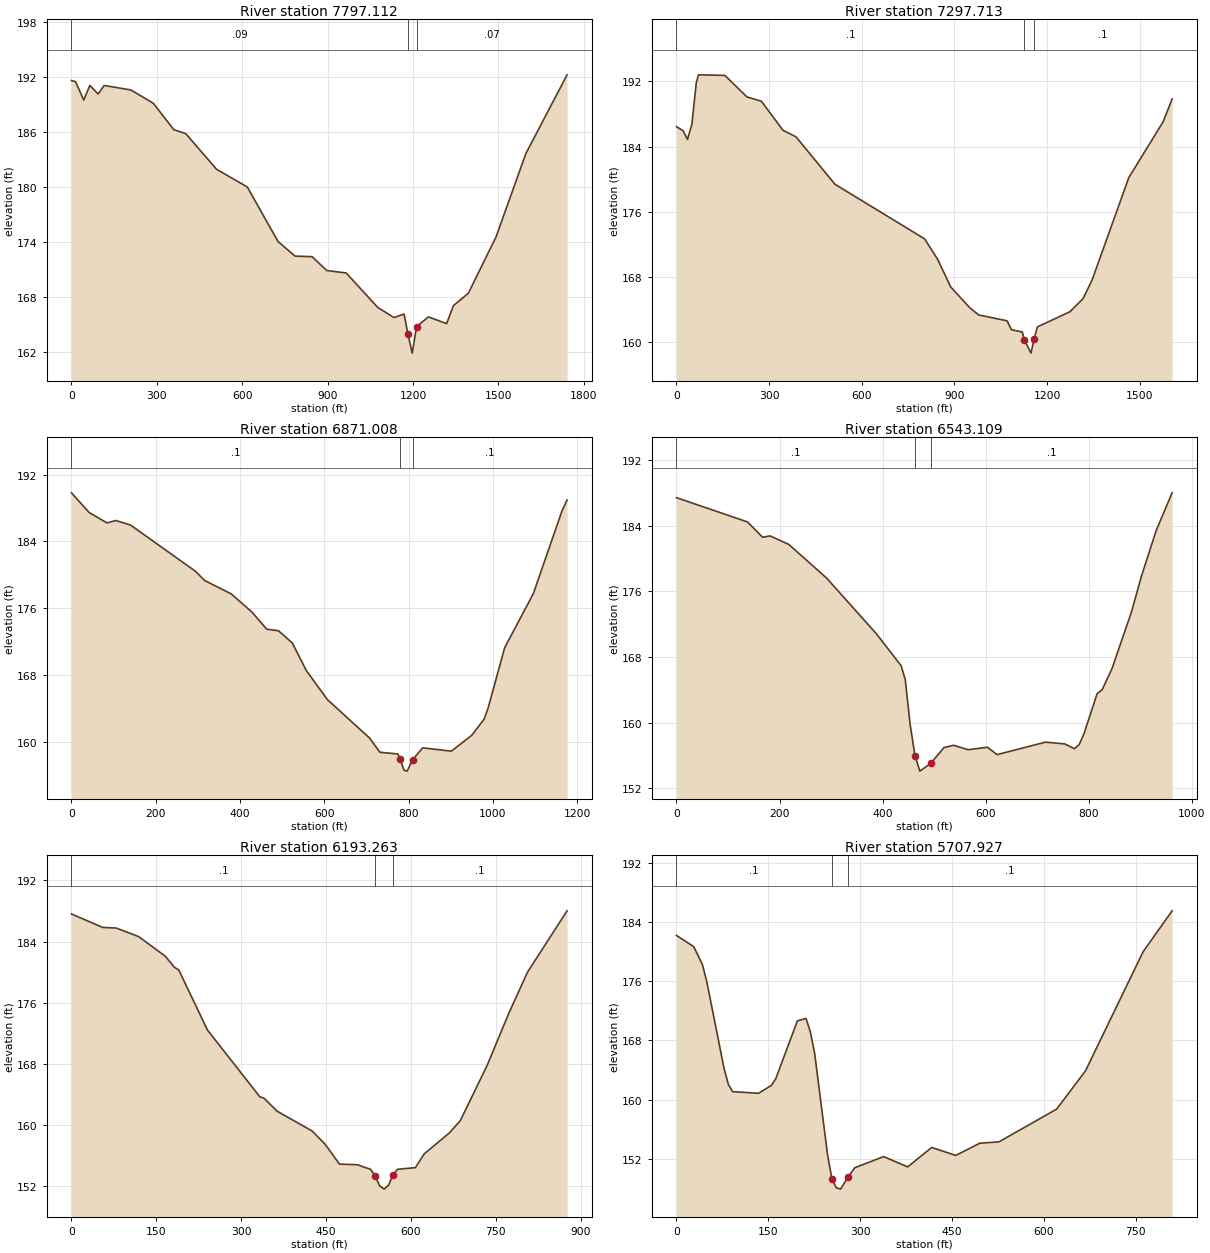
Type RM Length L Ch R = 1 ,7797.112,481.66,499.4,462.84
XS GIS Cut Line= 6
1624920.93186542721954.6939223711625013.36144082721563.645718768
 1625249.3172625 721271.850340591625421.65477213721027.173629344
1625466.33486725720780.3692945091625612.96868634720392.871097073
#Sta/Elev= 30
       0  191.59   14.39  191.47   43.16  189.46   64.74  191.06   93.51  190.12
  115.09  191.05  208.59  190.56  287.72  189.11  359.64  186.23  401.82  185.79
  509.85  181.91  617.88  179.98   725.9  174.03  785.64  172.44  845.58  172.38
  896.95  170.87  965.45   170.6 1076.36  166.84 1133.27  165.74 1168.84  166.12
  1182.3  163.93 1197.29  161.86 1212.77  164.76  1254.2  165.81 1318.23  165.08
 1342.14  167.04 1394.54  168.39 1491.83  174.53 1596.61  183.62 1741.49  192.21
#Mann= 3 , 0 , 0
       0     .09       0  1182.3    .045       0 1212.77     .07       0
Bank Sta=1182.3,1212.77
XS Rating Curve= 0 ,0
Exp/Cntr=0.3,0.1

Type RM Length L Ch R = 1 ,7297.713,367.02,426.7,420.7
XS GIS Cut Line= 5
1625793.08785889722127.7031275931625843.56213389721864.572651446
1625861.81754319 721371.676600621625913.33714345720811.800973758
1626008.75686817720546.920389399
#Sta/Elev= 30
       0  186.45   21.38  185.95   35.64  184.88   49.89  186.74   64.15  191.84
   71.28  192.81  156.81  192.74  228.08   190.1  274.93  189.57  344.98     186
  387.01   185.2   513.1  179.38  803.34  172.68  845.52  170.18   887.7  166.79
  950.96  164.17  979.08  163.33 1070.46  162.62 1084.52  161.52 1119.67  161.25
  1126.7  160.28 1147.79  158.65 1158.45  160.44 1168.88  161.87 1274.32  163.74
  1316.5  165.33 1345.72  167.62 1464.77   180.2 1576.37  187.08 1604.94  189.85
#Mann= 3 , 0 , 0
       0      .1       0  1126.7    .045       0 1158.45      .1       0
Bank Sta=1126.7,1158.45
XS Rating Curve= 0 ,0
Exp/Cntr=0.3,0.1

Type RM Length L Ch R = 1 ,6871.008,301.22,327.9,271.28
XS GIS Cut Line= 5
1625954.24711858721885.964238122 1625992.1669444 721371.67660062
1626131.99630204721153.6376022551626169.91612786721144.157645822
1626430.61493023720892.938799858
#Sta/Elev= 30
       0  189.81   42.11  187.45   84.23  186.21  105.29  186.49  140.38  185.95
   294.8  180.39  315.86  179.31  379.03  177.71  428.16  175.53  463.25  173.48
  491.33  173.29     524  171.82  557.26  168.52  607.16  165.05  706.95  160.46
  731.89  158.74  774.71  158.53  779.46  157.91  789.14  156.59  796.35  156.48
  809.56  157.86  833.24  159.27  901.29  158.87  949.89  160.78  979.06  162.71
  988.78  164.08 1027.66  171.25 1095.71  177.73 1163.76  187.64 1175.84  188.95
#Mann= 3 , 0 , 0
       0      .1       0  779.46    .045       0  809.56      .1       0
Bank Sta=779.46,809.56
XS Rating Curve= 0 ,0
Exp/Cntr=0.3,0.1

Type RM Length L Ch R = 1 ,6543.109,310.07,349.85,323.63
XS GIS Cut Line= 5
1626040.94067574721877.6459840691626112.10040031721620.104604945
1626203.98905173721457.8432687671626460.74339104721229.200718462
1626572.81427701721108.607809126
#Sta/Elev= 30
       0  187.42  137.98  184.46  167.03   182.6  181.56  182.76  217.87  181.73
  291.32  177.63  387.86  170.85  436.13  166.94  444.17  165.23  453.66  159.72
  463.04  155.98  472.41   154.1  493.55  155.05  519.28  156.97  538.02  157.25
  566.14  156.71  603.64  157.01  622.38  156.11  716.11  157.63  753.61  157.42
  772.35  156.83  781.73  157.33   791.1  158.67  816.58  163.55  826.14     164
  845.25  166.57  883.47  173.55  902.58  177.86  931.25  183.43  962.09  188.01
#Mann= 3 , 0 , 0
       0      .1       0  463.04    .045       0  493.55      .1       0
Bank Sta=463.04,493.55
XS Rating Curve= 0 ,0
Exp/Cntr=0.3,0.1

Type RM Length L Ch R = 1 ,6193.263,424.37,485.33,319.51
XS GIS Cut Line= 6
1626123.40192337721894.5130574551626220.85612515721708.975250229
1626460.74339104721598.4022136031626633.16236338721508.444488898
1626726.86832659721407.2420486211626760.04341689721345.606720403
#Sta/Elev= 30
       0  187.61   55.35  185.85   79.07  185.77   118.6  184.66  166.04  182.08
  181.86  180.65  189.76  180.28  240.41  172.44   332.9  163.72  340.61  163.51
  363.73  161.82  425.39  159.24  448.52   157.5  473.72  154.91   505.3  154.83
  528.99  154.22  536.88  153.33  544.78  152.08  552.67  151.64  560.57  152.16
  568.42  153.51  576.36  154.23  607.94  154.45  623.73  156.26  668.19     159
  687.27  160.58  734.97  167.84  773.13  174.63  806.12     180  876.11  188.02
#Mann= 3 , 0 , 0
       0      .1       0  536.88    .045       0  568.42      .1       0
Bank Sta=536.88,568.42
XS Rating Curve= 0 ,0
Exp/Cntr=0.3,0.1

Type RM Length L Ch R = 1 ,5707.927,333.14,343.31,300.23
XS GIS Cut Line= 3
1626525.41449477722160.8829751611626560.96433143721871.744303405
1626795.59325361721409.596426427
#Sta/Elev= 30
       0  182.21   28.21  180.69   42.32  178.28   49.37  176.01   77.58  164.27
   84.63  162.07   91.69  161.07     134  160.85  155.16  161.92  162.21  162.82
  197.48  170.65  211.58  170.98  218.63  169.17  225.69  166.26  246.84   152.5
   253.9  149.26  260.95  148.07     268  147.88  280.61  149.55  291.32  150.78
  338.42  152.28  377.67  150.89  416.92  153.52  456.18  152.44  495.43  154.09
  526.83  154.28  621.04  158.71  668.14  163.89  762.34  180.02  809.61  185.54
#Mann= 3 , 0 , 0
       0      .1       0   253.9    .045       0  280.61      .1       0
Bank Sta=253.9,280.61
XS Rating Curve= 0 ,0
Exp/Cntr=0.3,0.1

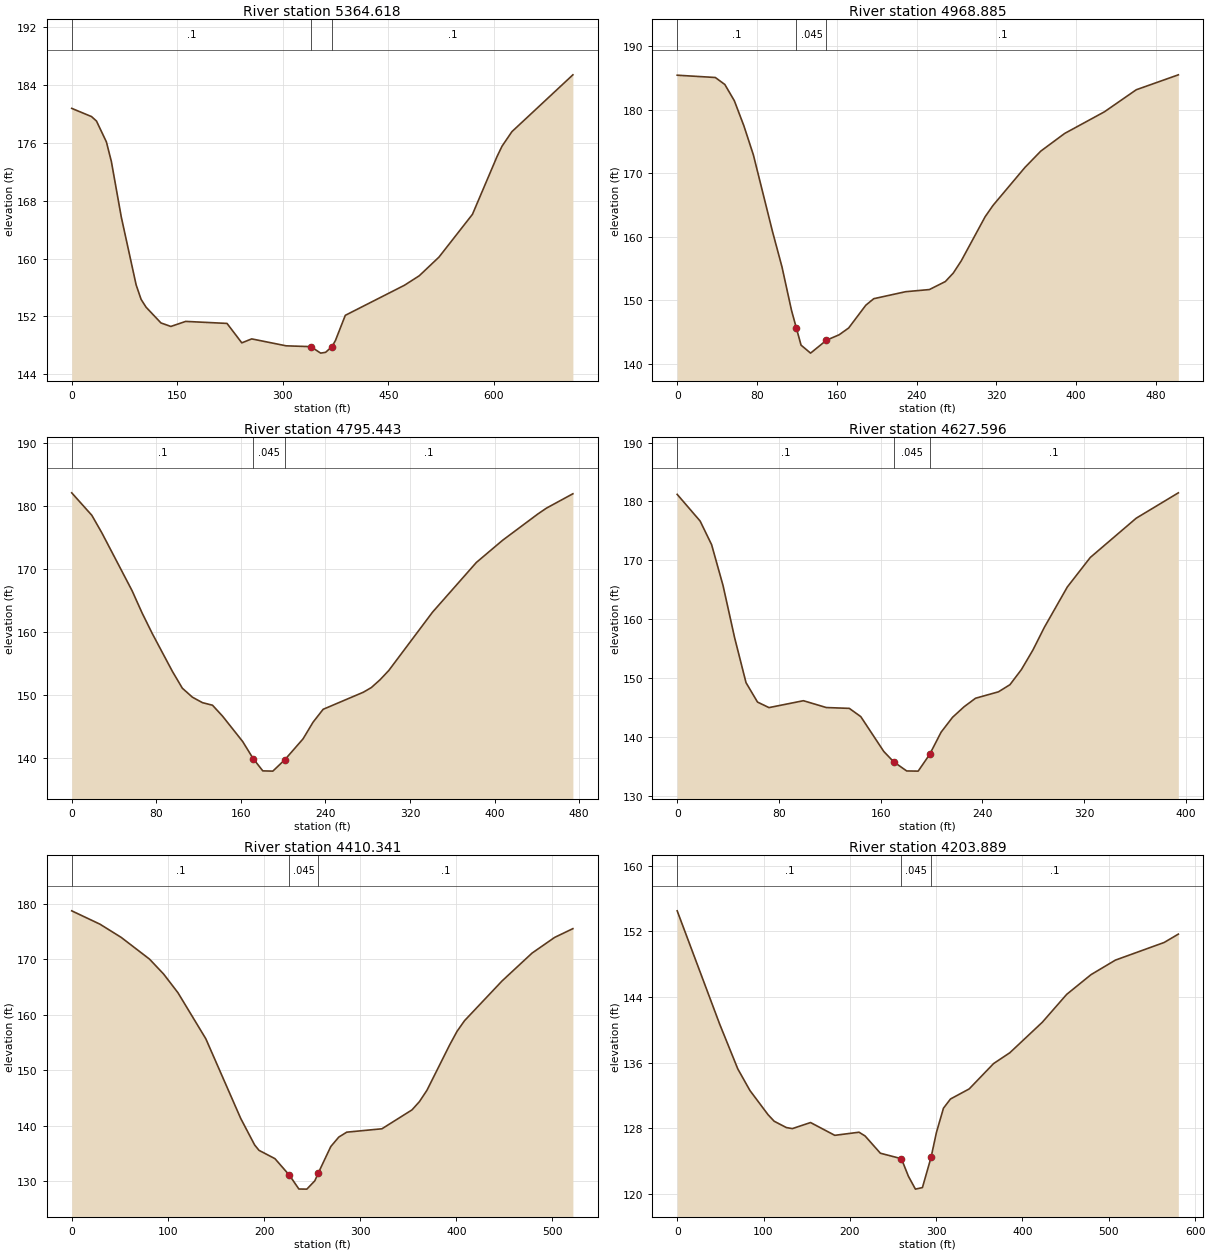
Type RM Length L Ch R = 1 ,5364.618,344.73,395.73,232.07
XS GIS Cut Line= 4
1626895.13279635722146.6630404891626876.17288344721976.023824379
1626863.20511127721592.3855413791626861.95294876721435.666306674
#Sta/Elev= 30
       0  180.78   28.17  179.64   35.22  179.02    49.3  176.13   56.34  173.43
   70.43  165.75   91.56  156.35    98.6  154.35  105.65  153.27  126.78  151.09
  140.86   150.6  161.99   151.3  220.72  151.02  241.73  148.33  255.74  148.88
  304.77  147.92  339.82147.8076  353.79  146.91   360.8  147.02  369.88  147.81
  374.81  148.66  388.81  152.14  472.86   156.3  493.87  157.61  521.89  160.19
  569.55  166.12  604.55  174.13  611.55  175.54  625.55  177.55  712.27  185.42
#Mann= 3 , 0 , 0
       0      .1       0  339.82    .045       0  369.88      .1       0
Bank Sta=339.82,369.88
XS Rating Curve= 0 ,0
Exp/Cntr=0.3,0.1

Type RM Length L Ch R = 1 ,4968.885,172.91,173.44,169.33
XS GIS Cut Line= 3
1627191.38143544721831.4544885011627068.14200155721698.735098213
1626914.09270926721416.706393763
#Sta/Elev= 30
       0  185.42   38.21  185.06   47.76  183.96   57.31   181.4   66.87  177.45
   76.42  172.86   95.52  160.83  105.08  155.23  114.63  148.39  119.59  145.55
  124.18  142.92  133.73  141.66  149.64  143.69  162.39  144.55  171.94  145.62
  189.09   149.2  197.07  150.23  228.97  151.33   252.9  151.67  268.85  152.93
  276.83  154.27   284.8  156.19  308.73  163.13  316.71  164.93  348.61  170.89
  364.57  173.47  388.49  176.25  428.38  179.66  460.28  183.13  502.47  185.48
#Mann= 3 , 0 , 0
       0      .1       0  119.59    .045       0  149.64      .1       0
Bank Sta=119.59,149.64
XS Rating Curve= 0 ,0
Exp/Cntr=0.3,0.1

Type RM Length L Ch R = 1 ,4795.443,164.75,167.85,169.38
XS GIS Cut Line= 3
1627333.58078216721717.6950110941627125.02174029721525.725892946
1627023.11220841721364.566633284
#Sta/Elev= 30
       0  182.14   19.03  178.56   28.54  175.76   57.08  166.57    66.6  163.01
   76.11  159.77   95.14  153.75  104.65  151.04  114.17  149.61  123.68  148.74
  133.19  148.33  142.71  146.59  161.74  142.55  171.68  139.83  180.76  137.88
  190.28  137.84   201.7  139.67  218.82  142.97  228.33  145.63  237.85  147.68
   275.9   150.4  283.46  151.14  291.74  152.39  300.02  153.87  341.43  163.16
  382.84  171.06  407.69  174.59  440.82  178.75   449.1   179.7  474.14  181.99
#Mann= 3 , 0 , 0
       0      .1       0  171.68    .045       0   201.7      .1       0
Bank Sta=171.68,201.7
XS Rating Curve= 0 ,0
Exp/Cntr=0.3,0.1

Type RM Length L Ch R = 1 ,4627.596,216.2,217.26,219.61
XS GIS Cut Line= 2
1627404.68045557721596.8255663371627155.83159876721291.096970797
#Sta/Elev= 30
       0  181.21   18.05  176.68   27.08  172.67    36.1  165.71   45.13  156.92
   54.15  149.25   63.18  145.96   72.21  145.02   99.28  146.19  117.33  145.03
  135.39  144.89  144.41  143.49  162.46  137.59  170.18  135.84  180.51  134.27
  189.54  134.24  198.57  137.07  207.59  140.85  216.62  143.38  225.64  145.16
  234.67  146.61  252.72   147.7  261.75  148.91  270.77  151.48   279.8  154.79
  288.82  158.65  306.87  165.49  324.93   170.5  361.03  177.16   394.2  181.47
#Mann= 3 , 0 , 0
       0      .1       0  170.18    .045       0  198.57      .1       0
Bank Sta=170.18,198.57
XS Rating Curve= 0 ,0
Exp/Cntr=0.3,0.1

Type RM Length L Ch R = 1 ,4410.341,206.67,206.45,207.05
XS GIS Cut Line= 5
1627537.39984587 721542.31581676 1627503.4247411721437.236034945
 1627481.1695748 721355.889565141627416.70633461721254.590187654
1627231.67125034721163.117558703
#Sta/Elev= 30
       0  178.72   29.43  176.31    51.5  173.93   80.92  170.02   95.64  167.32
  110.44  163.98  139.46  155.68  175.75  141.33  190.27  136.54  194.77  135.58
  211.37  134.08  226.48  131.08  236.26  128.61  244.55  128.59  252.85  130.09
  256.46   131.5  269.45  136.26  277.74  137.96  286.04  138.85  322.65  139.46
  353.89  142.86  361.69  144.36   369.5  146.41  392.93  154.51  400.74  157.01
  408.55  158.93  447.59  166.09  478.82  171.11  502.25  173.93  521.25  175.51
#Mann= 3 , 0 , 0
       0      .1       0  226.48    .045       0  256.46      .1       0
Bank Sta=226.48,256.46
XS Rating Curve= 0 ,0
Exp/Cntr=0.3,0.1

Type RM Length L Ch R = 1 ,4203.889,278.58,295.39,286.18
XS GIS Cut Line= 4
1627679.59919265721492.5460453781627660.63927974721257.917123213
 1627613.2394975721177.3374933751627444.97027053720990.108353496
#Sta/Elev= 30
       0   154.5   49.16   140.7   70.23  135.22   84.27  132.59  105.34  129.63
  112.37  128.84  126.41  128.07  133.43  127.94   154.5  128.68  182.59  127.12
  210.68   127.5  217.71  127.04  235.39  124.94  259.76  124.27  267.88  122.13
     276  120.56  284.12  120.75  294.08  124.42  300.36  127.48  308.49  130.43
  316.61  131.55  338.29  132.78  366.53  135.87  385.35  137.19     423  140.91
  451.23  144.31  479.47  146.72   507.7  148.49  564.17  150.64  580.61  151.66
#Mann= 3 , 0 , 0
       0      .1       0  259.76    .045       0  294.08      .1       0
Bank Sta=259.76,294.08
XS Rating Curve= 0 ,0
Exp/Cntr=0.3,0.1