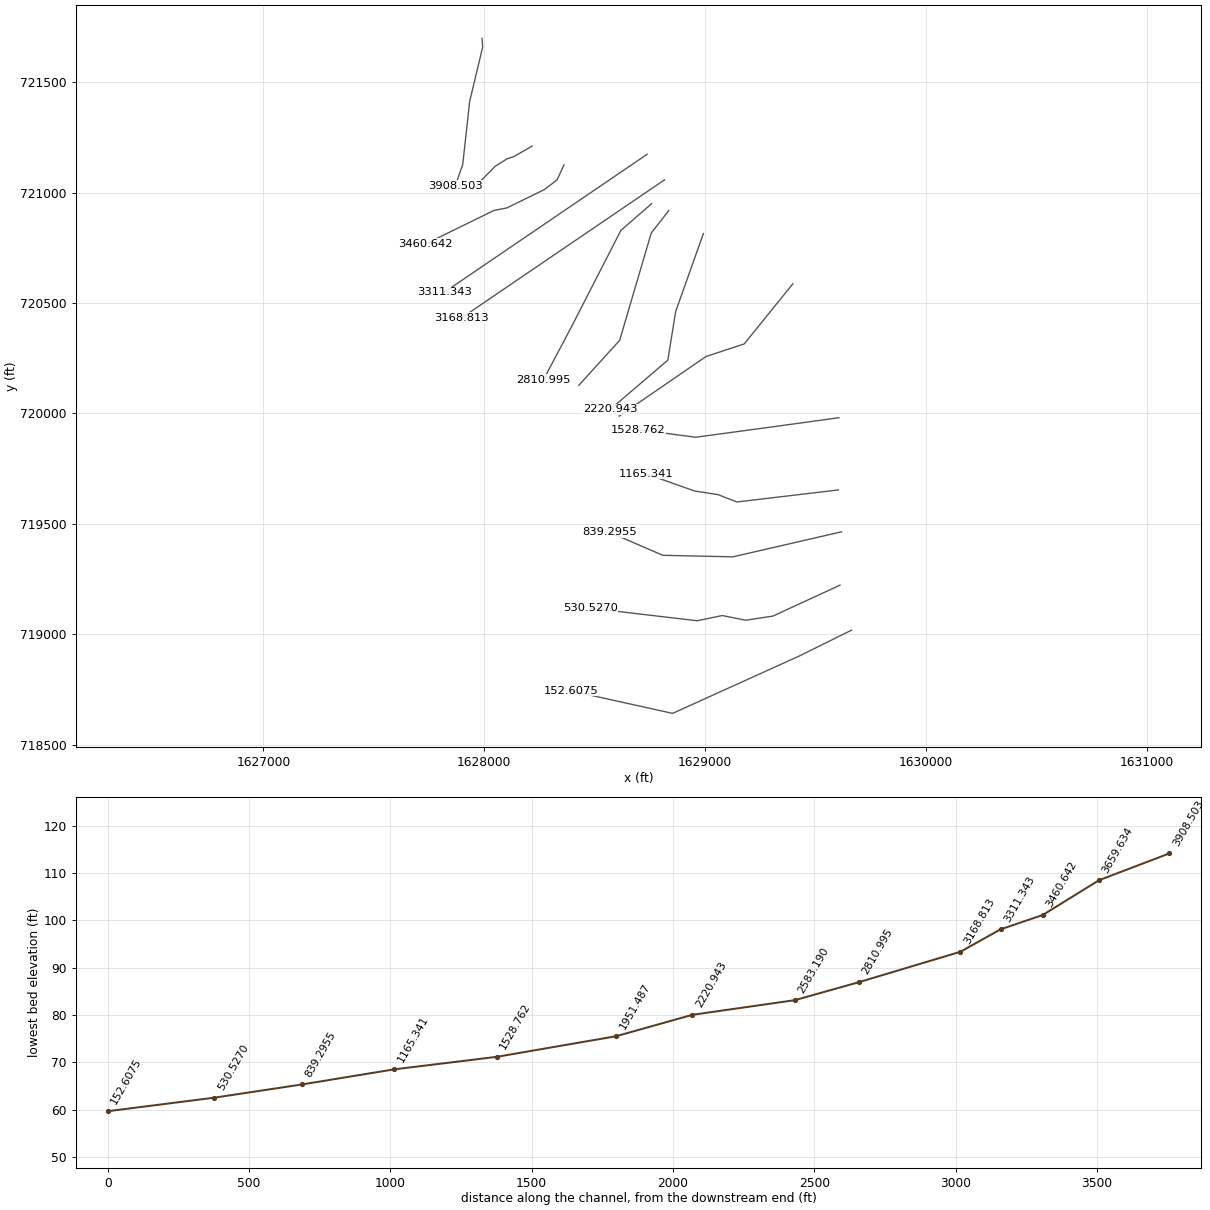
HEC-RAS study East_Branch_Laurel.prj: East_Branch_Laurel

--- East_Branch_Laurel.g01 (geometry) --- (continued)

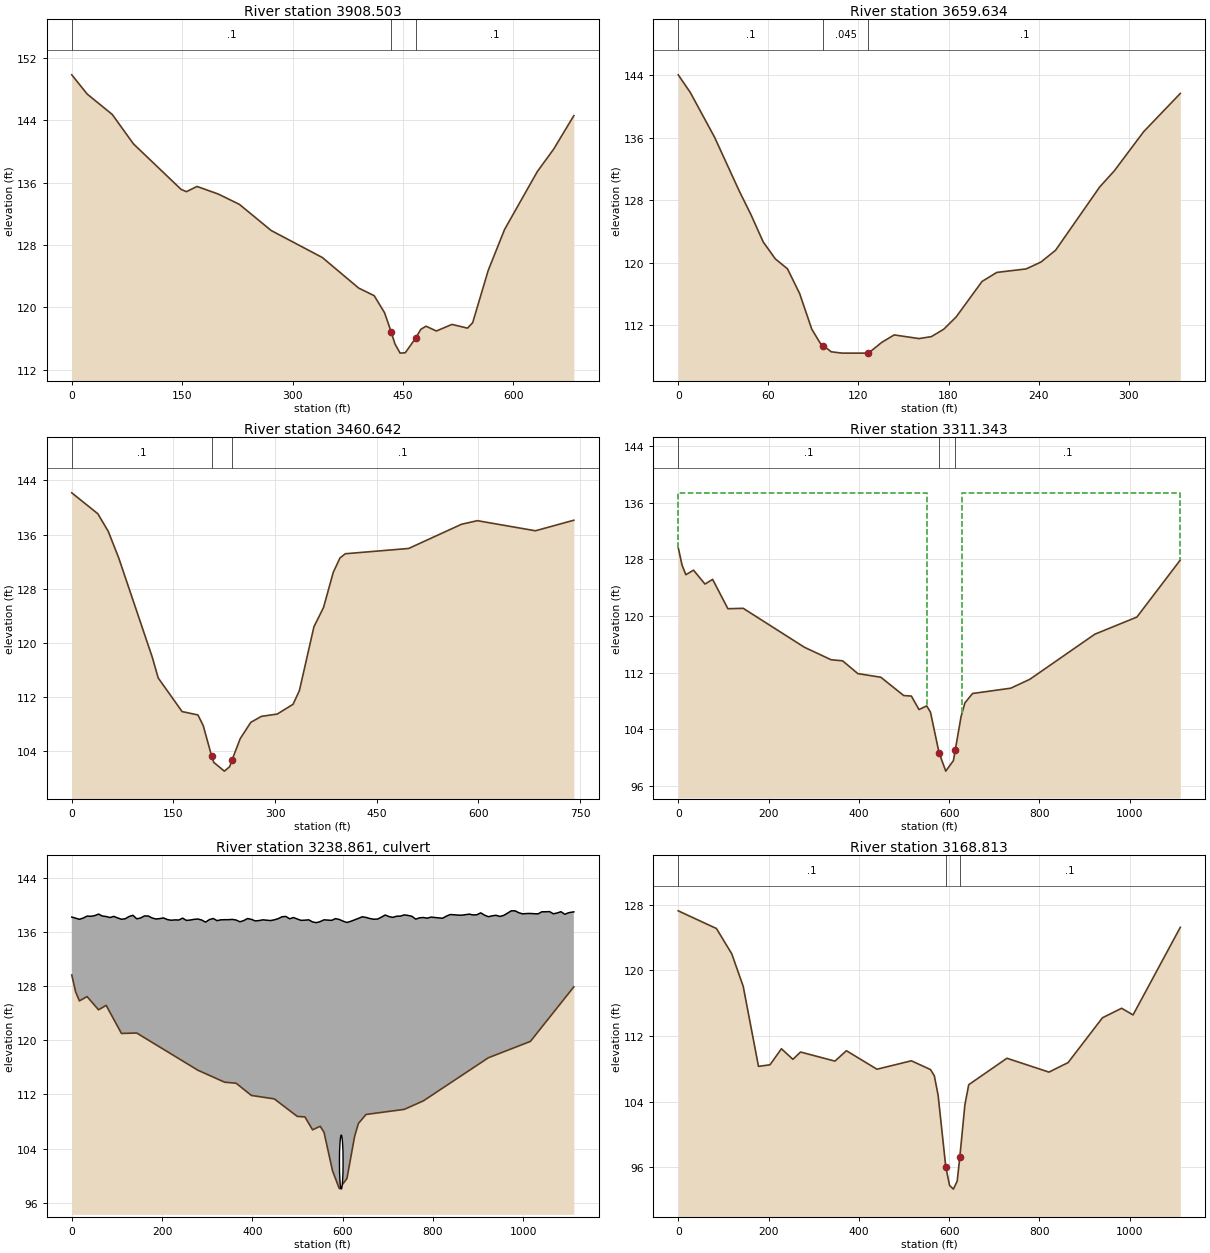
Type RM Length L Ch R = 1 ,3908.503,286.86,248.87,184.04
XS GIS Cut Line= 5
1627990.06776641721698.7350982131627992.71348347721658.201284692
1627934.30089237 721414.537333191627902.41709585721126.856190816
1627868.80254874721031.015873164
#Sta/Elev= 30
       0  149.86   21.04  147.38   55.02  144.77   83.81  140.99   148.6  135.14
  155.79  134.85  170.19  135.52  198.98  134.55  227.78  133.22  270.97  129.86
  340.49  126.39  389.79  122.47  410.92  121.49     425   119.3  433.88  116.87
  439.09   115.3  446.13  114.11  453.17  114.16  467.26  116.04   474.3  117.17
  481.34  117.57  495.43  116.95  516.56   117.8  537.69  117.32  544.73  118.02
  565.86  124.74  588.05  129.99  632.56  137.43  654.81  140.32  682.19  144.62
#Mann= 3 , 0 , 0
       0      .1       0  433.88    .045       0  467.26      .1       0
Bank Sta=433.88,467.26
XS Rating Curve= 0 ,0
Exp/Cntr=0.3,0.1

Type RM Length L Ch R = 1 ,3659.634,197.63,198.99,195.73
XS GIS Cut Line= 5
1628216.85917193721210.8067116141628135.03129029721163.553991258
1628103.91364521721153.1814428721628048.59338722721118.606281653
  1627949.477925721017.185808659
#Sta/Elev= 30
       0  144.04    8.08  141.77   24.25  136.04   40.42  129.27    48.5  126.13
   56.58  122.67   64.67   120.5   72.75  119.23   80.83  116.08   88.92  111.52
   94.49  109.74   96.66  109.41  101.87  108.62  109.25  108.45  126.68  108.45
  135.55  109.83   143.8  110.78  160.31  110.31  168.57  110.56  176.82  111.51
  185.08  113.08  202.32  117.62   212.1  118.77  231.68  119.22  241.47  120.09
  251.25   121.6  280.62  129.69  290.41  131.77  309.98  136.78  334.34  141.66
#Mann= 3 , 0 , 0
       0      .1       0   96.66    .045       0  126.68      .1       0
Bank Sta=96.66,126.68
XS Rating Curve= 0 ,0
Exp/Cntr=0.3,0.1

Type RM Length L Ch R = 1 ,3460.642,136.67,149.3,154.75
XS GIS Cut Line= 6
1628360.92234376721125.5213138761628329.80469866721057.523496807
1628272.17942992721013.7282925251628102.76113983720930.747905567
1628043.98336571720919.2228518131627734.13171196 720767.57411404
#Sta/Elev= 30
       0  142.17   38.49  139.08   53.89  136.47   69.28  132.56  118.74  117.92
  127.53  114.85  162.75  109.89  186.13  109.39  193.93  107.82   206.2  103.37
  209.51  102.39   225.1   101.1   232.9  101.75  236.42  102.75  248.49  105.89
  264.08   108.3  279.67  109.18  303.05  109.52  326.43  110.96  335.81  112.98
  357.21  122.39  371.47  125.27  385.74  130.43   395.7  132.56   403.5  133.18
  497.02  133.96  574.95  137.53  598.33  138.06  684.06  136.57  740.68  138.13
#Mann= 3 , 0 , 0
       0      .1       0   206.2    .045       0  236.42      .1       0
Bank Sta=206.2,236.42
XS Rating Curve= 0 ,0
Exp/Cntr=0.5,0.3

Type RM Length L Ch R = 1 ,3311.343,152.62,142.53,141.93
XS GIS Cut Line= 2
1628737.52613255721173.5915321261627817.97035679720547.914406374
#Sta/Elev= 30
       0  129.66    8.47  127.18   16.93  125.83   33.87  126.47   59.27  124.51
    76.2  125.17  110.07  121.02  143.93  121.08   279.4  115.58  338.67  113.81
  364.07  113.66  397.94  111.85  448.74  111.34  499.54  108.75  516.47  108.68
   533.4  106.77  550.34  107.29   558.8   106.4  577.69   100.7  592.67   98.07
   609.6   99.56  613.84  101.11  626.54  105.78     635  107.71  651.94  109.04
   736.6  109.79  778.94  111.05  922.87  117.42    1016  119.84 1112.23  127.91
#Mann= 3 , 0 , 0
       0      .1       0  577.69    .045       0  613.84      .1       0
#XS Ineff= 2 , 0
       0     551   137.4     629       0   137.4
Permanent Ineff=
       F       F
Bank Sta=577.69,613.84
XS Rating Curve= 0 ,0
Exp/Cntr=0.5,0.3

Type RM Length L Ch R = 2 ,3238.861,,,
BEGIN DESCRIPTION:
Un-named railroad, inspection crews could not access
Based on width of channel from DEM, an 8-ft diameter circular culver was assumed.  Based on comparisons with culverts on other streams with similar 100-yr discharges, this culvert size should be conservatively small.  The resulting stage upstream of this culvert appears to confirm this.  It does not appear that this conservative assumption (for stage) impacts any structures upstream.
Top of road obtained from DEM.
END DESCRIPTION:
Bridge Culvert--1,0,-1,-1, 0
Deck Dist Width WeirC Skew NumUp NumDn MinLoCord MaxHiCord MaxSubmerge Is_Ogee
61,20,2.6,0, 132, 132, , , 0.95, 0, 1.5,1.5,,
       0    8.47   16.93    25.4   33.87   42.33    50.8   59.27   67.73    76.2
   84.67   93.13   101.6  110.07  118.53     127  135.47  143.93   152.4  160.87
  169.33   177.8  186.27  194.73   203.2  211.67  220.13   228.6  237.07  245.53
     254  262.47  270.93   279.4  287.87  296.33   304.8  313.27  321.73   330.2
  338.67  347.13   355.6  364.07  372.54     381  389.47  397.94   406.4  414.87
  423.34   431.8  440.27  448.74   457.2  465.67  474.14   482.6  491.07  499.54
     508  516.47  524.94   533.4  541.87  550.34   558.8  567.27  575.74   584.2
  592.67  601.14   609.6  618.07  626.54     635  643.47  651.94   660.4  668.87
  677.34   685.8  694.27  702.74   711.2  719.67  728.14   736.6  745.07  753.54
     762  770.47  778.94   787.4  795.87  804.34   812.8  821.27  829.74   838.2
  846.67  855.14   863.6  872.07  880.54     889  897.47  905.94   914.4  922.87
  931.34   939.8  948.27  956.74   965.2  973.67  982.14   990.6  999.07 1007.54
    1016 1024.47 1032.94  1041.4 1049.87 1058.34  1066.8 1075.27 1083.74  1092.2
 1100.67 1112.23
  138.23  138.07   137.9  138.08  138.37  138.34  138.44  138.67  138.38  138.31
  138.16  138.33   138.1   137.9  137.98  138.31  138.49  137.97  138.09  138.39
  138.39   138.1  137.94     138   138.1  137.86  137.76  137.81  137.79  138.07
  137.73  137.79  137.89  137.94  137.79  137.48  137.85  138.02   137.7  137.82
  137.84  137.84  137.88  137.79  137.53  137.71  138.01  137.89  137.66  137.71
  137.82  137.77  137.71  137.82  137.99  138.27  138.32  137.97  138.16  137.94
  137.74  137.77  137.82  137.51   137.4  137.56  137.82  137.78  137.74     138
  137.87  137.62  137.43   137.6  137.81  138.03  138.27  138.17  138.01  137.91
  137.93  138.21  138.53   138.3  138.18  138.35  138.37  138.55  138.47  138.34
  137.92  138.12  138.16  138.06  138.22  138.16  138.09  138.05  138.36   138.6
  138.57  138.52   138.5  138.58  138.66  138.54  138.57  138.85  138.51  138.28
  138.41  138.49  138.32  138.47   138.8  139.15  139.15  138.86   138.7  138.75
  138.76  138.72   138.7  139.01  139.01  139.04  138.71  138.83  139.02  138.64
  138.87     139
                                                                                
                                                                                
                                                                                
                                                                                
                                                                                
                                                                                
                                                                                
                                                                                
                                                                                
                                                                                
                                                                                
                                                                                
                                                                                
                
       0    8.47   16.93    25.4   33.87   42.33    50.8   59.27   67.73    76.2
   84.67   93.13   101.6  110.07  118.53     127  135.47  143.93   152.4  160.87
  169.33   177.8  186.27  194.73   203.2  211.67  220.13   228.6  237.07  245.53
     254  262.47  270.93   279.4  287.87  296.33   304.8  313.27  321.73   330.2
  338.67  347.13   355.6  364.07  372.54     381  389.47  397.94   406.4  414.87
  423.34   431.8  440.27  448.74   457.2  465.67  474.14   482.6  491.07  499.54
     508  516.47  524.94   533.4  541.87  550.34   558.8  567.27  575.74   584.2
  592.67  601.14   609.6  618.07  626.54     635  643.47  651.94   660.4  668.87
  677.34   685.8  694.27  702.74   711.2  719.67  728.14   736.6  745.07  753.54
     762  770.47  778.94   787.4  795.87  804.34   812.8  821.27  829.74   838.2
  846.67  855.14   863.6  872.07  880.54     889  897.47  905.94   914.4  922.87
  931.34   939.8  948.27  956.74   965.2  973.67  982.14   990.6  999.07 1007.54
    1016 1024.47 1032.94  1041.4 1049.87 1058.34  1066.8 1075.27 1083.74  1092.2
 1100.67 1112.23
  138.23  138.07   137.9  138.08  138.37  138.34  138.44  138.67  138.38  138.31
  138.16  138.33   138.1   137.9  137.98  138.31  138.49  137.97  138.09  138.39
  138.39   138.1  137.94     138   138.1  137.86  137.76  137.81  137.79  138.07
  137.73  137.79  137.89  137.94  137.79  137.48  137.85  138.02   137.7  137.82
  137.84  137.84  137.88  137.79  137.53  137.71  138.01  137.89  137.66  137.71
  137.82  137.77  137.71  137.82  137.99  138.27  138.32  137.97  138.16  137.94
  137.74  137.77  137.82  137.51   137.4  137.56  137.82  137.78  137.74     138
  137.87  137.62  137.43   137.6  137.81  138.03  138.27  138.17  138.01  137.91
  137.93  138.21  138.53   138.3  138.18  138.35  138.37  138.55  138.47  138.34
  137.92  138.12  138.16  138.06  138.22  138.16  138.09  138.05  138.36   138.6
  138.57  138.52   138.5  138.58  138.66  138.54  138.57  138.85  138.51  138.28
  138.41  138.49  138.32  138.47   138.8  139.15  139.15  138.86   138.7  138.75
  138.76  138.72   138.7  139.01  139.01  139.04  138.71  138.83  139.02  138.64
  138.87     139
                                                                                
                                                                                
                                                                                
                                                                                
                                                                                
                                                                                
                                                                                
                                                                                
                                                                                
                                                                                
                                                                                
                                                                                
                                                                                
                
BR Coef=-1 , 0 , 0 ,, 0 ,,,0.8,0,,0,
WSPro=,,,, 1 ,,,, 0 ,,,, 0 ,,,,-1 ,-1 ,-1 , 0 , 0 , 0 , 0 , 0
Culvert=1,8,,126.5,0.015,0.5,1,1,1,98,597,93,608,Culvert #1  , 0 ,8
Culvert Bottom n=0.015
BC Design=,, 0 ,, 0 ,,,,,,
BC Use User HTab Curves=0
BC User HTab FreeFlow(D)= 0

Type RM Length L Ch R = 1 ,3168.813,331.63,357.82,385.2
XS GIS Cut Line= 2
1628816.28217117721057.8440208141627896.72639546720432.166895032
#Sta/Elev= 30
       0  127.28   84.67  125.12  118.53  122.04  143.93  118.07   177.8   108.3
   203.2  108.49   228.6  110.45     254  109.16  270.93  110.05  347.13  108.94
  372.54  110.21  440.27  107.95  516.47  108.98   558.8  107.91  567.27  107.16
  575.74  104.77  592.67   96.04  601.14   93.77   609.6   93.32  618.07   94.32
  623.85   97.27     635  103.59  643.47  106.06  728.14  109.29  821.27   107.6
   863.6  108.76   939.8  114.23  982.14  115.39 1007.54  114.58 1112.23  125.27
#Mann= 3 , 0 , 0
       0      .1       0  592.67    .045       0  623.85      .1       0
Bank Sta=592.67,623.85
XS Rating Curve= 0 ,0
Exp/Cntr=0.5,0.3

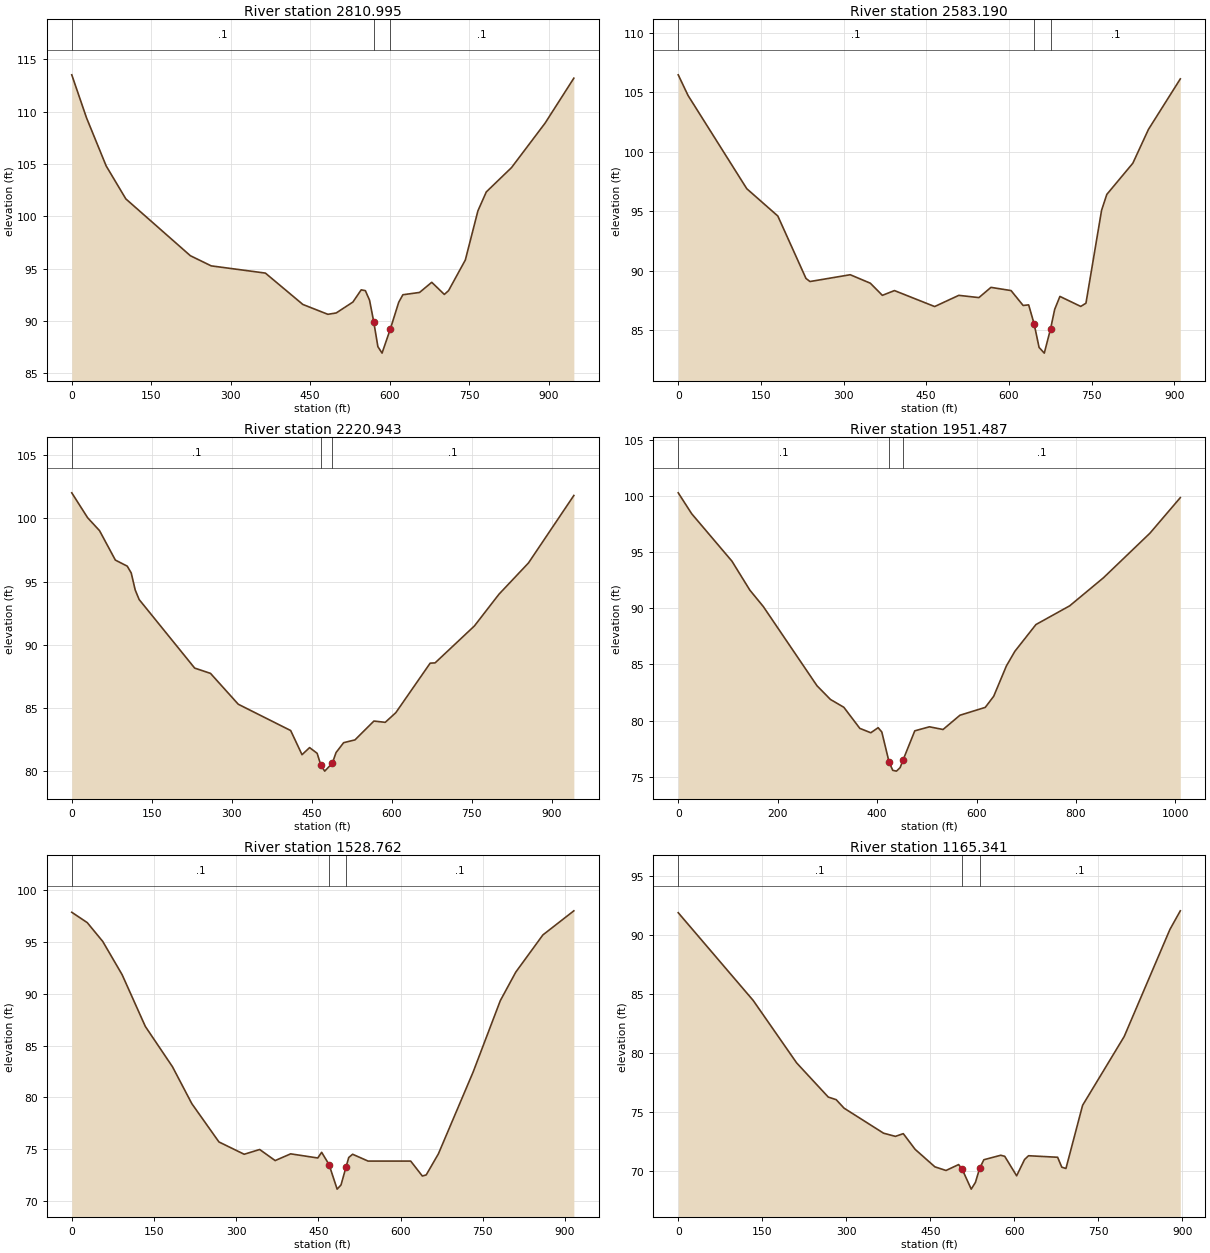
Type RM Length L Ch R = 1 ,2810.995,231.01,227.8,222.01
XS GIS Cut Line= 4
1628757.94423896720949.8185385761628618.74464183720828.624834135
1628392.96591556720388.1311188491628267.35649259720151.132207587
#Sta/Elev= 30
       0  113.52   27.84  109.41   64.97  104.81  102.09  101.66   223.9   96.23
  263.23   95.26  365.48   94.57  436.28   91.57  483.47   90.63   499.2   90.76
  530.67    91.8   546.4   92.97  554.26   92.89  562.13   91.98     570   89.93
  577.86   87.54  585.73   86.92  601.46   89.24  617.19   91.78  625.06    92.5
  656.52   92.72  679.55   93.69  703.32   92.53  711.24   92.89  742.93   95.82
   766.7  100.52  782.54  102.33  830.08  104.65  893.46   108.9  947.78   113.2
#Mann= 3 , 0 , 0
       0      .1       0     570     .05       0  601.46      .1       0
#XS Ineff= 1 ,-1
  416.37  545.37      92
Permanent Ineff=
       T
Bank Sta=570,601.46
XS Rating Curve= 0 ,0
Exp/Cntr=0.3,0.1

Type RM Length L Ch R = 1 ,2583.190,295.65,362.25,331.12
XS GIS Cut Line= 4
1628836.15387969720919.0086801051628756.33860889720816.874126673
1628613.37490307720331.2513801311628428.51575229720127.432316437
#Sta/Elev= 30
       0  106.46   17.77  104.73  124.38    96.9   180.7   94.61  231.78   89.37
  239.08   89.11  312.05   89.68  348.53   88.97  370.42   87.95  392.32   88.35
  465.29   87.01  509.07   87.95  545.55   87.76  567.44   88.62  603.93   88.35
  625.82    87.1  635.85   87.15  645.73   85.56  654.75   83.58   664.2    83.1
   675.7   85.16   683.1   86.78  692.55   87.86  730.35   87.02   739.8   87.29
  768.16   95.09  777.61   96.42  824.86   99.04  853.21  101.88  911.01  106.12
#Mann= 3 , 0 , 0
       0      .1       0  645.73     .05       0   675.7      .1       0
#XS Ineff= 1 ,-1
   353.2  572.06    88.5
Permanent Ineff=
       T
Bank Sta=645.73,675.7
XS Rating Curve= 0 ,0
Exp/Cntr=0.3,0.1

Type RM Length L Ch R = 1 ,2220.943,317.06,269.45,199.08
XS GIS Cut Line= 4
1628992.57316114720814.7291591321628866.96373811720461.600781336
1628831.41390143720241.1917938591628570.71509902720018.412817255
#Sta/Elev= 30
       0  102.02   29.72  100.05   52.01   99.03   81.73    96.7  104.02   96.22
  111.44   95.68  118.87   94.34   126.3   93.58  230.32   88.16  260.04   87.74
  312.05    85.3  410.26   83.22  431.53   81.31  445.71   81.87  459.89   81.42
  466.98   80.46  474.07   80.01  488.25   80.63  495.34   81.48  509.52   82.26
  530.79   82.48  566.25   83.97  587.52   83.87  607.27   84.63  671.72   88.55
  680.93   88.57  754.59   91.49  800.63      94  855.88   96.47  940.98  101.81
#Mann= 3 , 0 , 0
       0      .1       0  466.98     .05       0  488.25      .1       0
Bank Sta=466.98,488.25
XS Rating Curve= 0 ,0
Exp/Cntr=0.3,0.1

Type RM Length L Ch R = 1 ,1951.487,387.8,422.73,361.31
XS GIS Cut Line= 4
1629397.84129938720587.2102043331629177.43231192720314.661456347
1629004.42310666720257.7817176431628611.00491399719987.602958798
#Sta/Elev= 30
       0  100.29   27.01   98.43  108.03    94.2  144.04   91.62  171.05   90.16
  279.08    83.1  306.09   81.88  333.09   81.18  365.26    79.3  387.36   78.91
   402.1   79.36  409.47   78.98   424.2   76.28  431.57   75.56  438.94   75.49
  446.31    75.8  452.03   76.46  475.78   79.08  505.26   79.44  532.64    79.2
   566.6   80.47  617.55   81.17  634.54   82.16  660.01   84.86     677   86.16
  719.45   88.55  787.39   90.22  855.32   92.72  948.73   96.69 1009.89   99.86
#Mann= 3 , 0 , 0
       0      .1       0   424.2     .05       0  452.03      .1       0
Bank Sta=424.2,452.03
XS Rating Curve= 0 ,0
Exp/Cntr=0.3,0.1

Type RM Length L Ch R = 1 ,1528.762,334.26,363.42,264.58
XS GIS Cut Line= 4
1629606.40034132719980.4929914621629322.77296148719941.531404451
1628957.69476826719892.0937324461628698.69451113719925.983241856
#Sta/Elev= 30
       0   97.89   28.26   96.89   56.53   95.07   91.85   91.86  134.25   86.85
  183.71   82.96  219.04   79.39   268.5   75.69  314.55    74.5   342.8   74.96
  371.06   73.89  399.31   74.54  448.76   74.14  455.82   74.69  469.31   73.51
  484.08   71.13  491.14   71.53  500.36   73.27  505.27   74.19  512.34    74.5
  540.59   73.84  618.29   73.84  639.49    72.4  646.55    72.5  668.82   74.54
  732.36   82.47  781.78   89.35  810.02   92.11  859.43    95.7  915.91   98.03
#Mann= 3 , 0 , 0
       0      .1       0  469.31     .05       0  500.36      .1       0
Bank Sta=469.31,500.36
XS Rating Curve= 0 ,0
Exp/Cntr=0.3,0.1

Type RM Length L Ch R = 1 ,1165.341,256.1,326.05,290.53
XS GIS Cut Line= 5
1629604.03035218719653.4344939141629144.25246434719598.924744308
1629058.93285629719632.1045919061628952.28334618719648.694515675
1628731.87435871719726.904156402
#Sta/Elev= 30
       0    91.9  133.93   84.46  211.47   79.17  267.86   76.28  281.96   76.06
  296.06   75.34  366.55   73.22   387.7   72.95  401.79   73.18  422.94   71.85
  458.19   70.37  478.02   70.06  500.55   70.56  506.79   70.18  523.08   68.48
  530.59   69.05   538.1   70.24  545.62   70.97  575.79   71.35  582.88   71.26
  604.13   69.61   618.3   70.99  625.38   71.31  677.33   71.18  684.76   70.34
  692.18   70.23  721.89   75.58  796.17   81.41  877.87   90.49  896.35   92.06
#Mann= 3 , 0 , 0
       0      .1       0  506.79     .05       0   538.1      .1       0
Bank Sta=506.79,538.1
XS Rating Curve= 0 ,0
Exp/Cntr=0.3,0.1

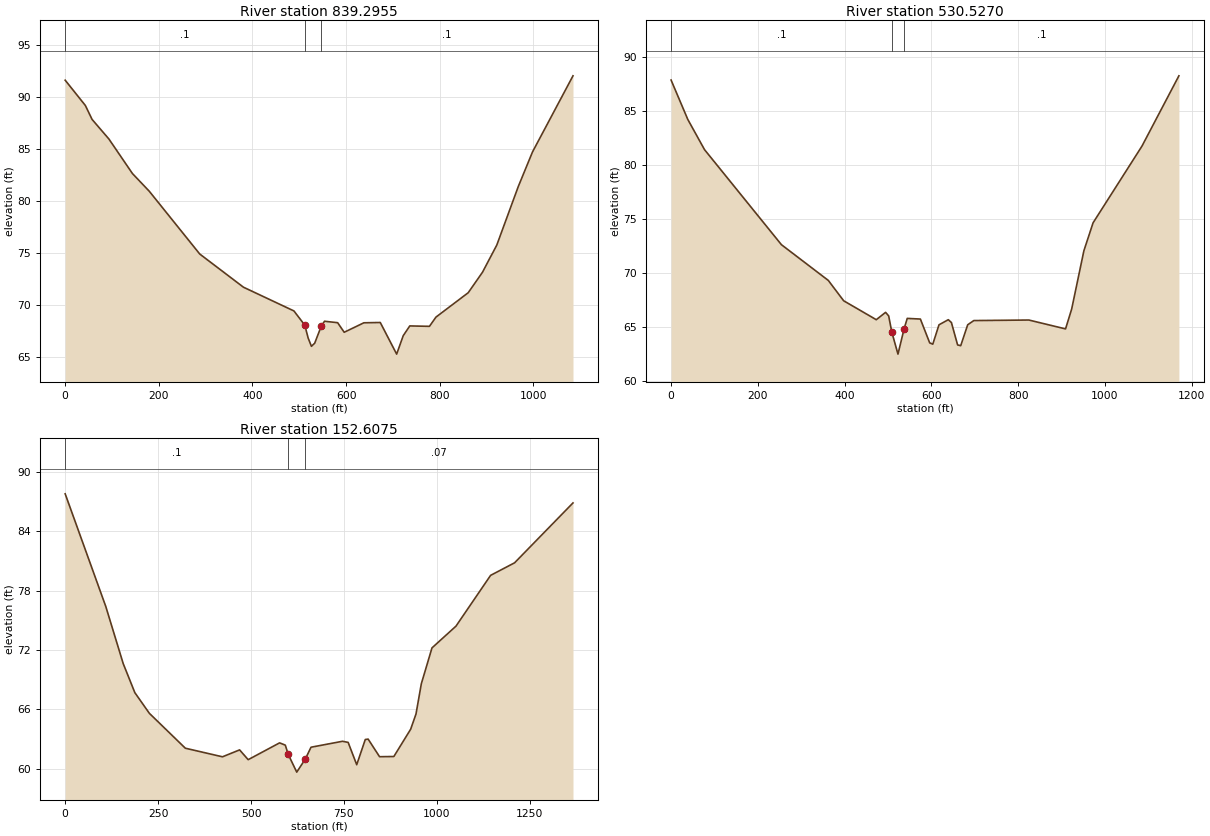
Type RM Length L Ch R = 1 ,839.2955,291.15,308.77,291.86
XS GIS Cut Line= 4
1629618.25028683719463.8353648781629126.31851332719350.452070132
1628808.65933587719357.4081104841628568.34510992719461.465375766
#Sta/Elev= 30
       0   91.61    43.1   89.18   57.47   87.84   93.39   85.96  143.67   82.64
  179.59   80.94  287.34   74.91  380.73   71.72  488.48   69.44  511.75   68.07
  518.83   66.84  525.83   66.04  532.84   66.34  546.84   67.97  553.84   68.45
  581.85   68.31  595.85   67.39  637.86    68.3  672.87   68.33  707.88   65.29
  721.88   67.06  735.88      68  777.89   67.96   791.9   68.85   860.7   71.19
  891.22   73.16  921.73   75.77   967.5   81.38  998.01   84.72 1084.44   92.03
#Mann= 3 , 0 , 0
       0      .1       0  511.75     .05       0  546.84      .1       0
Bank Sta=511.75,546.84
XS Rating Curve= 0 ,0
Exp/Cntr=0.3,0.1

Type RM Length L Ch R = 1 ,530.5270,311.94,377.92,373.94
XS GIS Cut Line= 6
1629611.14031951719222.0964753931629307.78171308719082.267117724
1629184.54227926719063.3072048281629077.89276919719084.637106851
1628964.13329175719060.9372157311628480.65551277719117.816954434
#Sta/Elev= 30
       0   87.83   38.54   84.19   77.08    81.4  254.36   72.62  362.36   69.32
  397.78   67.44     473   65.69  494.42   66.37  501.56   66.04  508.69   64.56
  522.97   62.51  537.25   64.87  544.39   65.81  574.64   65.75  596.09   63.55
  603.24   63.43  617.54   65.22  638.99   65.69  646.14   65.43  660.44   63.36
  667.59   63.29  683.69   65.22  697.78   65.61  824.65   65.66  909.23   64.84
  923.33   66.67  951.52   72.06  972.67   74.64 1085.44   81.73  1170.5   88.22
#Mann= 3 , 0 , 0
       0      .1       0  508.69     .05       0  537.25      .1       0
Bank Sta=508.69,537.25
XS Rating Curve= 0 ,0
Exp/Cntr=0.3,0.1

Type RM Length L Ch R = 1 ,152.6075,109.27,152.61,179.08
XS GIS Cut Line= 4
1629663.28007999719018.2774116991629428.65115786718902.147945181
1628853.08152552718641.4966456741628391.66418014718743.518571287
#Sta/Elev= 30
       0    87.8  109.35   76.39  156.21   70.61  187.45   67.68   226.5   65.59
  323.27   62.06  423.17   61.19  469.27   61.89  492.33    60.9  576.85    62.6
  592.22   62.37  599.91   61.45  622.96   59.64  646.01   60.96  661.38   62.16
  745.91   62.76  761.28   62.65  784.33   60.39  807.38   62.94  815.07   62.98
   845.8    61.2  884.23   61.22  929.48   63.98  943.82   65.52  958.15   68.58
  986.83   72.21 1051.35   74.41 1144.55   79.55 1209.07   80.82 1366.19   86.88
#Mann= 3 , 0 , 0
       0      .1       0  599.91     .05       0  646.01     .07       0
Bank Sta=599.91,646.01
XS Rating Curve= 0 ,0
Exp/Cntr=0.3,0.1

Chan Stop Cuts=-1
Use User Specified Reach Order=0
User Specified Reach Order=EastBrachLaurel ,Reach1