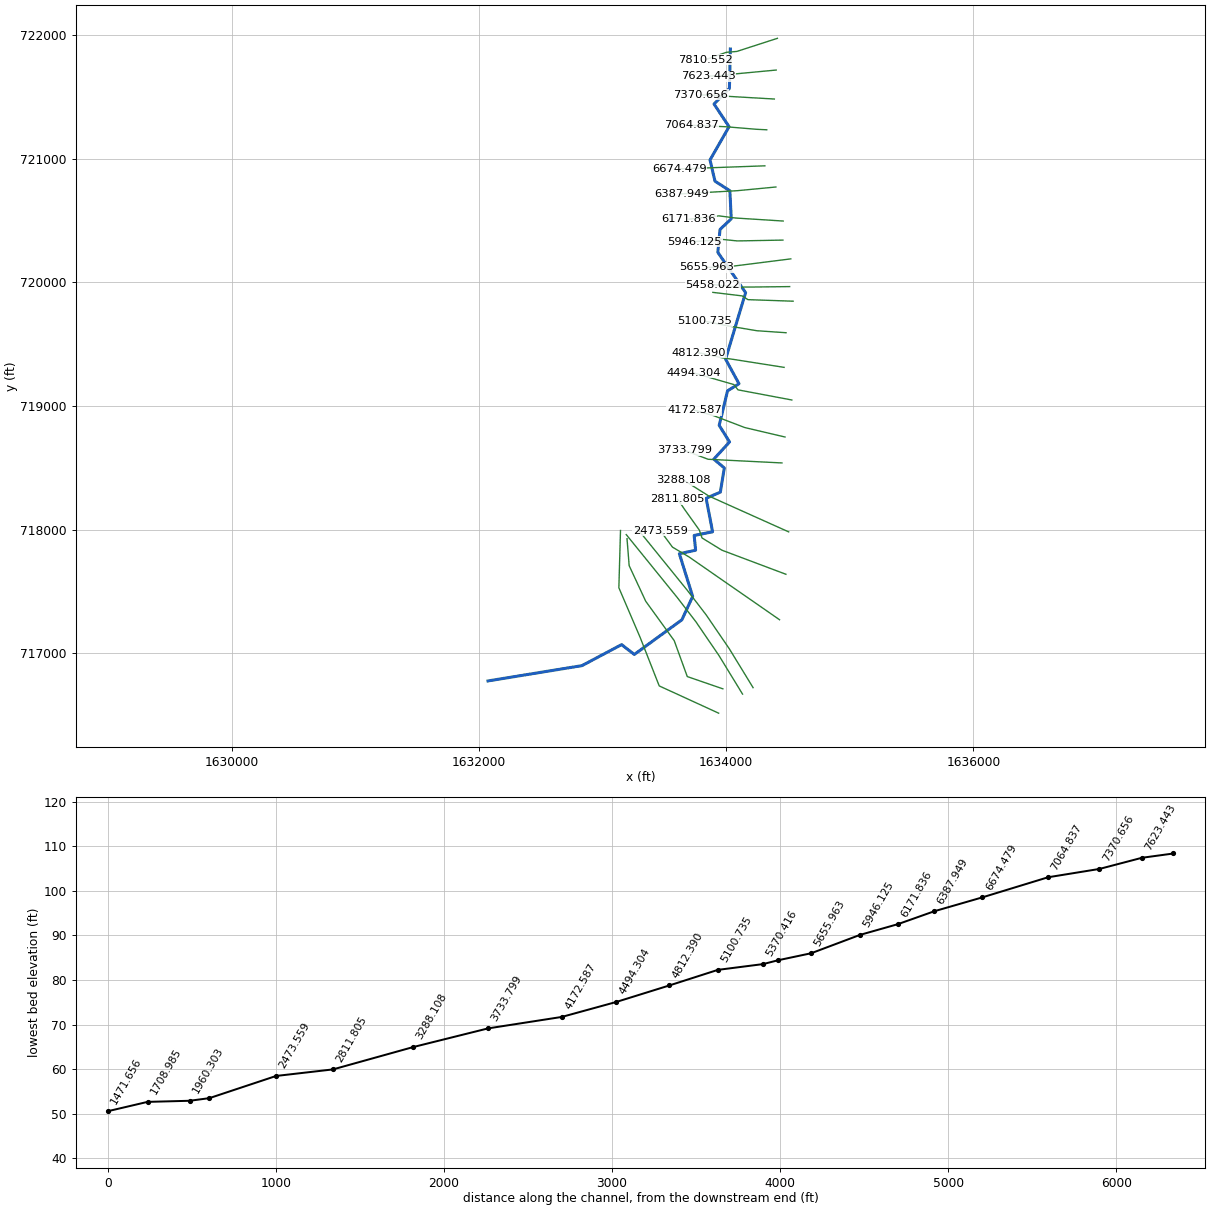
--- GravellyRun.prj (project) ---

Proj Title=Gravelly Run
Current Plan=p01
Default Exp/Contr=0.3,0.1
English Units
Geom File=g01
Flow File=f01
Flow File=f02
Plan File=p01
Plan File=p02
Y Axis Title=Elevation
X Axis Title(PF)=Main Channel Distance
X Axis Title(XS)=Station
BEGIN DESCRIPTION:
Gravelly Run - Georeferenced HEC-RAS model.  This was formerly an approximate method stream.  Projection:  MD Stateplane.  Horizontal datum:  NAD83.  Vertrial datum: NAVD88.  Units:Feet.  Created by: Aaron W. Buesing, USACE- St Paul District as part of FEMA Map Modernization study for Cecil County, MD.
NOTE - a portion of this model was changed to a Detailed Stream by LOMR 06-03-B926P.  The portion of the stream from Blue Ball Road (just downstream of the road) to the confluence with Little Elk Creek is now a detailed stream.
END DESCRIPTION:
DSS File=dss
DSS Export Rating Curves= 0
DSS Export Rating Curve Sorted= 0
DSS Export Volume Flow Curves= 0
DXF OffsetX= 0
DXF OffsetY= 0
DXF ScaleX= 1
DXF ScaleY= 10

--- GravellyRun.p01 (plan) ---

Plan Title=Gravelly Run Frequency Profiles
Program Version=4.00
Short Identifier=frequency
Geom File=g01
Flow File=f01
Subcritical Flow
K Sum by GR= 0
Std Step Tol= 0.01
Critical Tol= 0.01
Num of Std Step Trials= 20
Max Error Tol= 0.3
Flow Tol Ratio= 0.001
Split Flow NTrial= 30
Split Flow Tol= 0.02
Split Flow Ratio= 0.02
Log Output Level= 0
Friction Slope Method= 1
Unsteady Friction Slope Method= 2
Unsteady Bridges Friction Slope Method= 1
Secant Critical Depth
Global Vel Dist= 0 , 0 , 0
Global Log Level= 0
CheckData=True
Encroach Param=-1 ,0,0, 0
Computation Interval=1HOUR
Output Interval=1HOUR
Run HTab= 0
Run UNet= 0
Run PostProcess= 0
Run WQNet= 0
UNET Theta= 1
UNET Theta Warmup= 1
UNET ZTol= 0.02
UNET ZSATol= 0.05
UNET MxIter= 20
UNET MaxInSteps= 0
UNET DtIC= 0
UNET DtMin= 0
UNET MaxCRTS= 20
UNET WFStab= 2
UNET SFStab= 1
UNET WFX= 1
UNET SFX= 1
UNET DSS MLevel= 4
UNET DZMax Abort= 100
UNET Convert EG Bridges= 0
UNET Use Existing IB Tables=-1
UNET Froude Reduction=False
UNET Froude Limit= 1
UNET Froude Power= 10
UNET Time Slicing=0,0, 5
Instantaneous Interval=1HOUR
Write IC File= 0
Echo Input=False
Echo Output=False
Write Detailed= 0
Detailed Automatic Start=False, 10
WQ ULTIMATE=-1
WQ Max Comp Step=1HOUR
WQ Output Interval=15MIN
WQ Output Selected Increments= 0
WQ Output face flow=0
WQ Output face velocity=0
WQ Output face area=0
WQ Output face dispersion=0
WQ Output cell volume=0
WQ Output cell surface area=0
WQ Output cell continuity=0
WQ Output face conc=0
WQ Output face dconc_dx=0
WQ Output face courant=0
WQ Output face peclet=0
WQ Output face adv mass=0
WQ Output face disp mass=0
WQ Output cell mass=0
WQ Output cell source sink temp=0
WQ Output cell source sink nsm=0
WQ Output MaxMinRange=-1
WQ Daily Max Min Mean=-1
WQ Daily Range=0
WQ Daily Time=0
WQ Create Restart=0
WQ Fixed Restart=0
WQ System Summary=False
Sorting and Armoring Iterations= 10
XS Update Threshold= 0.02
Hydraulics Update Threshold= 0.02
Energy Slope Method= 1
Volume Change Method= 0
XS Weighting Method= 0
Number of US Weighted Cross Sections= 1
Number of DS Weighted Cross Sections= 1
Upstream XS Weight=0.25
Main XS Weight=0.5
Downstream XS Weight=0.25
Number of DS XS's Weighted with US Boundary= 1
Upstream Boundary Weight= 1
Weight of XSs Associated with US Boundary= 0
Number of US XS's Weighted with DS Boundary= 1
Downstream Boundary Weight= 0.5
Weight of XSs Associated with DS Boundary= 0.5
Sediment Output Level= 4
Mass or Volume Output= 0
Output Increment Type= 1
Profile and TS Output Increment= 10
XS Output Flag= 0
XS Output Increment= 10
Disregard all LS=0
Disregard all Conn=0
Disregard all Breaches=0
Disregard all Pumps=0

--- GravellyRun.p02 (plan) ---

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Plan Title=Gravelly Run Floodway
Short Identifier=Gravelly Run
Geom File=g01
Flow File=f02
Encroach Param=-1 ,0,0, 2
Encroach River=GravellyRun
Encroach Reach=Reach1
Encroach Node=1960.303
       1     790     840
Encroach Node=1708.985
       1     686     736
Encroach Node=1471.656
       1     871     922
Encroach Node=1081.175
       1     990    1040
Encroach Node=766.8887
       1    1070    1170
Encroach Node=488.0061
       1    1245    1355
Encroach Node=281.4444
       1    1045    1155
DSS File=dss

--- GravellyRun.f01 (steady flow) ---

Flow Title=Gravelly Run Frequency Flows
Program Version=4.00
Number of Profiles= 5
Profile Names=10yr,50yr,100yr-current,500yr,100yr-ultimate
River Rch & RM=GravellyRun,Reach1          ,7810.552
     253     564     770    1513    1012
River Rch & RM=GravellyRun,Reach1          ,5655.963
     272     625     862    1728    1081
River Rch & RM=GravellyRun,Reach1          ,2076.760
     305     729    1016    2073    1232
River Rch & RM=GravellyRun,Reach1          ,281.4444
     330     797    1111    2281    1316
Boundary for River Rch & Prof#=GravellyRun,Reach1          , 1
Up Type= 0
Dn Type= 3
Dn Slope=0.006
Boundary for River Rch & Prof#=GravellyRun,Reach1          , 2
Up Type= 0
Dn Type= 3
Dn Slope=0.006
Boundary for River Rch & Prof#=GravellyRun,Reach1          , 3
Up Type= 0
Dn Type= 3
Dn Slope=0.006
Boundary for River Rch & Prof#=GravellyRun,Reach1          , 4
Up Type= 0
Dn Type= 3
Dn Slope=0.006
Boundary for River Rch & Prof#=GravellyRun,Reach1          , 5
Up Type= 0
Dn Type= 3
Dn Slope=0.006
DSS Import GetInterval= 0
DSS Import GetPeak= 0
DSS Import FillOption= 0

--- GravellyRun.f02 (steady flow) ---

Flow Title=Gravelly Run Encroached Flows
Program Version=4.00
Number of Profiles= 2
Profile Names=100yr,100yr-enc
River Rch & RM=GravellyRun,Reach1          ,7810.552
     770     770
River Rch & RM=GravellyRun,Reach1          ,5655.963
     862     862
River Rch & RM=GravellyRun,Reach1          ,2076.760
    1016    1016
River Rch & RM=GravellyRun,Reach1          ,281.4444
    1111    1111
Boundary for River Rch & Prof#=GravellyRun,Reach1          , 1
Up Type= 0
Dn Type= 1
Dn Known WS=47.72
Boundary for River Rch & Prof#=GravellyRun,Reach1          , 2
Up Type= 0
Dn Type= 1
Dn Known WS=48.72
DSS Import GetInterval= 0
DSS Import GetPeak= 0
DSS Import FillOption= 0

--- GravellyRun.g01 (geometry) ---

Geom Title=Gravelly Run Geometry
Program Version=4.00
BEGIN GEOM DESCRIPTION:
Detailed Reach between 1960 and 122, LOMR used to lay out sections, XS cut from DEM, LOMR HEC-RAS used to cut channel in when necessary
END GEOM DESCRIPTION:

River Reach=GravellyRun     ,Reach1
Reach XY= 30
1634033.81429619721889.4390181451634026.20571555721570.833356097
1633901.61672589 721443.866746531634023.35270289721260.311995521
1633869.28050451720991.637007952 1633909.4664477720819.555003032
1634029.95833269720742.338622019 1634040.9891506720515.355480179
1633950.19602512720428.8051283661633932.37683496720243.824527204
1634157.23826194719917.5633686931633995.16837601719379.762278959
1634103.78069165719180.3568378841634011.29039104719123.504917458
1633943.40765283718843.9129569381634027.41273417718709.420443803
1633900.13247693718570.2606171371633984.98598173718498.983856782
1633952.74162364718303.3966495691633837.76233114718253.507007688
1633890.11970162717982.4812808631633740.77780879717952.782521397
 1633752.6573782717833.139059886 1633621.1343472717805.137475446
1633728.89823931717459.3599517791633641.49946402717270.136905044
1633256.43461734716989.7811665241633153.76192245717069.543146148
1632833.18579189716899.4122527991632072.22012219  716775.5263457

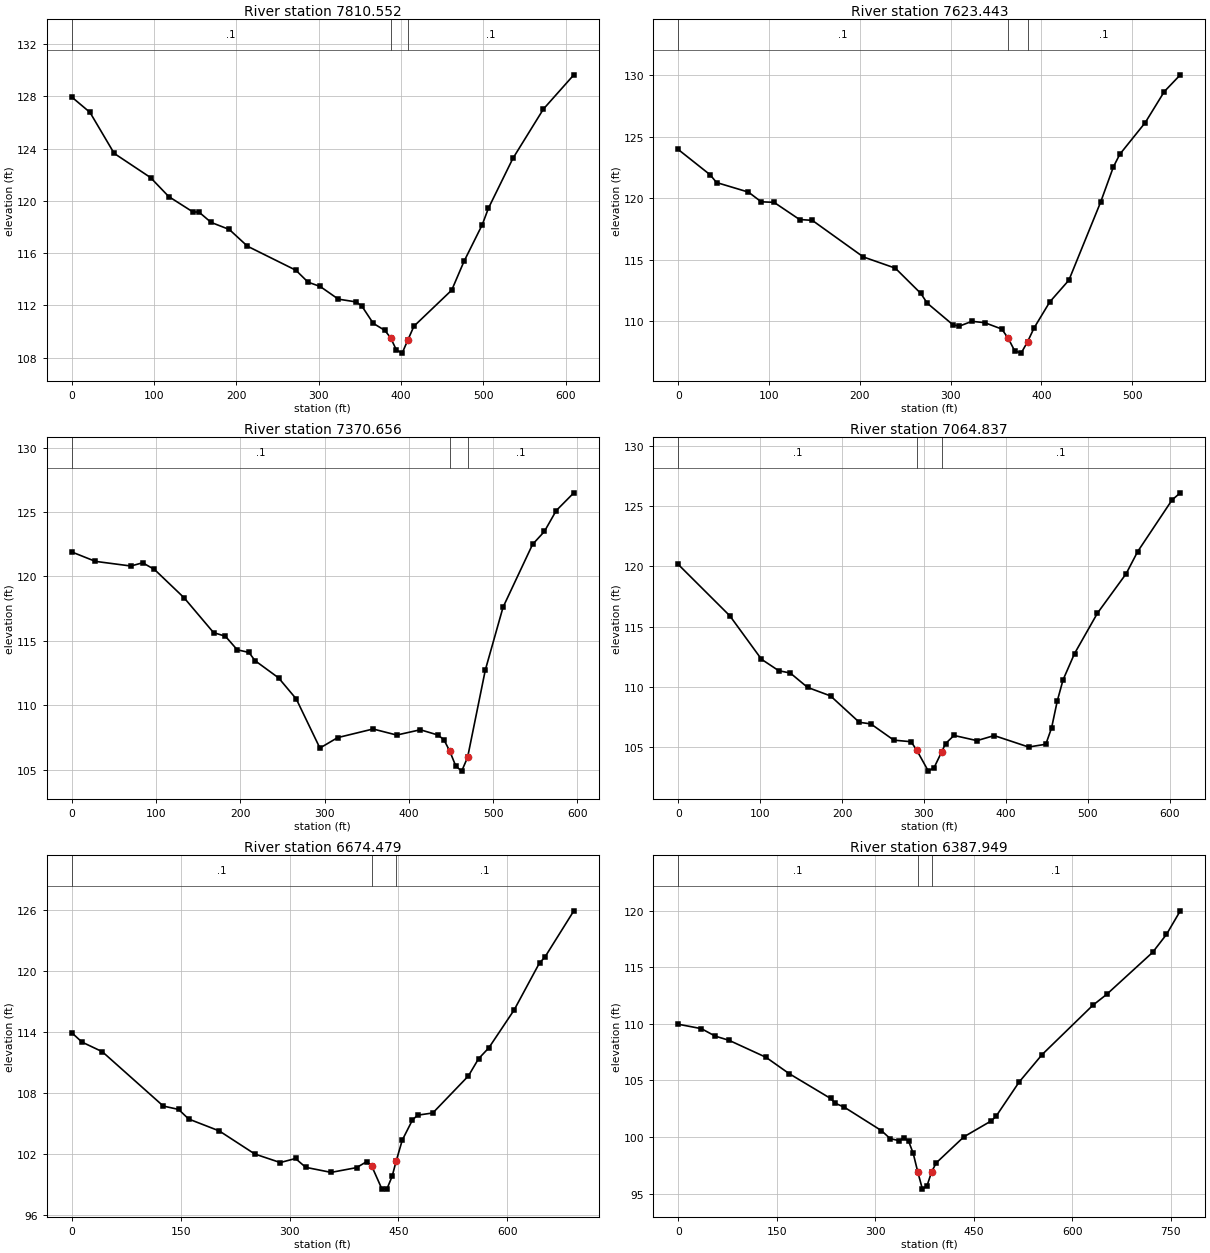
Type RM Length L Ch R = 1 ,7810.552,182.1,187.11,184.51
XS GIS Cut Line= 4
1634414.48971589721975.6744099561634086.19280027 721869.53354612
1633999.79894422721862.1283771841633831.94757387721802.886697784
#Sta/Elev= 30
       0  127.94   22.07  126.77    51.5  123.63   95.64  121.78  117.71  120.33
  147.14  119.15  154.49  119.14  169.21  118.35  191.28  117.81  213.35  116.53
   272.2  114.69  286.91  113.78  301.63  113.45   323.7  112.48  345.03  112.27
  352.05  111.97  366.11  110.63  380.16  110.09  387.18  109.53  394.21  108.59
  401.23  108.35  408.26  109.37  415.54  110.41  461.43  113.17  476.28  115.36
  498.55  118.18  505.97  119.43  535.66  123.24  572.78  127.02  609.74  129.64
#Mann= 3 , 0 , 0
       0      .1       0  387.18    .045       0  408.26      .1       0
Bank Sta=387.18,408.26
XS Rating Curve= 0 ,0
Exp/Cntr=0.3,0.1

Type RM Length L Ch R = 1 ,7623.443,184.84,252.79,215.83
XS GIS Cut Line= 4
1634404.61604795721718.9610126171634063.97729355721686.871837944
1634004.73561409721676.9981700331633854.16340874721669.593001097
#Sta/Elev= 30
       0  123.97   35.15  121.91   42.19  121.28   77.34   120.5    91.4  119.71
  105.46  119.67  133.59  118.27  147.65   118.2   203.9  115.22  239.05  114.31
  267.18  112.25  274.21  111.46  302.33  109.71  309.36  109.58  323.43  109.98
  337.49  109.87  356.34  109.35  363.44  108.59  370.53  107.58  377.63  107.39
  384.73  108.31  391.82  109.43  409.21  111.56  430.24  113.33  465.28   119.7
   479.3  122.56  486.31  123.58  514.34  126.16  535.37  128.69  552.96  130.05
#Mann= 3 , 0 , 0
       0      .1       0  363.44    .045       0  384.73      .1       0
Bank Sta=363.44,384.73
XS Rating Curve= 0 ,0
Exp/Cntr=0.3,0.1

Type RM Length L Ch R = 1 ,7370.656,248.46,305.82,269.44
XS GIS Cut Line= 2
1634389.80571014 721484.463122041633794.92172928721519.020795688
#Sta/Elev= 30
       0   121.9   28.05  121.17   70.12  120.81   84.14  121.06   98.17  120.54
  133.22  118.35  168.28  115.64  182.31  115.36  196.33  114.31  210.35   114.1
  217.37  113.47  245.41  112.13  266.45  110.49   294.5  106.68  315.53  107.49
   357.6  108.16  385.65  107.69   413.7   108.1  434.73  107.69  441.74  107.32
  448.76  106.42  455.77  105.28  462.78  104.89  469.79  105.96  490.83  112.74
  511.86  117.61  546.92  122.49  560.94  123.49  574.97  125.11  595.89  126.49
#Mann= 3 , 0 , 0
       0      .1       0  448.76    .045       0  469.79      .1       0
Bank Sta=448.76,469.79
XS Rating Curve= 0 ,0
Exp/Cntr=0.3,0.1

Type RM Length L Ch R = 1 ,7064.837,334.4,390.36,351.95
XS GIS Cut Line= 4
1634328.26777546 721235.576808781634247.77810708721239.400620013
1633992.54928678721260.5475593511633716.48323788721271.645634279
#Sta/Elev= 30
       0  120.17   63.07   115.9  101.65   112.3  122.72  111.35  136.77  111.16
  157.84  109.97  185.94  109.26  221.06  107.07  235.11  106.94   263.2  105.59
  284.28  105.46  291.16  104.76  305.35  103.02  312.37  103.31  321.57  104.61
  326.42  105.31  336.68  105.98  364.71  105.55  385.72  105.97  427.76  105.02
  448.77  105.25  455.78   106.6  462.79  108.85  469.79  110.59   483.8  112.77
  511.83  116.13  546.85   119.4  560.86  121.23   602.9  125.52  612.97  126.11
#Mann= 3 , 0 , 0
       0      .1       0  291.16    .045       0  321.57      .1       0
Bank Sta=291.16,321.57
XS Rating Curve= 0 ,0
Exp/Cntr=0.3,0.1

Type RM Length L Ch R = 1 ,6674.479,197.37,286.53,252.7
XS GIS Cut Line= 2
1634313.28552192720943.8838226051633622.13368906720919.199816853
#Sta/Elev= 30
       0  113.94   14.01  113.02   42.03  112.07  126.08  106.71  147.09  106.38
   161.1  105.43  203.13  104.26  252.16  101.98  287.18  101.14   308.2  101.54
  322.21  100.67  357.23  100.17  392.25  100.64  406.26  101.23  413.26  100.78
  427.27   98.52  434.28   98.57  441.28   99.78  446.91   101.3  455.29  103.36
   469.3  105.34   476.3  105.81  497.32  106.03  546.35  109.68  560.36  111.38
  574.37  112.44  609.39  116.19  644.41  120.84  651.41  121.36  691.59  125.96
#Mann= 3 , 0 , 0
       0      .1       0  413.26    .045       0  446.91      .1       0
Bank Sta=413.26,446.91
XS Rating Curve= 0 ,0
Exp/Cntr=0.3,0.1

Type RM Length L Ch R = 1 ,6387.949,216.45,216.11,204.68
XS GIS Cut Line= 3
1634402.32733862720772.6144801231634087.98380718720742.517755523
1633639.87741995720717.437097013
#Sta/Elev= 30
       0  109.97   35.16  109.58   56.26  108.92   77.35  108.55  133.61  107.05
  168.77  105.61  232.06  103.41  239.09  102.99  253.15  102.63  309.41  100.57
  322.79   99.86  336.81   99.68  343.82   99.95  350.84   99.63  357.85   98.56
  364.86    96.9  371.87    95.4  378.88    95.7  385.89   96.93   392.9   97.72
  434.97  100.02  477.03  101.44  484.04  101.84   519.1  104.86  554.15  107.29
  631.27  111.64  652.31   112.6  722.42  116.32  743.45   117.9  764.59  119.99
#Mann= 3 , 0 , 0
       0      .1       0  364.86    .045       0  385.89      .1       0
Bank Sta=364.86,385.89
XS Rating Curve= 0 ,0
Exp/Cntr=0.3,0.1

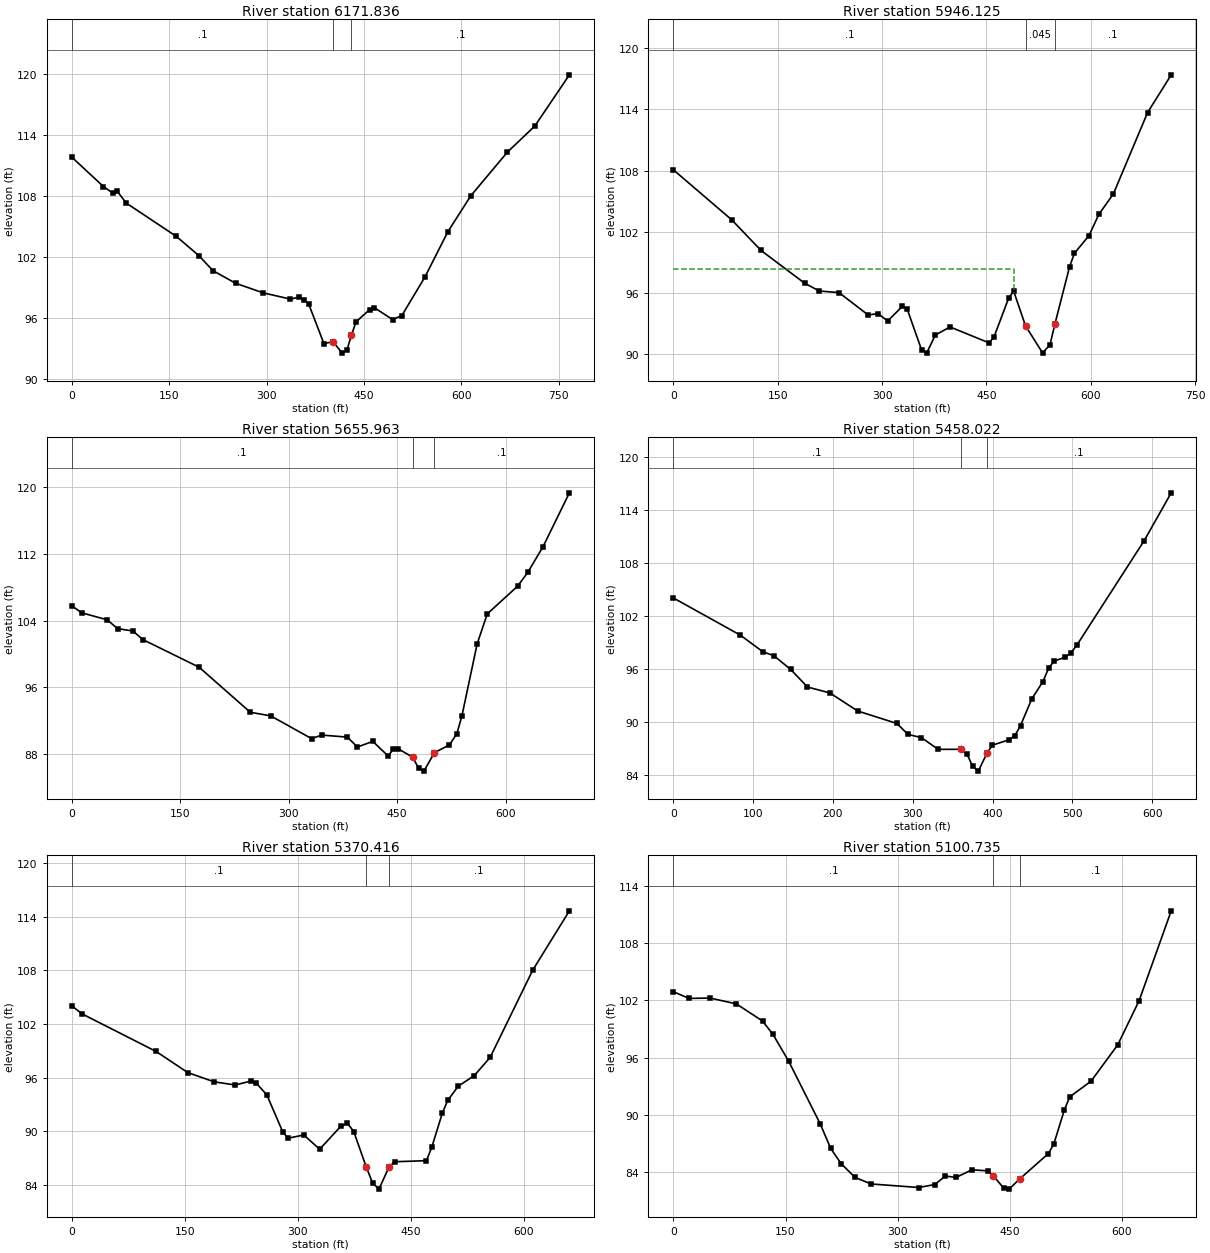
Type RM Length L Ch R = 1 ,6171.836,185.42,225.71,203.28
XS GIS Cut Line= 4
1634461.38922836720497.1035481841634073.85063334720521.787553936
1633940.55726478720539.0663907681633698.65420531720511.914214119
#Sta/Elev= 30
       0  111.86    49.1  108.94   63.13  108.31   70.14  108.49   84.17  107.31
  161.33  104.02   196.4   102.1  217.44  100.65  252.51    99.4   294.6   98.46
  336.68   97.84  350.71   98.04  357.72   97.77  364.74   97.39  388.32   93.45
  402.44   93.63  416.56   92.51  423.62   92.78  430.68   94.27  437.73   95.59
  458.91   96.81  465.97   96.99   494.2   95.82  508.32   96.22  543.86  100.02
  579.08  104.48   614.3  108.02  670.66  112.33  712.92  114.91  766.15  119.96
#Mann= 3 , 0 , 0
       0      .1       0  402.44    .045       0  430.68      .1       0
Bank Sta=402.44,430.68
XS Rating Curve= 0 ,0
Exp/Cntr=0.3,0.1

Type RM Length L Ch R = 1 ,5946.125,207.65,290.16,251.73
XS GIS Cut Line= 5
1634459.17663437720342.9004445231634089.65604793720336.212137684
 1633957.5647767720349.5884232671633919.10783261720342.900444523
1633745.21579197 720331.19607161
#Sta/Elev= 30
       0  108.08   84.01  103.17  126.02  100.17  189.03   96.94  210.03   96.19
  238.04   96.04  280.05   93.84  294.05   93.98  308.05   93.25  329.05   94.68
  336.06   94.43  357.06   90.37  364.06    90.1  376.62   91.88  397.72   92.67
  454.01    91.1  461.05   91.71  482.15   95.53  489.19   96.18  506.26   92.77
  530.77   90.12  541.38   90.92   548.4   92.94  569.45   98.55  576.46   99.89
  597.51  101.63  611.54   103.7  632.59  105.73   681.7   113.7  715.67   117.4
#Mann= 3 , 0 , 0
       0      .1       0  506.26    .045       0   548.4      .1       0
#XS Ineff= 2 , 0
          489.98   98.32
Permanent Ineff=
       F       F
Bank Sta=506.26,548.4
XS Rating Curve= 0 ,0
Exp/Cntr=0.3,0.1

Type RM Length L Ch R = 1 ,5655.963,186.81,197.94,188.35
XS GIS Cut Line= 3
1634523.09940679 720191.022139371633994.86194621720124.375619099
1633839.35274278720121.907120124
#Sta/Elev= 30
       0  105.77   14.11  104.92   49.39  104.08    63.5  103.03   84.67  102.75
   98.78  101.71  176.39   98.41  246.94   93.03  275.16    92.6  331.61   89.88
  345.72    90.3     381   90.06  395.11   88.87  416.27   89.55  437.44    87.8
   444.5    88.6  451.55   88.65  471.32   87.66  479.77   86.31  486.83   85.99
  501.45    88.2  522.11   89.12  532.42   90.47  539.43    92.6  560.43  101.19
  574.43  104.79  616.43  108.11  630.44  109.76  651.44  112.82  687.95  119.27
#Mann= 3 , 0 , 0
       0      .1       0  471.32    .045       0  501.45      .1       0
Bank Sta=471.32,501.45
XS Rating Curve= 0 ,0
Exp/Cntr=0.3,0.1

Type RM Length L Ch R = 1 ,5458.022,100.9,87.61,66.17
XS GIS Cut Line= 5
1634513.64012755719966.6539231841634202.93437569719963.019937769
1634145.69910561719963.0199377691634121.16970415719959.385952353
1633891.32012749719983.006857485
#Sta/Elev= 30
       0  104.03   84.01   99.81  112.01   97.94  126.01   97.48  147.01   95.93
  168.01   93.94  196.01   93.27  231.02   91.22  280.02   89.81  294.02   88.57
  310.73   88.21  331.73   86.88  360.19   86.88  367.96   86.34  375.04   84.94
  382.12   84.41  393.13   86.48   399.8   87.35  420.91   87.97  427.94   88.44
  434.98   89.57  449.05   92.59  463.13   94.56  470.16   96.07   477.2   96.89
  491.28   97.32  498.31   97.82  505.35   98.65  589.79   110.5  623.82  115.94
#Mann= 3 , 0 , 0
       0      .1       0  360.19    .045       0  393.13      .1       0
Bank Sta=360.19,393.13
XS Rating Curve= 0 ,0
Exp/Cntr=0.3,0.1

Type RM Length L Ch R = 1 ,5370.416,237.94,269.68,258.28
XS GIS Cut Line= 4
1634541.82917966719848.5215958651634175.99500614719861.013494492
1634129.59652559719891.3509625351633892.25045206719919.903873637
#Sta/Elev= 30
       0  104.06   14.01  103.14  112.07   98.95  154.09   96.59  189.11   95.55
  217.13    95.2  238.14   95.64  245.14    95.4  259.15   94.08  280.16   89.96
  287.17   89.25  308.18   89.61  329.19   88.02  357.21   90.58  366.05   90.92
  374.41   89.99  390.97   86.04   399.5   84.23  407.86   83.56  420.96   85.99
  428.53   86.62  470.84   86.74  477.89   88.23  491.99   92.07  499.04   93.47
  513.14   95.07  534.29   96.24  555.44   98.29  611.85  108.03  660.54  114.66
#Mann= 3 , 0 , 0
       0      .1       0  390.97    .045       0  420.96      .1       0
Bank Sta=390.97,420.96
XS Rating Curve= 0 ,0
Exp/Cntr=0.3,0.1

Type RM Length L Ch R = 1 ,5100.735,260.3,288.35,267.97
XS GIS Cut Line= 4
1634484.72335744719593.3299528811634249.16184084719609.390965387
1634015.38488115719648.6512181461633826.22184511 719686.12691398
#Sta/Elev= 30
       0   102.9   21.05   102.2   49.11  102.24    84.2  101.63  119.28   99.84
  133.31   98.43  154.36   95.62  196.46   89.08  210.49   86.51  224.52   84.91
  243.21   83.48   264.5    82.8  328.38   82.43  349.68   82.74  363.87   83.63
  378.07   83.48  399.36   84.28  420.66   84.17  427.76   83.67  441.95   82.36
  449.05   82.26  463.25   83.32   501.7   85.98  508.84   86.96  523.11   90.55
  530.25   91.91  558.79   93.55  594.47   97.35  623.02  101.96     666  111.36
#Mann= 3 , 0 , 0
       0      .1       0  427.76    .045       0  463.25      .1       0
Bank Sta=427.76,463.25
XS Rating Curve= 0 ,0
Exp/Cntr=0.3,0.1

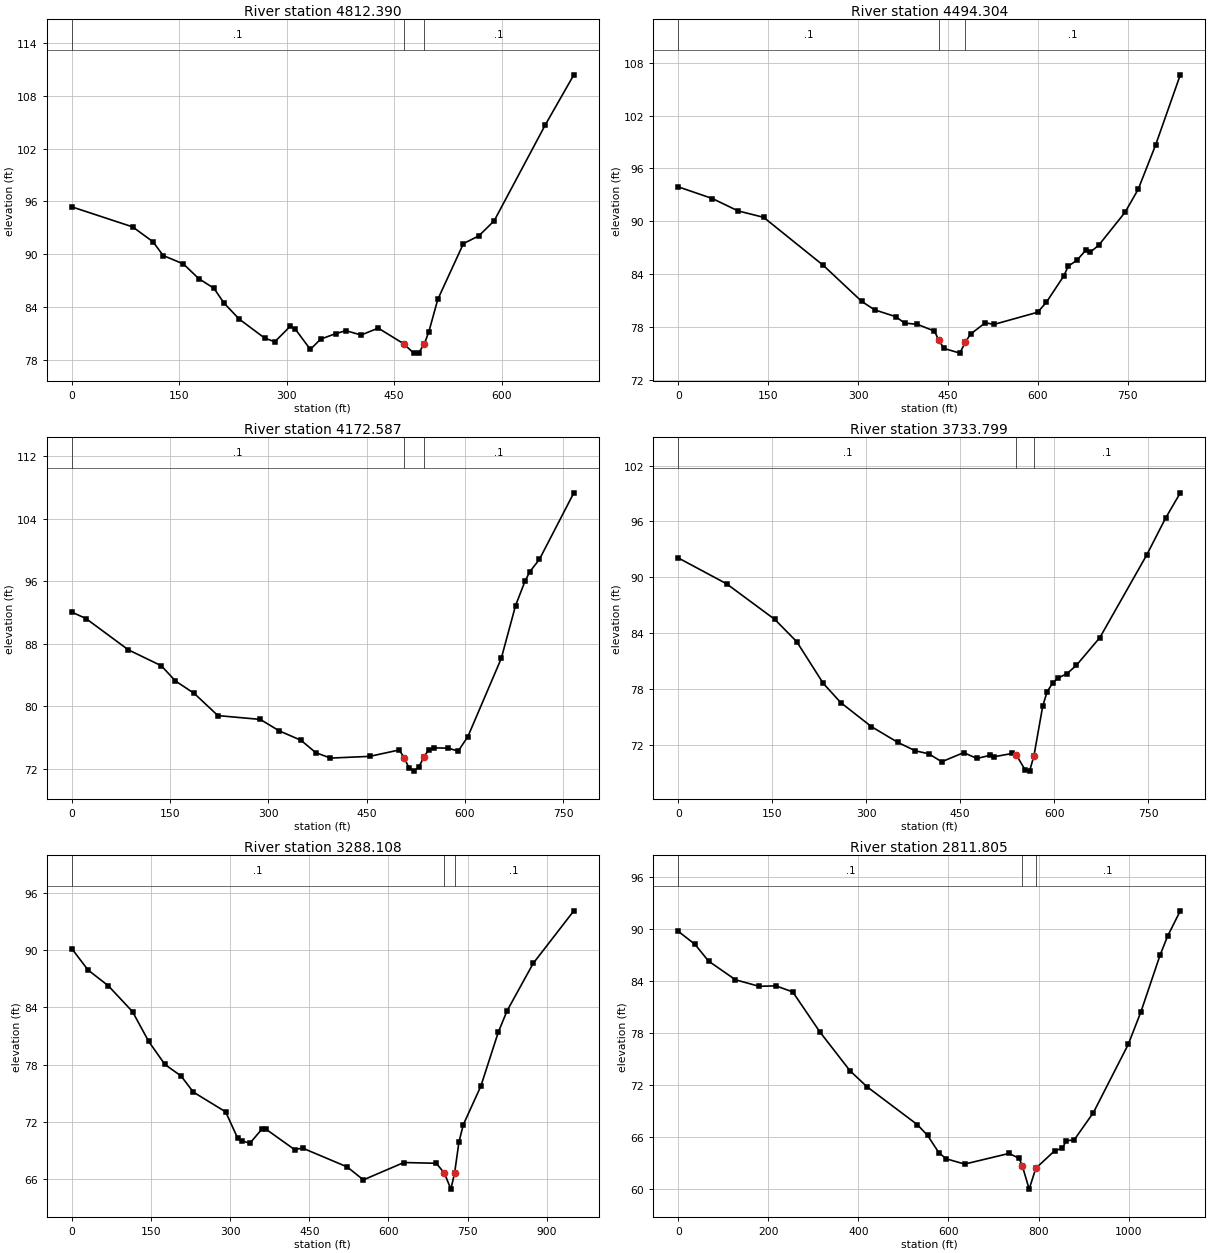
Type RM Length L Ch R = 1 ,4812.390,242.65,318.09,266.56
XS GIS Cut Line= 4
1634468.66234495719313.1545126741634059.99880475719377.398562685
1633970.77095756719389.8904612811633778.03880762719430.935270995
#Sta/Elev= 30
       0   95.39   85.03   93.11  113.38   91.42  127.55   89.86  155.89    88.9
  177.15   87.24  198.41   86.14  212.58   84.45  233.84   82.63  269.27   80.48
  283.44   80.06   304.7    81.8  311.78   81.52  333.04   79.19  347.21   80.35
  368.47   80.99  382.64   81.32   403.9   80.83  427.82   81.61  463.16   79.84
   477.3   78.77  484.37   78.82   492.2   79.83   498.5   81.22  510.94   84.88
  546.72   91.22  568.19   92.09  589.66   93.81  661.23  104.74  700.83  110.39
#Mann= 3 , 0 , 0
       0      .1       0  463.16    .045       0   492.2      .1       0
Bank Sta=463.16,492.2
XS Rating Curve= 0 ,0
Exp/Cntr=0.3,0.1

Type RM Length L Ch R = 1 ,4494.304,276.54,321.72,333.4
XS GIS Cut Line= 4
1634531.12183799719049.0400849731634095.68994363719131.129704416
 1634061.7833617719173.9590710551633735.20944098719268.540589079
#Sta/Elev= 30
       0   93.91   56.99   92.58   99.73   91.18  142.47   90.45  242.19   84.99
   306.3    80.9  327.67   79.95  363.29   79.17  377.54   78.45  398.91   78.31
   427.4   77.54  434.52   76.56   443.1   75.58  469.89   75.04  478.81   76.26
  487.74    77.2   512.3   78.48  526.88    78.3  599.76   79.68  614.33   80.82
  643.48   83.82  650.77   84.91  665.34   85.58  679.92   86.72  687.21   86.48
  701.78    87.3  745.51   91.02  767.37   93.62  796.52   98.66  837.72  106.62
#Mann= 3 , 0 , 0
       0      .1       0  434.52    .045       0  478.81      .1       0
Bank Sta=434.52,478.81
XS Rating Curve= 0 ,0
Exp/Cntr=0.3,0.1

Type RM Length L Ch R = 1 ,4172.587,298.59,438.79,353.99
XS GIS Cut Line= 4
1634476.19989432718749.4774502811634150.37114964718825.997638434
1633898.59442222718922.265162438 1633743.0852188718966.696504027
#Sta/Elev= 30
       0   92.07   21.57   91.25   86.29   87.24  136.62    85.2  158.19   83.25
  186.95   81.65   222.9   78.82  287.62   78.33  316.38   76.87  349.68   75.66
  372.16   74.08  394.65   73.38   454.6    73.6  499.57   74.42  507.06   73.45
  514.56   72.09  522.05   71.71  529.54   72.22  537.04   73.51  544.53   74.42
  552.03   74.69  574.51   74.65   589.5   74.27  604.25   76.12  655.21   86.13
  677.05    92.9  691.61   96.06  698.89   97.25  713.45   98.82  765.98  107.34
#Mann= 3 , 0 , 0
       0      .1       0  507.06    .045       0  537.04      .1       0
Bank Sta=507.06,537.04
XS Rating Curve= 0 ,0
Exp/Cntr=0.3,0.1

Type RM Length L Ch R = 1 ,3733.799,356.63,445.69,326.61
XS GIS Cut Line= 3
1634451.51588857718539.6635654421633854.16340874718569.284241125
 1633664.0965316718640.867759347
#Sta/Elev= 30
       0   92.07   77.09   89.29  154.19   85.45  189.23   83.05  231.28   78.59
  259.32   76.51  308.38   73.92  350.43   72.23  378.46   71.32  399.49   71.01
  420.52   70.15  455.56   71.13  476.59    70.5  497.61   70.84  504.62   70.69
  532.65   71.04  539.66   70.86  553.68   69.26  560.69   69.14   567.7   70.82
  581.71   76.16  588.72   77.69  598.09   78.67  605.57   79.13  620.53   79.63
  635.49   80.53  672.89   83.51  747.69    92.4  777.61   96.34  801.19   99.07
#Mann= 3 , 0 , 0
       0      .1       0  539.66    .045       0   567.7      .1       0
Bank Sta=539.66,567.7
XS Rating Curve= 0 ,0
Exp/Cntr=0.3,0.1

Type RM Length L Ch R = 1 ,3288.108,355.39,476.3,297.61
XS GIS Cut Line= 4
1634505.82056995717981.8054292051633858.17812991718272.482070282
1633845.26676798718280.9412384481633654.22286372718401.433198854
#Sta/Elev= 30
       0   90.17   30.69   87.93   69.05   86.28  115.09   83.56  145.78   80.43
  176.47   78.02  207.16   76.81  230.18   75.13  291.56   73.05  314.58   70.26
  322.25      70   337.6   69.77  360.62   71.27  368.29   71.22     422    69.1
  437.35   69.25  521.75   67.28  552.44   65.92  629.16   67.74  690.55   67.66
  705.89   66.63  718.25   64.95  725.32   66.65  733.59   69.92  741.87   71.72
  774.97   75.74  808.08   81.41  824.63   83.64  874.29   88.63  951.19   94.13
#Mann= 3 , 0 , 0
       0      .1       0  705.89    .045       0  725.32      .1       0
Bank Sta=705.89,725.32
XS Rating Curve= 0 ,0
Exp/Cntr=0.3,0.1

Type RM Length L Ch R = 1 ,2811.805,199.22,338.25,253.18
XS GIS Cut Line= 6
1634483.60506323717638.6978476791633965.24127053717833.701394707
1633804.79539722717932.4374177011633782.57956237717996.615767017
1633666.26253776718159.8533014361633607.32335119 718245.92399545
#Sta/Elev= 30
       0   89.71   37.39   88.19   67.31   86.27  127.14   84.11  179.49   83.36
  216.89   83.41  254.28   82.71  314.12   78.12  381.43   73.61  418.82   71.78
     531   67.39  553.83   66.14  578.49   64.17  594.93   63.45  636.02   62.84
  734.65   64.07  757.04    63.5  764.44   62.57  779.26   59.95  794.07   62.36
  835.92   64.38  853.11   64.67  861.71   65.55   878.9   65.61  921.88   68.78
  999.23   76.65 1027.54   80.43 1069.96   86.96 1086.93   89.18 1114.89   92.07
#Mann= 3 , 0 , 0
       0      .1       0  764.44    .045       0  794.07      .1       0
Bank Sta=764.44,794.07
XS Rating Curve= 0 ,0
Exp/Cntr=0.3,0.1

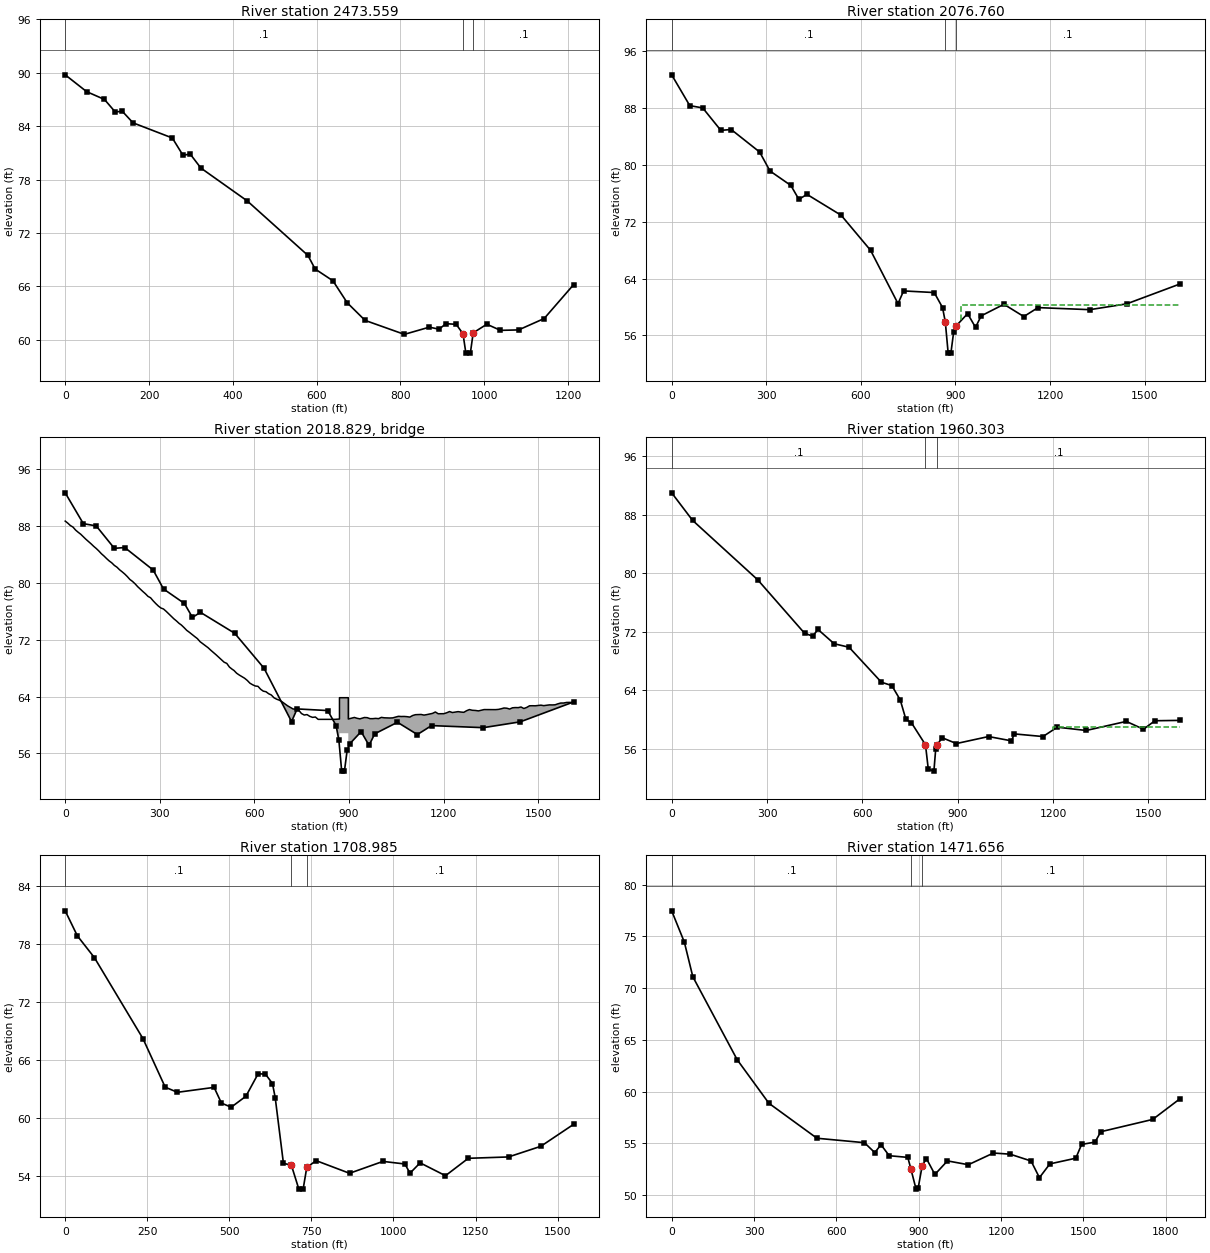
Type RM Length L Ch R = 1 ,2473.559,346.08,396.8,182.72
XS GIS Cut Line= 4
1634431.76855268717270.9065885251633698.65420531717779.396713272
1633565.36050865717858.3854004291633466.62481372717991.679097101
#Sta/Elev= 30
       0   89.77   51.11   87.88   93.71      87  119.27    85.6   136.3   85.67
  161.86   84.37  255.57   82.67  281.13   80.72  298.16   80.87  323.72   79.29
  434.47   75.59  579.29   69.46  596.33   67.94  638.92   66.61     673   64.14
  715.59   62.16   809.3   60.59  868.94    61.4   892.2   61.17  908.47   61.79
  932.88   61.72  949.16   60.67  956.05   58.51  966.79   58.48  973.57   60.76
 1006.11   61.73 1038.66   61.04 1081.98   61.09 1142.96   62.37 1213.02   66.17
#Mann= 3 , 0 , 0
       0      .1       0  949.16    .045       0  973.57      .1       0
Bank Sta=949.16,973.57
XS Rating Curve= 0 ,0
Exp/Cntr=0.5,0.3

Type RM Length L Ch R = 1 ,2076.760,112.46,116.46,187.07
BEGIN DESCRIPTION:
Center of channel lowered 2 feet to match clearance
information from bridge survey.
END DESCRIPTION:
XS GIS Cut Line= 6
1634217.65722831716721.4554289581634024.74000432 717036.75447166
1633929.82648414717175.4907814261633838.29176378 717309.90176414
1633683.28721195  717511.68379661633269.21235032718022.616227046
#Sta/Elev= 30
       0    92.7   57.44   88.36   98.48   88.04  155.92   84.88  188.75      85
  279.02   81.83  311.84   79.16  378.12   77.12  403.56   75.16  429.01   75.87
  537.73   72.92  630.89   67.99     718   60.48  735.66   62.27  832.76   62.04
  859.24   59.93  868.06   57.87  876.89   53.58  885.72   53.51  894.54   56.51
  903.37   57.39  938.68   59.07  963.81   57.14  981.83   58.76 1053.93   60.39
 1117.01   58.66 1162.07   59.92 1326.37   59.63 1443.48   60.45 1612.45   63.25
#Mann= 3 , 0 , 0
       0      .1       0  868.06     .04       0  903.37      .1       0
#XS Ineff= 2 , 0
       0                  918.84       0   60.33
Permanent Ineff=
       F       F
Bank Sta=868.06,903.37
XS Rating Curve= 0 ,0
Exp/Cntr=0.5,0.3

Type RM Length L Ch R = 3 ,2018.829,,,
BEGIN DESCRIPTION:
Blue Ball Road, MDE Bridge #: CE050307PF-3
Top of road obtained from DEM.
Opening from MDE2 bridge/culvert surveys.
END DESCRIPTION:
Bridge Culvert--1,0,-1,-1, 0
Deck Dist Width WeirC Skew NumUp NumDn MinLoCord MaxHiCord MaxSubmerge Is_Ogee
43,28,2.6,0, 186, 186, , , 0.95, 0, 2,2,,
       0    8.21   16.41   24.62   32.83   41.03   49.24   57.44   65.65   73.86
   82.06   90.27   98.48  106.68  114.89   123.1   131.3  139.51  147.71  155.92
  164.13  172.33  180.54  188.75  196.95  205.16  213.36  221.57  229.78  237.98
  246.19   254.4   262.6  270.81  279.02  287.22  295.43  303.63  311.84  320.05
  328.25  336.46  344.67  352.87  361.08  368.36  376.84  385.33  393.81  402.29
  410.77  419.25  427.73  436.21  444.69  453.18  461.66  470.14  478.62   487.1
  495.58  504.06  512.55  521.03  529.51  535.24  543.71  552.18  560.65  569.12
  577.58  586.05  594.52  602.99  611.46  619.93   628.4  636.87  645.34  653.81
  662.27  670.74  679.21  687.68  696.48  705.31  714.14  722.96  731.79  740.62
  749.44  758.27   767.1  775.92  784.75  793.58  802.41  811.23  820.06  828.89
  837.71  846.54  855.37     870     870     898     898  908.33  917.16  925.98
  934.81  943.64  948.84  957.85  966.87  975.88  984.89   993.9 1002.91 1011.92
 1020.94 1029.95 1038.96 1047.97 1056.98    1066 1075.01 1084.02 1093.03 1102.04
 1111.05 1120.07 1129.08 1138.09  1147.1 1156.11 1165.13 1174.14 1183.15 1192.16
 1201.17 1210.19  1219.2 1228.21 1237.22 1246.23 1255.24 1264.26 1273.27 1282.28
 1291.29 1301.76 1310.77 1319.77 1328.78 1337.79  1346.8 1355.81 1364.81 1373.82
 1382.83 1391.84 1400.85 1409.86 1418.86 1427.87 1436.88 1445.89  1454.9  1463.9
 1472.91 1481.92 1490.93 1499.94 1508.95 1517.95 1526.96 1535.97 1544.98 1553.99
 1562.99    1572 1581.01 1590.02 1599.03 1612.45
   88.72   88.43   88.09   87.88   87.46   87.15   86.87   86.51   86.16   85.85
   85.52   85.17   84.86   84.51   84.12    83.8   83.44   83.11   82.84   82.48
   82.23   81.87   81.58   81.27   80.91    80.5   80.23   79.89   79.49   79.14
   78.81   78.49   78.12   77.92   77.49   77.11   76.76   76.48   76.34   76.02
   75.67   75.32   74.96   74.66   74.32   74.09   73.73   73.34   73.06   72.75
   72.46   72.17   71.74   71.46   71.17   70.89   70.54   70.22   69.89   69.55
   69.22   68.85   68.68   68.16   67.86   67.69    67.3   67.04   66.82   66.59
   66.28   65.89   65.67    65.5   65.45   65.04   64.77   64.69   64.41   64.23
   63.84   63.64    63.5   63.28   62.99   62.71   62.49   62.26   62.24   62.09
   61.62   61.41   61.47   61.22   61.08   61.13    60.8    60.8    60.8    60.8
    60.8    60.8    60.8   60.85   63.85   63.85   60.85   60.97   61.07   60.95
   60.87   60.98   61.06   61.04    60.9    60.9   60.94    60.9   61.08   61.02
      61   60.99   61.01   61.12   61.23    61.2   61.21   61.18   61.12   61.34
   61.46   61.47   61.49    61.4   61.47   61.56   61.64   61.84   61.59    61.6
    61.6   61.73    61.9   61.76   61.82   61.89   61.83   61.79   62.02   62.18
   62.08   62.05   61.99   62.08   62.18   62.18   62.17   62.19   62.17    62.2
   62.29    62.4   62.37   62.25   62.43   62.46   62.45   62.54   62.33   62.48
   62.71   62.72   62.71   62.76    62.8   62.73   62.79   62.84   62.83   62.85
   62.99    63.1    63.1   63.18   63.19   63.18
                                                                                
                                                                                
                                                                                
                                                                                
                                                                                
                                                                                
                                                                                
                                                                                
                                                                                
                                                                                
                                   58.85   58.85
                                                                                
                                                                                
                                                                                
                                                                                
                                                                                
                                                                                
                                                                                
                                                
       0    8.21   16.41   24.62   32.83   41.03   49.24   57.44   65.65   73.86
   82.06   90.27   98.48  106.68  114.89   123.1   131.3  139.51  147.71  155.92
  164.13  172.33  180.54  188.75  196.95  205.16  213.36  221.57  229.78  237.98
  246.19   254.4   262.6  270.81  279.02  287.22  295.43  303.63  311.84  320.05
  328.25  336.46  344.67  352.87  361.08  368.36  376.84  385.33  393.81  402.29
  410.77  419.25  427.73  436.21  444.69  453.18  461.66  470.14  478.62   487.1
  495.58  504.06  512.55  521.03  529.51  535.24  543.71  552.18  560.65  569.12
  577.58  586.05  594.52  602.99  611.46  619.93   628.4  636.87  645.34  653.81
  662.27  670.74  679.21  687.68  696.48  705.31  714.14  722.96  731.79  740.62
  749.44  758.27   767.1  775.92  784.75  793.58     802     802     830     830
  837.71  846.54  855.37  864.19  873.02  881.85  890.68   899.5  908.33  917.16
  925.98  934.81  943.64  948.84  957.85  966.87  975.88  984.89   993.9 1002.91
 1011.92 1020.94 1029.95 1038.96 1047.97 1056.98    1066 1075.01 1084.02 1093.03
 1102.04 1111.05 1120.07 1129.08 1138.09  1147.1 1156.11 1165.13 1174.14 1183.15
 1192.16 1201.17 1210.19  1219.2 1228.21 1237.22 1246.23 1255.24 1264.26 1273.27
 1282.28 1291.29 1301.76 1310.77 1319.77 1328.78 1337.79  1346.8 1355.81 1364.81
 1373.82 1382.83 1391.84 1400.85 1409.86 1418.86 1427.87 1436.88 1445.89  1454.9
  1463.9 1472.91 1481.92 1490.93 1499.94 1508.95 1517.95 1526.96 1535.97 1544.98
 1553.99 1562.99    1572 1581.01 1590.02 1599.28
   88.72   88.43   88.09   87.88   87.46   87.15   86.87   86.51   86.16   85.85
   85.52   85.17   84.86   84.51   84.12    83.8   83.44   83.11   82.84   82.48
   82.23   81.87   81.58   81.27   80.91    80.5   80.23   79.89   79.49   79.14
   78.81   78.49   78.12   77.92   77.49   77.11   76.76   76.48   76.34   76.02
   75.67   75.32   74.96   74.66   74.32   74.09   73.73   73.34   73.06   72.75
   72.46   72.17   71.74   71.46   71.17   70.89   70.54   70.22   69.89   69.55
   69.22   68.85   68.68   68.16   67.86   67.69    67.3   67.04   66.82   66.59
   66.28   65.89   65.67    65.5   65.45   65.04   64.77   64.69   64.41   64.23
   63.84   63.64    63.5   63.28   62.99   62.71   62.49   62.26   62.24   62.09
   61.62   61.41   61.47   61.22   61.08   61.13   60.85   63.85   63.85   60.85
   60.82    60.8    60.8   60.95   60.98    60.8   60.83      61   60.97   61.07
   60.95   60.87   60.98   61.06   61.04    60.9    60.9   60.94    60.9   61.08
   61.02      61   60.99   61.01   61.12   61.23    61.2   61.21   61.18   61.12
   61.34   61.46   61.47   61.49    61.4   61.47   61.56   61.64   61.84   61.59
    61.6    61.6   61.73    61.9   61.76   61.82   61.89   61.83   61.79   62.02
   62.18   62.08   62.05   61.99   62.08   62.18   62.18   62.17   62.19   62.17
    62.2   62.29    62.4   62.37   62.25   62.43   62.46   62.45   62.54   62.33
   62.48   62.71   62.72   62.71   62.76    62.8   62.73   62.79   62.84   62.83
   62.85   62.99    63.1    63.1   63.18   63.19
                                                                                
                                                                                
                                                                                
                                                                                
                                                                                
                                                                                
                                                                                
                                                                                
                                                                                
                                                           58.85   58.85
                                                                                
                                                                                
                                                                                
                                                                                
                                                                                
                                                                                
                                                                                
                                                                                
                                                
BR Coef=-1 , 0 , 0 ,, 0 ,,,0.8,0,,0,
WSPro=,,,, 1 ,,,, 0 ,,,, 0 ,,,,-1 ,-1 ,-1 , 0 , 0 , 0 , 0 , 0
BC Design=,, 0 ,, 0 ,,,,,,
BC Use User HTab Curves=0
BC User HTab FreeFlow(D)= 0

Type RM Length L Ch R = 1 ,1960.303,229.45,251.32,247.39
BEGIN DESCRIPTION:
Upstream limit of Detailed Study - Section B
Center of channel lowered 2 feet to match clearance
information from bridge survey.
END DESCRIPTION:
XS GIS Cut Line= 6
1634132.35728209716669.2642497871633940.76871344716982.391771764
1633847.23247929717119.1148848831633757.24722157717251.250613078
1633604.78454046717449.723685652 1633191.5054328717959.674706787
#Sta/Elev= 30
       0   90.98   65.65   87.22  270.81   79.08  417.98   71.78  443.42   71.38
  460.38   72.29  511.27   70.34  558.15   69.86  659.78   65.08  692.61   64.62
  719.09   62.66  736.75   60.02   754.4   59.53  798.54   56.52  807.36   53.18
  825.02   52.92  830.66   55.92  833.84   56.48   851.5   57.48  895.63   56.69
  996.96   57.65 1069.05   57.06 1078.06   58.01 1168.18   57.65 1213.24   58.93
 1304.17   58.48 1430.28   59.72 1484.33   58.65 1520.36   59.81 1599.28   59.86
#Mann= 3 , 0 , 0
       0      .1       0  798.54     .04       0  833.84      .1       0
#XS Ineff= 2 , 0
       0                    1200       0      59
Permanent Ineff=
       F       F
Bank Sta=798.54,833.84
XS Rating Curve= 0 ,0
Exp/Cntr=0.5,0.3

Type RM Length L Ch R = 1 ,1708.985,242.36,237.33,198.32
XS GIS Cut Line= 6
1633973.13991492716711.6542221611633685.17298335716810.953164086
1633579.25411193717102.2300603841633349.01337743717420.400016084
1633214.95980586717708.366947621  1633197.582491717926.824619859
#Sta/Elev= 30
       0   81.47   37.02   78.88   88.85   76.63  236.94   68.24  304.61   63.22
  341.85   62.69  453.58    63.2  475.92   61.57  505.71   61.15  550.41   62.28
  587.65   64.61  609.99   64.57  631.28    63.6  639.65   62.15  664.76   55.34
   688.9   55.15  711.69   52.67  724.75   52.67  735.82   54.91  764.21   55.62
  866.11   54.31  968.02   55.54 1034.82   55.27 1050.26   54.32 1081.15   55.39
 1158.36   54.06 1227.85   55.86 1350.36      56 1448.67    57.1 1548.44   59.37
#Mann= 3 , 0 , 0
       0      .1       0   688.9     .04       0  735.82      .1       0
#XS Ineff= 2 , 0
                          760.92           55.22
Permanent Ineff=
       F       F
Bank Sta=688.9,735.82
XS Rating Curve= 0 ,0
Exp/Cntr=0.3,0.1

Type RM Length L Ch R = 1 ,1471.656,273.46,390.48,263.43
XS GIS Cut Line= 5
1633939.26168872716514.6419590411633458.21348122716735.306274429
1633303.74846044717128.0887558011633131.63029446717529.697809786
1633144.87015338717993.092872053
#Sta/Elev= 30
       0   77.48   46.21   74.45   77.01   71.11  238.74   63.08  354.26   58.87
  529.24   55.49  702.25   55.06  739.86    54.1  762.42   54.87  792.51    53.8
  860.21   53.64  871.84   52.48  890.29   50.57  897.82   50.65  912.58   52.83
   927.9   53.53  958.92   51.99 1004.62    53.3 1080.78   52.93 1172.17   54.06
 1233.09   53.95 1309.25   53.29 1339.71   51.68 1377.79   53.01 1472.28   53.56
 1493.29   54.89 1542.31   55.12 1563.31   56.12 1752.39   57.31 1851.83   59.31
#Mann= 3 , 0 , 0
       0      .1       0  871.84     .04       0  912.58      .1       0
#XS Ineff= 2 , 0
                          929.21           53.31
Permanent Ineff=
       F       F
Bank Sta=871.84,912.58
XS Rating Curve= 0 ,0
Exp/Cntr=0.3,0.1