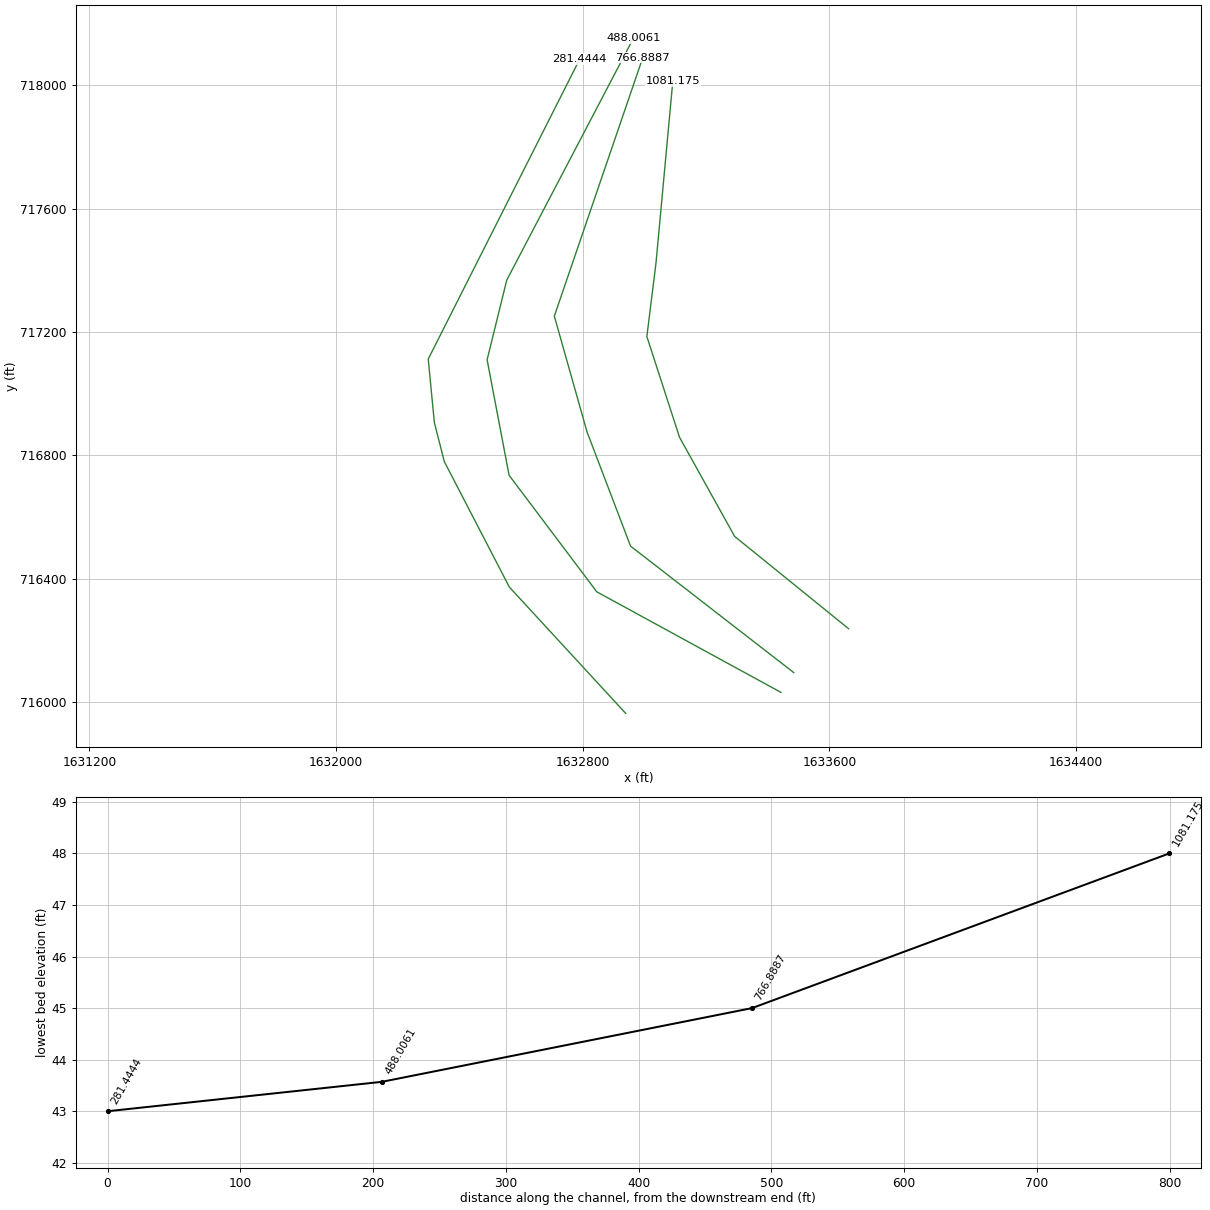
HEC-RAS study GravellyRun.prj: Gravelly Run

--- GravellyRun.g01 (geometry) --- (continued)

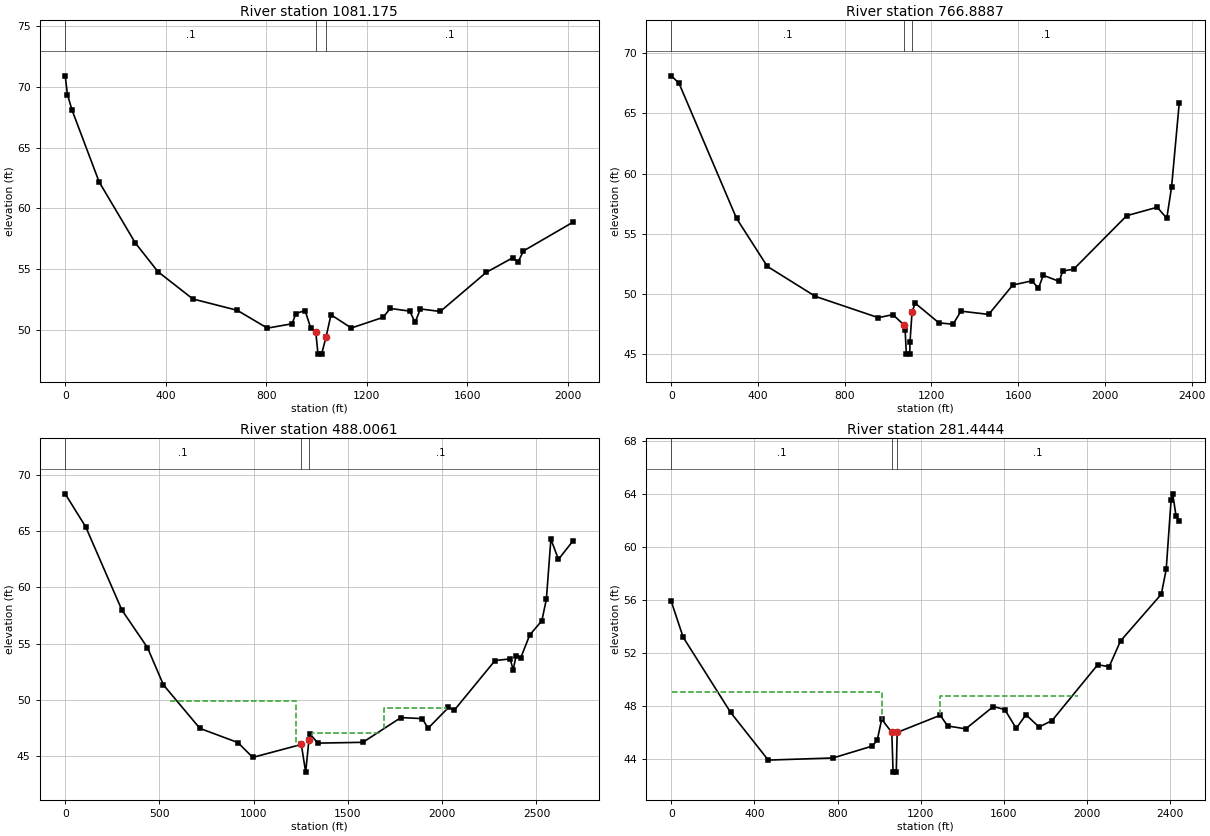
Type RM Length L Ch R = 1 ,1081.175,278.05,314.29,274.58
XS GIS Cut Line= 6
1633662.49049935716237.745993793 1633292.7405833716537.278531238
1633113.97714919716858.8782910411633008.05827783717185.461477786
1633037.81622493717425.1924392431633092.31846033718014.542189777
#Sta/Elev= 30
       0   70.91    9.01   69.37   27.03    68.1  135.13   62.17  279.27   57.14
  369.36   54.78  507.89   52.54  684.08   51.61  804.21   50.14  902.67    50.5
  917.38   51.34  954.18   51.59  976.26   50.17  996.74   49.79 1005.63      48
 1019.88      48 1037.96   49.44 1057.21   51.24 1138.15   50.15 1264.72   51.03
 1292.93   51.76 1370.52   51.54 1391.68   50.61 1412.85   51.72 1491.97   51.51
 1674.74   54.73 1780.19   55.93 1801.28   55.56 1822.37   56.49 2020.56   58.87
#Mann= 3 , 0 , 0
       0      .1       0  996.74     .04       0 1037.96      .1       0
#XS Ineff= 4 ,-1
       0  952.14   50.71 1064.31  1301.1   50.64  1301.1 1587.74   51.69
 1587.74 2020.56   50.64
Permanent Ineff=
       F       F       F       F
Bank Sta=996.74,1037.96
XS Rating Curve= 0 ,0
Exp/Cntr=0.3,0.1

Type RM Length L Ch R = 1 ,766.8887,284.84,278.88,257.46
BEGIN DESCRIPTION:
Section A
END DESCRIPTION:
XS GIS Cut Line= 5
1633484.69319904716095.3797598481632955.09884213716505.815386429
1632813.87368026716876.5314362791632707.95480891717251.660772413
1632994.81841892718090.185170829
#Sta/Elev= 30
       0   68.12   35.42   67.51  301.11   56.27  442.81   52.29  664.21    49.8
  954.67   48.03 1022.08   48.28 1071.58 47.4532 1078.56      47  1083.9      45
 1099.71      45 1100.92      46 1110.37   48.52 1124.91   49.23 1234.02    47.6
 1299.48   47.48 1335.85   48.57 1463.92    48.3 1574.89   50.74 1663.67   51.09
 1693.27   50.47 1715.46   51.55 1789.44   51.04 1804.24    51.9 1856.03   52.06
 2100.17    56.5 2240.74    57.2 2285.13   56.29 2307.32    58.9 2342.75   65.89
#Mann= 3 , 0 , 0
       0      .1       0 1071.58     .04       0 1110.37      .1       0
Bank Sta=1071.58,1110.37
XS Rating Curve= 0 ,0
Exp/Cntr=0.3,0.1

Type RM Length L Ch R = 1 ,488.0061,168.6,206.56,204.62
XS GIS Cut Line= 6
  1633443.148077716031.2590344551632845.74539946716357.410941437
1632561.10128398716735.6880734561632489.94001004717110.220132187
1632553.61048503717368.6474374091632964.22613525 718152.79416208
#Sta/Elev= 30
       0   68.32   109.2   65.37  300.57   57.99  436.29   54.65  521.12   51.33
  714.57   47.46  916.05    46.2   994.9   44.88 1252.52   46.03  1275.7   43.57
 1292.94   46.43 1297.07      47 1339.82   46.15 1578.97   46.22 1780.83   48.42
 1894.11   48.33 1925.03   47.47 2033.24   49.32 2064.16   49.08 2280.04   53.49
 2360.18   53.64  2376.2   52.68 2392.23    53.9 2416.27   53.72 2464.35   55.77
 2528.45   57.03 2552.49   58.94 2576.53   64.29  2616.6   62.49 2694.75   64.16
#Mann= 3 , 0 , 0
       0      .1       0 1252.52     .04       0 1292.94      .1       0
#XS Ineff= 3 ,-1
  556.33 1223.33   49.94 1306.86 1678.4247.05153 1688.92 2021.6549.27362
Permanent Ineff=
       F       F       F
Bank Sta=1252.52,1292.94
XS Rating Curve= 0 ,0
Exp/Cntr=0.3,0.1

Type RM Length L Ch R = 1 ,281.4444,209.3,281.44,258.84
XS GIS Cut Line= 6
1632939.40524203715963.1880434161632562.06926271716372.796178818
1632351.05901113716779.9218406981632318.78685503716906.527991623
1632298.92706661 717112.573296131632790.45682912718085.702926934
#Sta/Elev= 30
       0    55.9   57.11    53.2  285.53   47.51  466.36   43.91  777.68   44.07
  966.91   44.97  990.56   45.42  1012.1      47 1060.69      46 1066.77      43
  1082.1      43 1086.39      46 1293.82    47.3 1328.98   46.49 1415.88   46.27
 1549.19   47.96 1604.09   47.73 1658.99   46.31 1706.04   47.34 1768.78   46.41
 1831.52    46.9  2051.1   51.12    2106   50.97 2160.89   52.92 2356.95   56.45
 2380.48   58.33    2404   63.58 2411.85   64.04 2427.53   62.39 2443.36   61.97
#Mann= 3 , 0 , 0
       0      .1       0 1060.69     .04       0 1086.39      .1       0
#XS Ineff= 2 ,-1
    4.99 1015.6549.09151 1291.13 1956.63 48.7454
Permanent Ineff=
       F       F
Bank Sta=1060.69,1086.39
XS Rating Curve= 0 ,0
Exp/Cntr=0.3,0.1

Chan Stop Cuts=-1
Use User Specified Reach Order=0
User Specified Reach Order=GravellyRun     ,Reach1