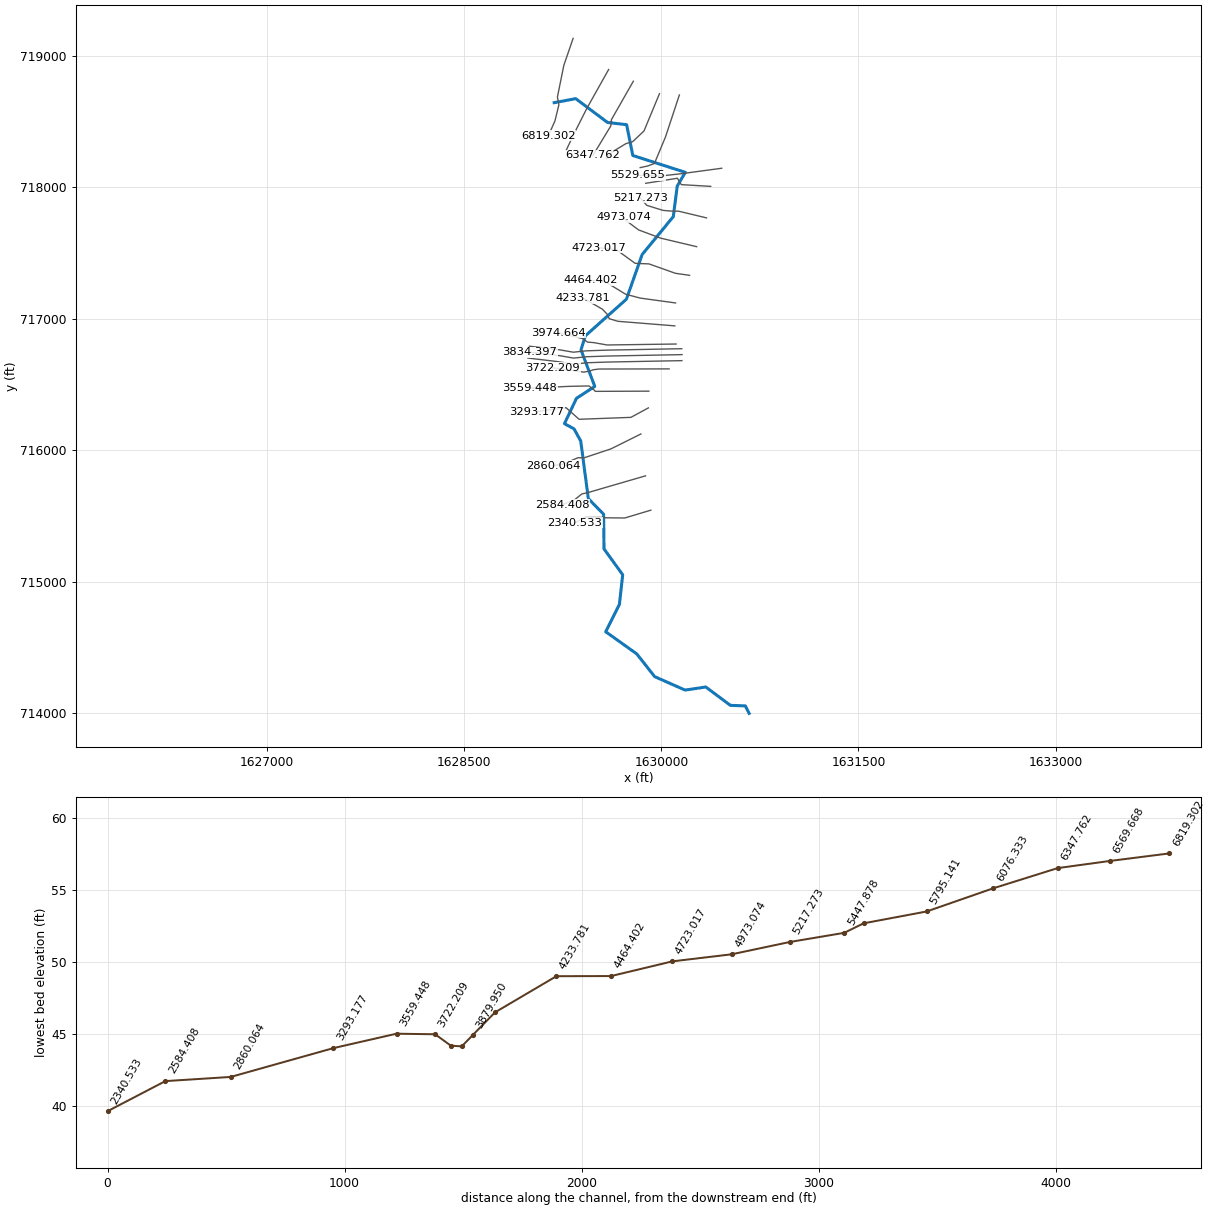
--- LaurelRun.prj (project) ---

Proj Title=LaurelRun
Current Plan=p02
Default Exp/Contr=0.3,0.1
English Units
Geom File=g02
Flow File=f02
Flow File=f03
Plan File=p02
Plan File=p03
Y Axis Title=Elevation
X Axis Title(PF)=Main Channel Distance
X Axis Title(XS)=Station
BEGIN DESCRIPTION:
Laurel Run - Georeferenced HEC-RAS model.  This was formerly an approximate method stream.  Projection:  MD Stateplane.  Horizontal datum:  NAD83.  Vertrial datum: NAVD88.  Units:Feet.  Created by: Aaron W. Buesing, USACE- St Paul District as part of FEMA Map Modernization study for Cecil County, MD.
END DESCRIPTION:
DSS Export Rating Curves= 0
DSS Export Rating Curve Sorted= 0
DSS Export Volume Flow Curves= 0
DXF OffsetX= 0
DXF OffsetY= 0
DXF ScaleX= 1
DXF ScaleY= 10

--- LaurelRun.p02 (plan) ---

Plan Title=Laurel Run Frequency Profiles
Program Version=4.00
Short Identifier=frequency
Geom File=g02
Flow File=f02
Subcritical Flow
K Sum by GR= 0
Std Step Tol= 0.01
Critical Tol= 0.01
Num of Std Step Trials= 20
Max Error Tol= 0.3
Flow Tol Ratio= 0.001
Split Flow NTrial= 30
Split Flow Tol= 0.02
Split Flow Ratio= 0.02
Log Output Level= 0
Friction Slope Method= 1
Unsteady Friction Slope Method= 2
Unsteady Bridges Friction Slope Method= 1
Parabolic Critical Depth
Global Vel Dist= 0 , 0 , 0
Global Log Level= 0
CheckData=True
Encroach Param=-1 ,0,0, 0
Computation Interval=1HOUR
Output Interval=1HOUR
Run HTab= 0
Run UNet= 0
Run PostProcess= 0
Run WQNet= 0
UNET Theta= 1
UNET Theta Warmup= 1
UNET ZTol= 0.02
UNET ZSATol= 0.05
UNET MxIter= 20
UNET MaxInSteps= 0
UNET DtIC= 0
UNET DtMin= 0
UNET MaxCRTS= 20
UNET WFStab= 2
UNET SFStab= 1
UNET WFX= 1
UNET SFX= 1
UNET DSS MLevel= 4
UNET DZMax Abort= 100
UNET Convert EG Bridges= 0
UNET Use Existing IB Tables=-1
UNET Froude Reduction=False
UNET Froude Limit= 1
UNET Froude Power= 10
UNET Time Slicing=0,0, 5
Instantaneous Interval=1HOUR
Write IC File= 0
Echo Input=False
Echo Output=False
Write Detailed= 0
Detailed Automatic Start=False, 10
WQ ULTIMATE=-1
WQ Max Comp Step=1HOUR
WQ Output Interval=15MIN
WQ Output Selected Increments= 0
WQ Output face flow=0
WQ Output face velocity=0
WQ Output face area=0
WQ Output face dispersion=0
WQ Output cell volume=0
WQ Output cell surface area=0
WQ Output cell continuity=0
WQ Output face conc=0
WQ Output face dconc_dx=0
WQ Output face courant=0
WQ Output face peclet=0
WQ Output face adv mass=0
WQ Output face disp mass=0
WQ Output cell mass=0
WQ Output cell source sink temp=0
WQ Output cell source sink nsm=0
WQ Output MaxMinRange=-1
WQ Daily Max Min Mean=-1
WQ Daily Range=0
WQ Daily Time=0
WQ Create Restart=0
WQ Fixed Restart=0
WQ System Summary=False
Sorting and Armoring Iterations= 10
XS Update Threshold= 0.02
Hydraulics Update Threshold= 0.02
Energy Slope Method= 1
Volume Change Method= 0
XS Weighting Method= 0
Number of US Weighted Cross Sections= 1
Number of DS Weighted Cross Sections= 1
Upstream XS Weight=0.25
Main XS Weight=0.5
Downstream XS Weight=0.25
Number of DS XS's Weighted with US Boundary= 1
Upstream Boundary Weight= 1
Weight of XSs Associated with US Boundary= 0
Number of US XS's Weighted with DS Boundary= 1
Downstream Boundary Weight= 0.5
Weight of XSs Associated with DS Boundary= 0.5
Sediment Output Level= 4
Mass or Volume Output= 0
Output Increment Type= 1
Profile and TS Output Increment= 10
XS Output Flag= 0
XS Output Increment= 10
Disregard all LS=0
Disregard all Conn=0
Disregard all Breaches=0
Disregard all Pumps=0

--- LaurelRun.p03 (plan) ---

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Plan Title=Laurel Run Floodway
Short Identifier=floodway
Geom File=g02
Flow File=f03
Encroach Param=-1 ,0,0, 2
Encroach River=LaurelRun
Encroach Reach=Herron
Encroach Node=5447.878
       1  188.65   304.5
Encroach Node=5217.273
       1  225.63  302.63
Encroach Node=4973.074
       1  280.38  340.85
Encroach Node=4723.017
       1  358.12  412.08
Encroach Node=4464.402
       1  337.63  385.27
Encroach Node=4233.781
       1  428.39  536.52
Encroach Node=3974.664
       1  579.34  729.22
Encroach Node=3879.950
       1     615     783
Encroach Node=3834.397
       1     603     780
Encroach Node=3788.488
       1     600     780
Encroach Node=3722.209
       1  515.37   679.1
Encroach Node=3559.448
       1  380.71  545.15
Encroach Node=3293.177
       1     435     660
Encroach Node=2860.064
       1     430     540
Encroach Node=2584.408
       1     407     503
Encroach Node=2340.533
       1     315     405
Encroach Node=2119.688
       1  356.91  417.15
Encroach Node=1861.534
       1     350     410
Encroach Node=1641.840
       1     400     480
Encroach Node=1458.192
       1  340.37  531.31
Encroach Node=1306.092
       1     365  520.95
Encroach Node=1134.053
       1     385  502.37
Encroach Node=935.1041
       1     365  506.47
Encroach Node=670.0407
       1  417.97  588.26
Encroach Node=530.4335
       1  361.74  509.75
Encroach Node=412.0457
       1     410  543.07
Encroach Node=235.9861
       1     410     510
Encroach Node=44.71898
       1     475     575

--- LaurelRun.f02 (steady flow) ---

Flow Title=Laurel Run Frequency Flows
Program Version=4.00
Number of Profiles= 5
Profile Names=10yr,50yr,100yr,500yr,100ult
River Rch & RM=LaurelRun,Herron          ,6819.302
     667    1552    2111    4086    2395
River Rch & RM=LaurelRun,Herron          ,1306.092
     753    1773    2412    4676    2697
Boundary for River Rch & Prof#=LaurelRun,Herron          , 1
Up Type= 0
Dn Type= 3
Dn Slope=0.005
Boundary for River Rch & Prof#=LaurelRun,Herron          , 2
Up Type= 0
Dn Type= 3
Dn Slope=0.005
Boundary for River Rch & Prof#=LaurelRun,Herron          , 3
Up Type= 0
Dn Type= 3
Dn Slope=0.005
Boundary for River Rch & Prof#=LaurelRun,Herron          , 4
Up Type= 0
Dn Type= 3
Dn Slope=0.005
Boundary for River Rch & Prof#=LaurelRun,Herron          , 5
Up Type= 0
Dn Type= 3
Dn Slope=0.005
DSS Import GetInterval= 0
DSS Import GetPeak= 0
DSS Import FillOption= 0

--- LaurelRun.f03 (steady flow) ---

Flow Title=Laurel Run Encroached Flows
Program Version=4.00
Number of Profiles= 2
Profile Names=100yr,100enc
River Rch & RM=LaurelRun,Herron          ,6819.302
    2111    2111
River Rch & RM=LaurelRun,Herron          ,1306.092
    2412    2412
Boundary for River Rch & Prof#=LaurelRun,Herron          , 1
Up Type= 0
Dn Type= 1
Dn Known WS=35.44
Boundary for River Rch & Prof#=LaurelRun,Herron          , 2
Up Type= 0
Dn Type= 1
Dn Known WS=36.44
DSS Import GetInterval= 0
DSS Import GetPeak= 0
DSS Import FillOption= 0

--- LaurelRun.g02 (geometry) ---

Geom Title=Laurel Run Geometry
Program Version=4.00
BEGIN GEOM DESCRIPTION:
Detailed from station 44 through 5447.  LOMR HEC-RAS used for channel data, GRID used for overbank elevations
END GEOM DESCRIPTION:

River Reach=LaurelRun       ,Herron
Reach XY= 30
1629185.03283843718642.8178611251629349.01214705 718673.33955723
1629591.39032224718492.0047743171629735.91953042718475.247764662
1629783.19823623718240.9488619861630182.67337678718112.817584693
 1630121.0315199  718008.08627441630091.10828841717775.881997928
1629854.11629489717487.3023533081629734.42336884717147.733522162
1629422.50360367 716869.447469161629388.98958434716762.920765013
1629493.72089463716484.335479707 1629354.5778681716393.668088213
1629263.01277973716200.9624773261629336.02546459 716161.46381174
1629386.89495815716069.0010263921629444.94602726715630.326452538
1629561.04816553 715511.830455781629564.04048869715248.206786215
1629706.17583832715051.6111551971629681.04032387714825.092292696
 1629576.7332924714618.0108357371629813.10485768714449.570101529
1629949.31310569714276.6237509851630180.83246875714174.034332633
1630338.18245503714197.6021719871630525.68541224714057.928065211
1630639.01899266714053.7690347431630668.13220593713996.928951606

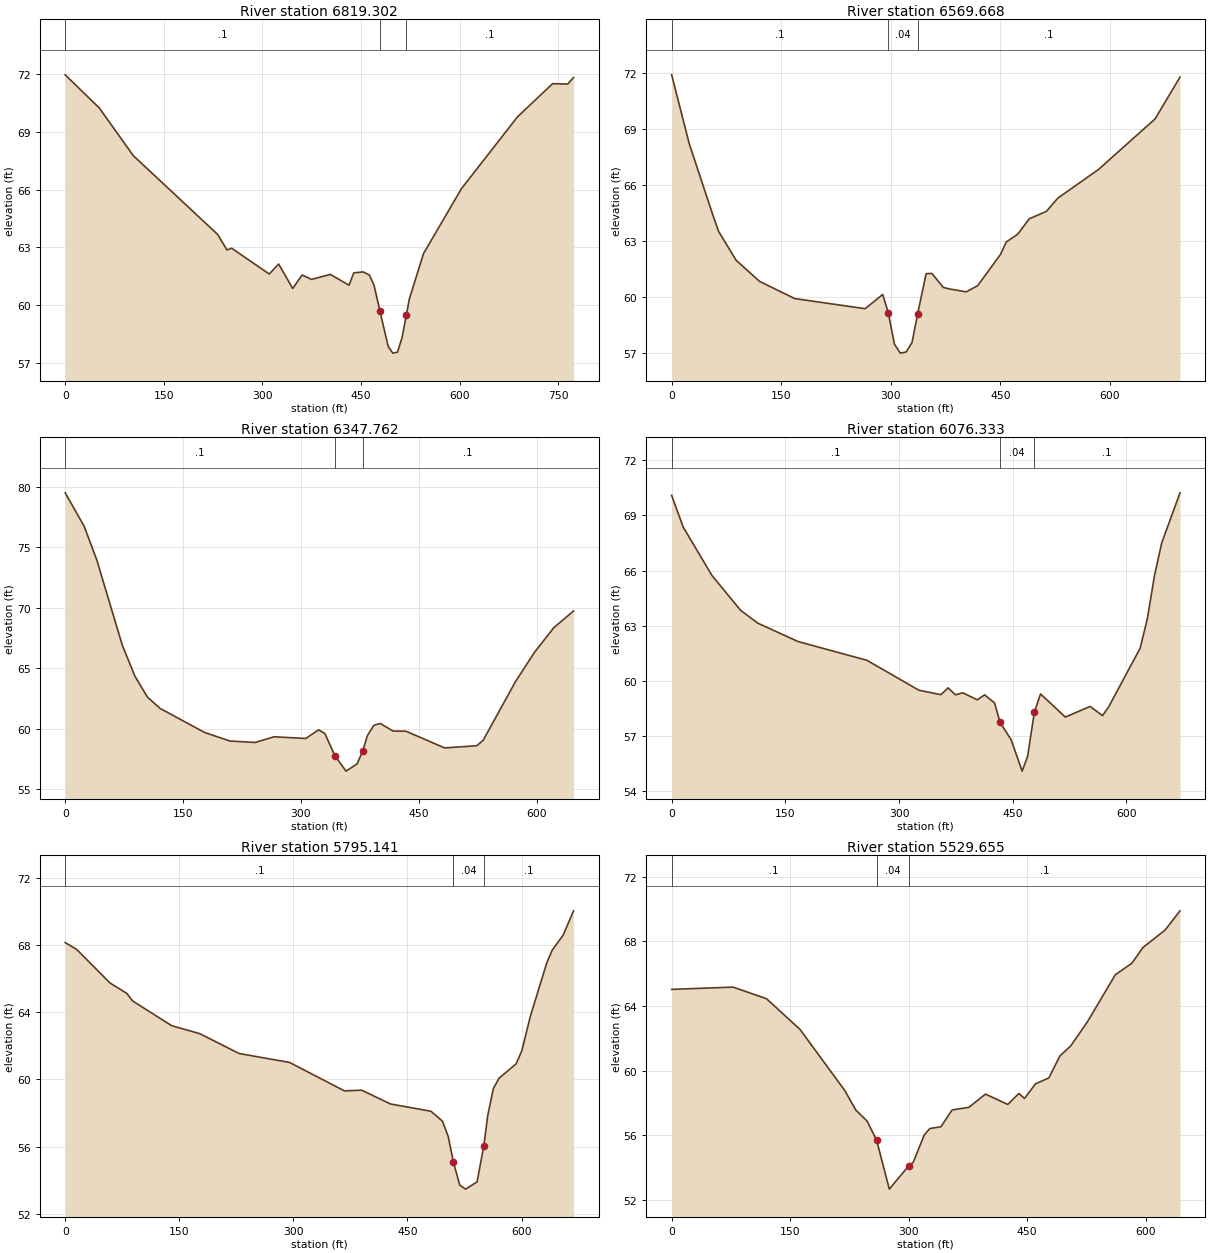
Type RM Length L Ch R = 1 ,6819.302,283.36,249.63,210.49
XS GIS Cut Line= 6
1629329.03515054719132.2193202971629258.35143092718926.451160446
1629209.65820313718686.1265163421629220.65344815718626.438041702
1629190.80921175718503.919595718 1629140.5452328718390.825645462
#Sta/Elev= 30
       0   71.97   51.81   70.25  103.62   67.77  231.85   63.68  246.14   62.87
  253.28   62.96  310.42   61.62   324.7   62.14  346.13   60.87  360.41   61.57
   374.7   61.34  403.27    61.6  431.84   61.04  438.98   61.68  453.26   61.73
  462.78   61.57   469.9   61.03  478.85   59.69  491.25   57.87  498.37   57.51
  505.48   57.56   512.6   58.33  518.91   59.47  523.47   60.31  545.09   62.68
  602.72   66.05  687.87   69.78  741.49   71.51  764.48   71.49  773.33   71.83
#Mann= 3 , 0 , 0
       0      .1       0  478.85     .04       0  518.91      .1       0
#XS Ineff= 2 , 0
          454.07   61.66
Permanent Ineff=
       F       F
Bank Sta=478.85,518.91
XS Rating Curve= 0 ,0
Exp/Cntr=0.3,0.1

Type RM Length L Ch R = 1 ,6569.668,206.9,221.91,230.62
XS GIS Cut Line= 4
1629599.20403293718895.0361747891629432.72933394718598.052995697
1629336.88889697718408.1038875581629275.62967302718279.302444473
#Sta/Elev= 30
       0   71.89   24.07    68.2   56.17   64.41    64.2   63.51   88.27   61.96
  120.37   60.83  168.52   59.91  264.82   59.37  288.89   60.13   296.5   59.16
  304.94   57.47  312.97   56.99  320.99   57.05  329.02   57.56  336.65   59.08
   348.3   61.24  356.14   61.26  371.82   60.51  379.66   60.43  403.18   60.27
  418.87    60.6  450.23   62.28  458.07   62.94  473.75   63.36  489.43   64.18
  512.95   64.58  528.63   65.29  584.22   66.82  661.74   69.53  695.85   71.77
#Mann= 3 , 0 , 0
       0      .1       0   296.5     .04       0  336.65      .1       0
#XS Ineff= 2 , 0
                          353.02           61.04
Permanent Ineff=
       F       F
Bank Sta=296.5,336.65
XS Rating Curve= 0 ,0
Exp/Cntr=0.3,0.1

Type RM Length L Ch R = 1 ,6347.762,260.1,271.43,135.95
XS GIS Cut Line= 4
1629787.26119412718806.1454707091629620.61204912718514.022136703
1629615.80489352718465.9505825041629479.82708362718241.604459792
#Sta/Elev= 30
       0    79.5   24.18   76.73   40.29   73.93   72.53   66.93   88.65   64.35
  104.77    62.6  120.88   61.67   177.3   59.69  209.53   58.98  241.77   58.86
  265.95   59.33  306.24   59.19  322.36    59.9  330.42   59.61  343.35   57.75
  357.42   56.49  371.49   57.09  378.52   58.13  384.63   59.43  392.81   60.28
     401   60.43  417.37    59.8  433.74   59.79  482.85   58.41  523.78   58.59
  531.96   59.04  572.89   63.87  597.45   66.33     622   68.36  646.96   69.73
#Mann= 3 , 0 , 0
       0      .1       0  343.35     .04       0  378.52      .1       0
Bank Sta=343.35,378.52
XS Rating Curve= 0 ,0
Exp/Cntr=0.3,0.1

Type RM Length L Ch R = 1 ,6076.333,179.24,281.19,286.83
XS GIS Cut Line= 6
1629985.95586018718711.1155090481629868.18055345718427.493339568
1629781.65175439718345.7716960911629731.17662242718331.350231171
1629627.82278255718268.8572101591629579.75122836718215.978500381
#Sta/Elev= 30
       0   70.09   15.16   68.37   53.06   65.74   90.95   63.84  113.69   63.14
  166.75   62.14   257.7   61.12  326.36   59.49  355.25   59.25  364.87   59.62
   374.5   59.24  384.13   59.35  403.39   58.97  413.02   59.24  426.12    58.8
   433.4   57.74  447.96    56.8  462.52   55.09   469.8    55.9  478.62   58.29
   486.8   59.29  519.52   58.03  552.24   58.61   568.6   58.11  576.78   58.59
  618.32   61.78  627.78   63.38  637.24   65.74   646.7    67.5  670.86   70.23
#Mann= 3 , 0 , 0
       0      .1       0   433.4     .04       0  478.62      .1       0
#XS Ineff= 2 , 0
                          489.93           59.04
Permanent Ineff=
       F       F
Bank Sta=433.4,478.62
XS Rating Curve= 0 ,0
Exp/Cntr=0.3,0.1

Type RM Length L Ch R = 1 ,5795.141,317.68,265.49,144.21
XS GIS Cut Line= 5
1630137.38125613718701.5011978151630031.62383652718381.825363174
1629947.49861722 718179.924835221629894.61990738718160.696212769
1629839.33761981718148.678323746
#Sta/Elev= 30
       0   68.13   14.75   67.74   58.98   65.73    81.1   65.11   88.48   64.67
  140.09   63.19  176.95   62.72  228.57   61.54  294.92   61.01  367.05   59.32
   389.8   59.36  427.72   58.54   480.8   58.11  495.97   57.52  503.55   56.61
  510.43   55.07  518.72   53.72   526.3   53.48  541.47   53.91   550.4   56.07
  555.44   57.84  562.89   59.46  570.34   60.07  592.68   60.92  600.13   61.68
  611.71   63.78   633.2   66.94  640.36   67.69  654.69   68.58  668.28   70.02
#Mann= 3 , 0 , 0
       0      .1       0  510.43     .04       0   550.4      .1       0
Bank Sta=510.43,550.4
XS Rating Curve= 0 ,0
Exp/Cntr=0.3,0.1

Type RM Length L Ch R = 1 ,5529.655,99.32,81.78,34.75
XS GIS Cut Line= 4
1630459.46066859718143.8711700441630156.60987663718103.010347366
1629985.95586018718083.7817268371629820.10899925718090.992460251
#Sta/Elev= 30
       0   65.02    77.7   65.16  120.08   64.44  162.46   62.54  218.97   58.77
  233.09   57.55  247.22   56.88  259.33   55.69  275.47   52.66  300.24   54.12
  305.59   54.31  319.68   56.01  326.73   56.41  340.82   56.52   354.9   57.56
  376.04   57.72  397.17   58.54  425.35    57.9  439.44   58.58  446.48   58.27
  460.57   59.18  477.33   59.54  491.34    60.9  505.35   61.54  526.37   63.03
  561.41   65.92  582.43   66.64  596.44   67.61  624.47   68.69  643.33   69.88
#Mann= 3 , 0 , 0
       0      .1       0  259.33     .04       0  300.24      .1       0
Bank Sta=259.33,300.24
XS Rating Curve= 0 ,0
Exp/Cntr=0.3,0.1

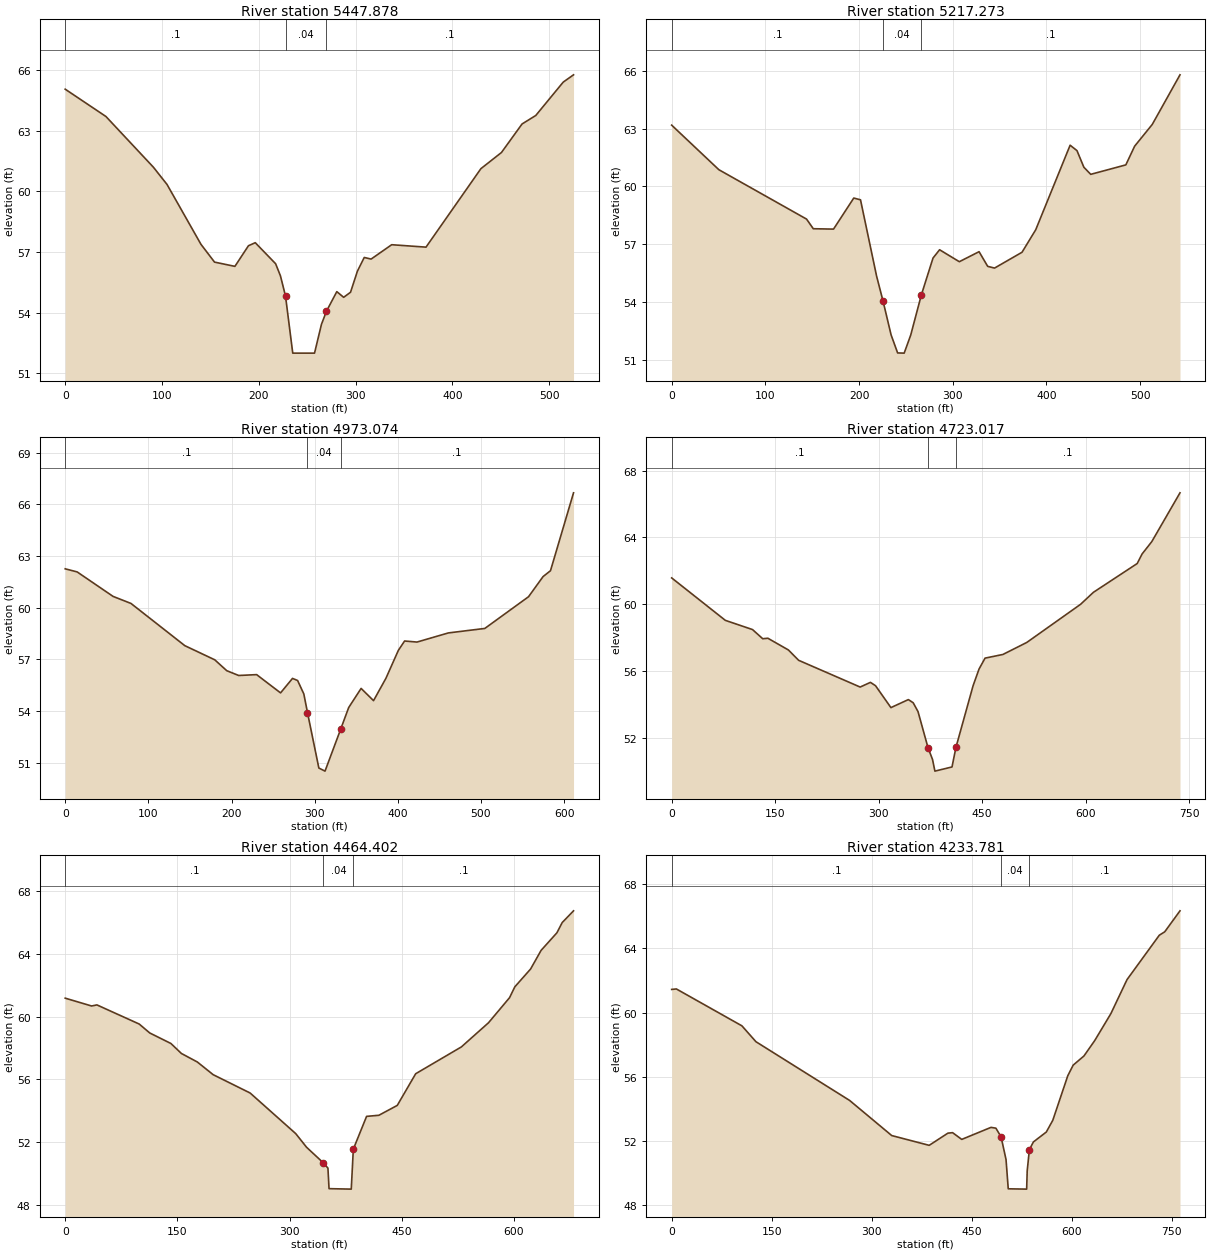
Type RM Length L Ch R = 1 ,5447.878,214.94,230.6,239.54
BEGIN DESCRIPTION:
Start of Detailed Reach
END DESCRIPTION:
XS GIS Cut Line= 6
1630375.64399913718006.1270008241630153.65800098718019.087999344
1630143.96999934718029.0610008391630134.28199965718047.013000503
1630122.56600003718067.8530006411629881.05500035718029.457000747
#Sta/Elev= 30
       0   65.05   42.07    63.7   91.15   61.19  105.18   60.34  140.24   57.38
  154.26    56.5   175.3   56.29  189.32   57.31  196.33   57.46  217.37   56.42
  222.36   55.82  227.59   54.82  235.06      52  257.56      52   264.7   53.42
  269.86   54.07  280.57   55.04  287.66   54.76  294.75   55.01  301.84   56.05
  308.93   56.73  316.01   56.65  337.28   57.36  372.72   57.24  429.42   61.12
  450.68   61.92  471.95   63.33  486.12   63.75  514.48    65.4  525.12   65.76
#Mann= 3 , 0 , 0
       0      .1       0  227.59     .04       0  269.86      .1       0
#XS Ineff= 2 , 0
          196.16   57.18
Permanent Ineff=
       F       F
Bank Sta=227.59,269.86
XS Rating Curve= 0 ,0
Exp/Cntr=0.3,0.1

Type RM Length L Ch R = 1 ,5217.273,235.7,244.2,204.07
XS GIS Cut Line= 6
1630343.82900052717766.3010005951630131.11100008717817.405000687
1630084.94199944717817.4549999241630012.77899937717823.288999572
1629889.99500084717861.6270008091629838.70499995717918.614999786
#Sta/Elev= 30
       0   63.18   50.39   60.87  143.98   58.31  151.18   57.81  172.78   57.79
  194.38    59.4  201.58   59.31  218.77   55.35  225.63   54.06  234.21   52.31
  241.21   51.37  248.21   51.36  255.21    52.3  266.49   54.37  278.99   56.29
  286.01   56.72  307.08    56.1  328.15   56.62  337.34   55.86  344.67   55.77
  374.01   56.59  388.67   57.76  425.34   62.14  432.67   61.86  440.01      61
  447.34   60.63  484.81   61.12  494.22   62.09  513.06   63.22  542.64   65.79
#Mann= 3 , 0 , 0
       0      .1       0  225.63     .04       0  266.49      .1       0
#XS Ineff= 2 , 0
                          290.51           56.22
Permanent Ineff=
       F       F
Bank Sta=225.63,266.49
XS Rating Curve= 0 ,0
Exp/Cntr=0.3,0.1

Type RM Length L Ch R = 1 ,4973.074,228.15,250.06,246.95
XS GIS Cut Line= 6
1630268.70000078717547.2719993741629996.75399974717611.795000076
1629952.61499979717627.8460006711629826.74500088717674.909999862
1629728.63299946717748.7639999391629711.81800085717770.788999558
#Sta/Elev= 30
       0   62.25   14.39   62.07   57.55   60.65   79.14   60.24  143.89   57.79
  179.86   56.97  194.25   56.34  208.64   56.06  230.22   56.11     259   55.05
  273.38   55.89   279.5   55.77  286.99   54.99  291.38   53.91  305.06   50.69
  312.48   50.51  331.36   52.95  340.95    54.2  355.89   55.31  370.83    54.6
  385.76    55.9   400.7   57.52  408.17   58.06  423.11      58  460.85   58.53
  504.66   58.79  557.23   60.63  574.75    61.8  583.65   62.14  611.36   66.66
#Mann= 3 , 0 , 0
       0      .1       0  291.38     .04       0  331.36      .1       0
Bank Sta=291.38,331.36
XS Rating Curve= 0 ,0
Exp/Cntr=0.3,0.1

Type RM Length L Ch R = 1 ,4723.017,274.2,258.61,241.43
XS GIS Cut Line= 6
1630215.20000081717329.277000442 1630106.6000004717344.909000412
1629906.56399921717416.1520004421629800.63299944717420.725999832
1629658.21299939717524.2630004881629526.57600026717539.072999954
#Sta/Elev= 30
       0   61.58   77.79   59.04  117.15   58.49  132.01   57.94  139.44   57.97
  169.16   57.27  184.03   56.65  273.19   55.05  288.06   55.33  295.49   55.13
  317.78   53.82  343.06    54.3  350.06   54.11  357.06   53.58   371.7    51.4
  378.07   50.72  381.54   50.02  406.34   50.27  412.08   51.45  436.88   55.13
  445.53   56.13  454.19   56.78  480.15      57  514.77   57.72  592.66      60
  611.35   60.72  674.75   62.44  681.79   63.01  695.88   63.75  736.77   66.67
#Mann= 3 , 0 , 0
       0      .1       0   371.7     .04       0  412.08      .1       0
Bank Sta=371.7,412.08
XS Rating Curve= 0 ,0
Exp/Cntr=0.3,0.1

Type RM Length L Ch R = 1 ,4464.402,217.03,230.62,198.52
XS GIS Cut Line= 6
 1630108.5849991 717119.187000291629839.07999995717156.190999985
1629728.38699916717185.6599998471629641.31299974717238.947000518
1629575.42000011717279.4409999851629462.32799916717291.334999099
#Sta/Elev= 30
       0   61.18   35.33   60.68   42.39   60.75   98.92   59.53  113.05   58.96
  141.31   58.29  155.44   57.65  176.64   57.11  197.84    56.3   247.3   55.13
  308.26   52.54  322.75   51.67   345.3   50.67  351.31   50.34  352.79   49.03
  382.51      49  385.27   51.55     403   53.64  419.41   53.71  444.03   54.34
  468.65   56.36  529.75   58.07  566.01   59.61  594.16   61.21   601.2    61.9
  622.32   63.04  636.39   64.23  657.51   65.35  664.55      66  679.72   66.75
#Mann= 3 , 0 , 0
       0      .1       0   345.3     .04       0  385.27      .1       0
Bank Sta=345.3,385.27
XS Rating Curve= 0 ,0
Exp/Cntr=0.3,0.1

Type RM Length L Ch R = 1 ,4233.781,197.48,259.12,270.48
XS GIS Cut Line= 6
1630103.01600075 716944.760999681629669.34509173 716979.62439464
        1629604.716999.4360008241629587.14900021717034.780000702
1629551.38699916717072.0149994191629405.49699976717155.910999313
#Sta/Elev= 30
       0   61.44    7.02   61.47  105.34   59.17  126.41   58.18  266.86   54.52
  330.06   52.33  386.24   51.72  414.33   52.48  421.36   52.51  435.07   52.09
  478.96   52.84  486.27   52.79  494.06   52.25  501.48   50.84  504.83   49.01
  532.45   48.99  533.24   50.12  536.52   51.45  542.51   51.93  561.92   52.55
  571.63   53.28  594.14   56.06  602.21   56.72  618.36   57.29  634.51   58.25
  658.74   59.93  682.96   62.05  731.41   64.82  739.49   65.03  762.43   66.34
#Mann= 3 , 0 , 0
       0      .1       0  494.06     .04       0  536.52      .1       0
#XS Ineff= 2 , 0
          475.55    52.7
Permanent Ineff=
       F       F
Bank Sta=494.06,536.52
XS Rating Curve= 0 ,0
Exp/Cntr=0.3,0.1

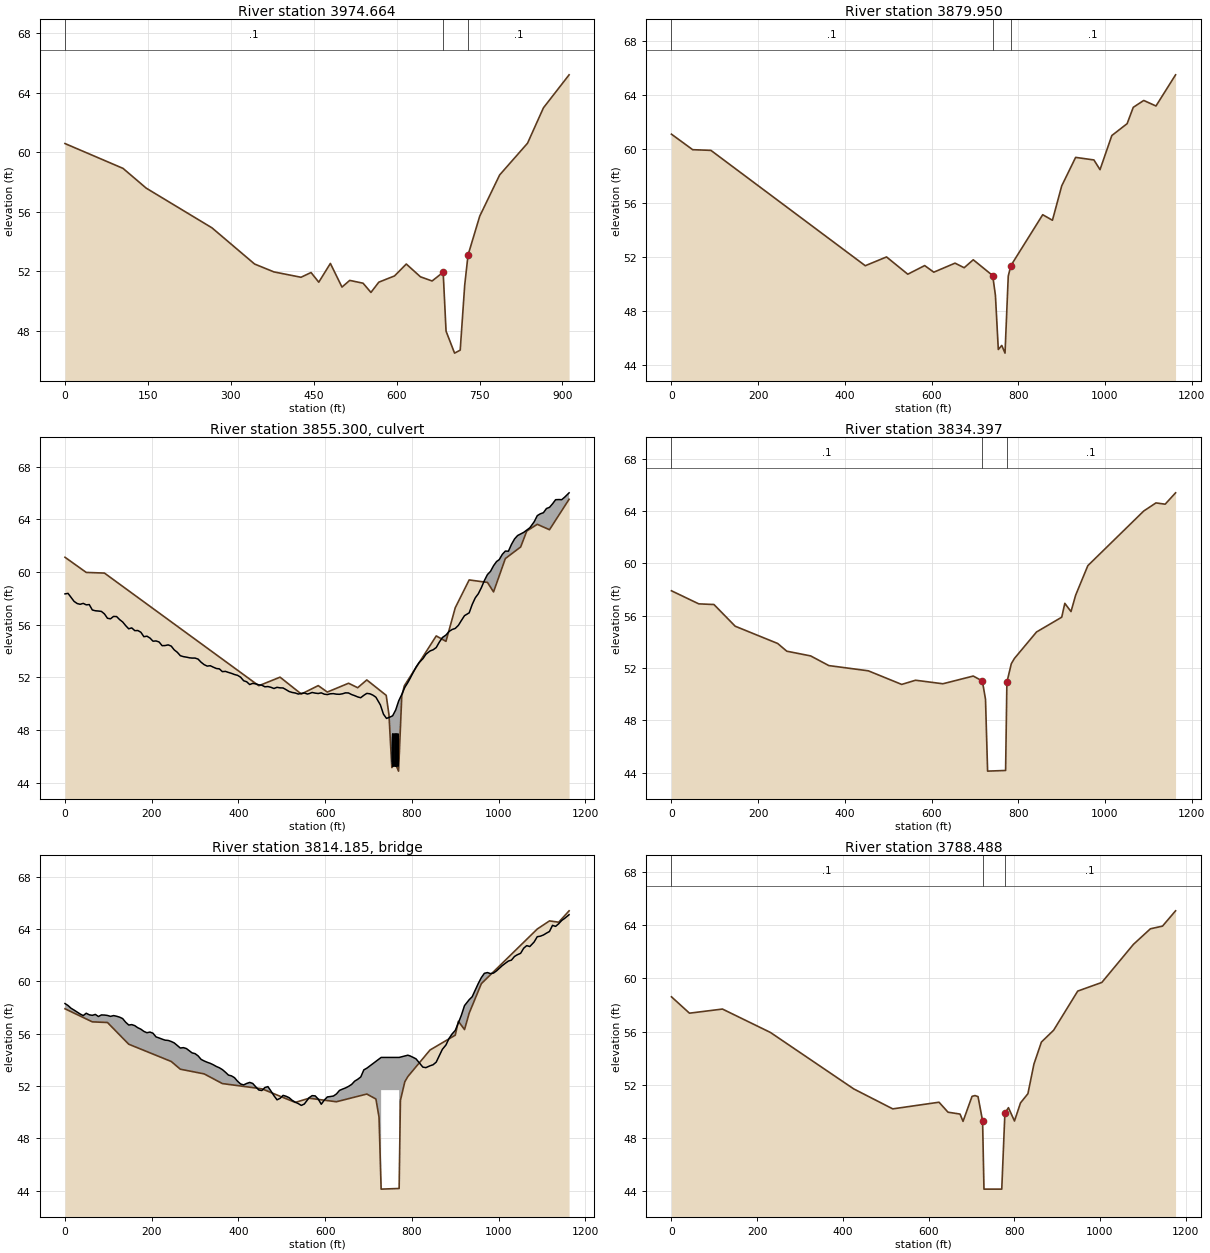
Type RM Length L Ch R = 1 ,3974.664,38.72,94.71,103.44
XS GIS Cut Line= 6
1630112.42750876716806.7641764281629587.35400011716799.511999145
1629484.95000079716817.5729999691629439.15099911716821.231000915
1629401.22500038716848.5380001221629215.97800066716891.392000213
#Sta/Elev= 30
       0   60.57  105.02    58.9  147.02   57.57  266.04    54.9  343.05   52.47
  378.06   51.94  427.06   51.58  445.17    51.9  459.17   51.25  480.17   52.51
  501.17   50.92  515.17   51.37  539.36   51.18  553.57   50.56  567.79   51.25
  596.22   51.67  617.55   52.47  643.17   51.61  664.24   51.33  684.25   51.92
  689.46   47.96  704.86   46.48  715.08   46.68   723.2   51.04  729.22   53.07
  750.43   55.69  786.46   58.46  836.86   60.59  865.66   62.97  912.09   65.19
#Mann= 3 , 0 , 0
       0      .1       0  684.25     .04       0  729.22      .1       0
#XS Ineff= 2 , 0
          679.77    51.7
Permanent Ineff=
       F       F
Bank Sta=684.25,729.22
XS Rating Curve= 0 ,0
Exp/Cntr=0.5,0.3

Type RM Length L Ch R = 1 ,3879.950,45.67,45.55,44.99
XS GIS Cut Line= 6
 1630155.4852066716771.0967269991629592.52611545716760.372281641
1629428.11665349716754.9521900121629330.68843462716744.503669366
 1629225.6706181716762.8434234861628996.81522183716790.175944924
#Sta/Elev= 30
       0   61.12      49   59.97   91.01   59.92  447.07   51.37  496.09   52.02
  545.11   50.74  584.09   51.38   605.1   50.89  654.12   51.56  675.14   51.22
  696.15   51.81  740.93   50.64  747.27   49.18  753.92   45.16  761.91   45.46
  769.42   44.89  776.86    50.6  782.79   51.37  856.34   55.15  878.81   54.74
  900.21   57.29  932.28    59.4  974.48   59.21  988.54   58.49 1015.76   61.02
 1051.08    61.9 1065.21   63.11  1089.4   63.62 1117.61   63.21 1162.79   65.52
#Mann= 3 , 0 , 0
       0      .1       0  740.93     .04       0  782.79      .1       0
#XS Ineff= 2 , 0
          696.66   51.57
Permanent Ineff=
       F       F
Bank Sta=740.93,782.79
XS Rating Curve= 0 ,0
Exp/Cntr=0.5,0.3

Type RM Length L Ch R = 2 ,3855.300,,,
BEGIN DESCRIPTION:
Zeitler Road, 30" Pipes, data taken from LOMR
END DESCRIPTION:
Bridge Culvert--1,0,-1,-1, 0
Deck Dist Width WeirC Skew NumUp NumDn MinLoCord MaxHiCord MaxSubmerge Is_Ogee
6,32,2.6,0, 165, 165, , , 0.98, 0, 0,0,,
       0       7      14      21      28      35      42      49      56      63
   70.01   77.01   84.01   91.01   98.01  105.01  112.01  119.01  126.01  133.01
  140.01  147.01  154.01  161.01  168.01  175.01  182.01  189.01  196.01  203.02
  210.02  217.02  224.02  231.02  238.02  245.02  252.02  259.02  266.02  273.02
  280.02  287.02  293.02  300.02  307.02  314.03  321.03  328.03  335.03  342.04
  349.04  356.04  363.04  370.05  377.05  384.05  391.05  398.06  405.06  412.06
  419.06  426.07  433.07  440.07  447.07  454.08  461.08  468.08  475.08  482.08
  489.09  496.09  503.09  510.09   517.1   524.1   531.1   538.1  545.11  552.11
  559.11  563.08  570.08  577.08  584.09  591.09  598.09   605.1   612.1  619.11
  626.11  633.11  640.12  647.12  654.12  661.13  668.13  675.14  682.14  689.14
  696.15  703.15  710.15  717.16  727.57  734.61  741.65   748.7  755.74  762.78
  769.82  776.86   783.9  790.94  795.78  802.82  809.86   816.9  825.56  832.57
  842.08  849.21  856.34  863.47   870.6  878.81  885.95  893.08  900.21  907.35
  914.48  921.61  932.28  939.32  946.35  953.38  960.41  967.45  974.48  981.51
  988.54  995.58 1001.63  1008.7 1015.76 1022.82 1029.89 1036.95 1044.02 1051.08
 1058.14 1065.21 1072.27 1082.35  1089.4 1096.46 1103.51 1110.56 1117.61 1124.67
 1131.72 1138.77 1145.83 1152.88 1162.79
   58.34   58.38   58.07   57.77   57.61   57.55   57.62   57.51   57.53   57.12
   57.06   57.04   57.01   56.82   56.49   56.45   56.63   56.62   56.39   56.21
   55.93   55.69   55.76   55.55   55.56   55.43   55.09   55.13   54.99   54.75
   54.77   54.69   54.41   54.42   54.47   54.38   54.09   53.91   53.65   53.58
   53.54   53.49   53.47   53.47   53.39   53.15   52.97   52.86   52.89   52.78
   52.68   52.65   52.44   52.46   52.38   52.31   52.22   52.16   52.02   51.75
   51.67   51.46   51.55   51.51   51.44   51.41   51.29   51.31   51.25   51.16
   51.25   51.21    51.2   51.07   50.93   50.86   50.82   50.74   50.79   50.82
   50.74   50.77   50.86   50.81   50.78   50.83   50.73    50.7   50.76   50.77
   50.73   50.72   50.76   50.83   50.82    50.7   50.62   50.52   50.46   50.64
   50.79   50.76   50.66    50.5   49.91   49.21   48.89   48.98   49.09   49.53
   50.23   50.71   51.25   51.62   51.91   52.36   52.79   53.13   53.42   53.76
   54.01    54.1   54.27   54.68   55.03   55.22   55.49   55.64   55.72   55.95
   56.33   56.69    56.9   57.54   58.04   58.35   58.81   59.36   59.81   60.05
   60.48    60.8   60.94   61.34   61.59   61.58    62.1   62.51   62.77   62.89
   63.01   63.18   63.36   63.82   64.28   64.42    64.5   64.82   64.91   65.18
   65.49    65.5   65.49   65.69   66.01
                                                                                
                                                                                
                                                                                
                                                                                
                                                                                
                                                                                
                                                                                
                                                                                
                                                                                
                                                                                
                                                                                
                                                                                
                                                                                
                                                                                
                                                                                
                                                                                
                                        
       0       7      14      21      28      35      42      49      56      63
   70.01   77.01   84.01   91.01   98.01  105.01  112.01  119.01  126.01  133.01
  140.01  147.01  154.01  161.01  168.01  175.01  182.01  189.01  196.01  203.02
  210.02  217.02  224.02  231.02  238.02  245.02  252.02  259.02  266.02  273.02
  280.02  287.02  293.02  300.02  307.02  314.03  321.03  328.03  335.03  342.04
  349.04  356.04  363.04  370.05  377.05  384.05  391.05  398.06  405.06  412.06
  419.06  426.07  433.07  440.07  447.07  454.08  461.08  468.08  475.08  482.08
  489.09  496.09  503.09  510.09   517.1   524.1   531.1   538.1  545.11  552.11
  559.11  563.08  570.08  577.08  584.09  591.09  598.09   605.1   612.1  619.11
  626.11  633.11  640.12  647.12  654.12  661.13  668.13  675.14  682.14  689.14
  696.15  703.15  710.15  717.16  727.57  734.61  741.65   748.7  755.74  762.78
  769.82  776.86   783.9  790.94  795.78  802.82  809.86   816.9  825.56  832.57
  842.08  849.21  856.34  863.47   870.6  878.81  885.95  893.08  900.21  907.35
  914.48  921.61  932.28  939.32  946.35  953.38  960.41  967.45  974.48  981.51
  988.54  995.58 1001.63  1008.7 1015.76 1022.82 1029.89 1036.95 1044.02 1051.08
 1058.14 1065.21 1072.27 1082.35  1089.4 1096.46 1103.51 1110.56 1117.61 1124.67
 1131.72 1138.77 1145.83 1152.88 1162.79
   58.34   58.38   58.07   57.77   57.61   57.55   57.62   57.51   57.53   57.12
   57.06   57.04   57.01   56.82   56.49   56.45   56.63   56.62   56.39   56.21
   55.93   55.69   55.76   55.55   55.56   55.43   55.09   55.13   54.99   54.75
   54.77   54.69   54.41   54.42   54.47   54.38   54.09   53.91   53.65   53.58
   53.54   53.49   53.47   53.47   53.39   53.15   52.97   52.86   52.89   52.78
   52.68   52.65   52.44   52.46   52.38   52.31   52.22   52.16   52.02   51.75
   51.67   51.46   51.55   51.51   51.44   51.41   51.29   51.31   51.25   51.16
   51.25   51.21    51.2   51.07   50.93   50.86   50.82   50.74   50.79   50.82
   50.74   50.77   50.86   50.81   50.78   50.83   50.73    50.7   50.76   50.77
   50.73   50.72   50.76   50.83   50.82    50.7   50.62   50.52   50.46   50.64
   50.79   50.76   50.66    50.5   49.91   49.21   48.89   48.98   49.09   49.53
   50.23   50.71   51.25   51.62   51.91   52.36   52.79   53.13   53.42   53.76
   54.01    54.1   54.27   54.68   55.03   55.22   55.49   55.64   55.72   55.95
   56.33   56.69    56.9   57.54   58.04   58.35   58.81   59.36   59.81   60.05
   60.48    60.8   60.94   61.34   61.59   61.58    62.1   62.51   62.77   62.89
   63.01   63.18   63.36   63.82   64.28   64.42    64.5   64.82   64.91   65.18
   65.49    65.5   65.49   65.69   66.01
                                                                                
                                                                                
                                                                                
                                                                                
                                                                                
                                                                                
                                                                                
                                                                                
                                                                                
                                                                                
                                                                                
                                                                                
                                                                                
                                                                                
                                                                                
                                                                                
                                        
BR Coef=-1 , 0 , 0 ,, 0 ,,,0.8,0,,0,
WSPro=,,,, 1 ,,,, 0 ,,,, 0 ,,,,-1 ,-1 ,-1 , 0 , 0 , 0 , 0 , 0
Multiple Barrel Culv=1,2.5,,32,0.013,0.5,1,1,1,45.24,44.94, 5,Culvert #1  , 0 ,6
     756     746     759     749     762     752     765     755     768     758
Culvert Bottom n=0.013
BC Design=,, 0 ,, 0 ,,,,,,
BC Use User HTab Curves=0
BC User HTab FreeFlow(D)= 0

Type RM Length L Ch R = 1 ,3834.397,46.44,45.91,45.88
XS GIS Cut Line= 6
1630157.79114828716726.1308648881629594.83205712716715.406419545
1629430.42259514716709.9863279161629332.99437627716699.537807256
1629227.97655976716717.8775613761628999.12116349716745.210082814
#Sta/Elev= 30
       0   57.91      63   56.91   98.01   56.86  147.01    55.2  245.02   53.88
  266.02   53.29  321.03   52.93  363.04   52.19  454.08   51.79   531.1   50.75
  563.08   51.07  626.11    50.8  696.15   51.39  717.16   51.01  724.39   49.62
  729.24   44.12  770.76   44.17  773.72   50.91   783.9   52.33  790.94   52.73
  842.08   54.76  900.21   55.89  907.35   56.95  921.61   56.32  932.28   57.57
  960.41   59.83  1089.4   64.01 1117.61   64.63 1138.77   64.53 1162.79    65.4
#Mann= 3 , 0 , 0
       0      .1       0  717.16     .04       0  773.72      .1       0
Bank Sta=717.16,773.72
XS Rating Curve= 0 ,0
Exp/Cntr=0.5,0.3

Type RM Length L Ch R = 3 ,3814.185,,,
BEGIN DESCRIPTION:
Zeitler Road wooden bridge, data taken from LOMR and MDE Survey
END DESCRIPTION:
Bridge Culvert--1,0,-1,-1, 0
Deck Dist Width WeirC Skew NumUp NumDn MinLoCord MaxHiCord MaxSubmerge Is_Ogee
15,16,2.6,0, 158, 158, , , 0.98, 0, 0,0,,
       0       7      14      21      28      35      42      49      56      63
   70.01   77.01   84.01   91.01   98.01  105.01  112.01  119.01  126.01  133.01
  140.01  147.01  154.01  161.01  168.01  175.01  182.01  189.01  196.01  203.02
  210.02  217.02  224.02  231.02  238.02  245.02  252.02  259.02  266.02  273.02
  280.02  287.02  293.02  300.02  307.02  314.03  321.03  328.03  335.03  342.04
  349.04  356.04  363.04  370.05  377.05  384.05  391.05  398.06  405.06  412.06
  419.06  426.07  433.07  440.07  447.07  454.08  461.08  468.08  475.08  482.08
  489.09  496.09  503.09  510.09   517.1   524.1   531.1   538.1  545.11  552.11
  559.11  563.08  570.09   577.1  584.11  591.13  598.14  605.15  612.17  619.18
  626.19  633.21  640.22  647.23  654.24  661.26  668.27  675.28   682.3  689.31
  696.32  706.66  729.23  729.23  770.76  770.76  790.75  795.65  802.69  809.73
  816.77  825.43  832.45  841.95  849.08  856.21  863.34  870.47  878.69  885.82
  892.95  900.09  907.22  914.35  921.48  932.16  939.19  946.22  953.25  960.29
  967.32  974.35  981.38  988.42  995.45 1001.51 1008.57 1015.63  1022.7 1029.76
 1036.82 1043.89 1050.95 1058.02 1065.08 1072.14 1082.22 1089.28 1096.33 1103.38
 1110.43 1117.49 1124.54 1131.59 1138.65  1145.7 1152.75 1162.66
   58.31   58.16   57.95   57.81   57.66   57.51   57.39   57.57   57.45   57.41
   57.48   57.32   57.44   57.43    57.4   57.33   57.39   57.34   57.27   57.16
   56.88   56.67    56.7   56.62   56.46   56.35   56.18   56.08   56.13   56.04
   55.76   55.68   55.59   55.51   55.49   55.41    55.3   55.11   54.91   54.94
   54.87   54.69   54.54   54.48   54.31   54.04   53.92   53.82   53.74   53.63
    53.5    53.4   53.26   53.06   52.84   52.78   52.64   52.37   52.16   52.09
    52.2   52.28    52.2   51.94    51.7   51.66   51.89   51.96   51.62   51.26
   50.95   51.06   51.29   51.22   51.11   50.91   50.77   50.66   50.52   50.63
   50.94   51.11   51.27   51.25   51.01   50.61   50.93   51.17    51.2   51.24
    51.4   51.67   51.77   51.86   51.98   52.13   52.38   52.52    52.7   53.24
   53.37   53.63   54.19   54.19   54.19   54.19   54.36   54.31    54.2   54.08
    53.8   53.45   53.41   53.55   53.63   53.83   54.32   54.81   55.14   55.64
   55.99   56.25   56.82   57.42   58.15    58.6   58.83   59.34   59.84   60.29
   60.62   60.68    60.6   60.64   60.81      61   61.21   61.39   61.56   61.63
   61.91   62.05   62.15   62.54   62.74   62.67   63.02   63.42   63.46   63.55
   63.69   63.82   64.29   64.21   64.41   64.66   64.83    65.1
                                                                                
                                                                                
                                                                                
                                                                                
                                                                                
                                                                                
                                                                                
                                                                                
                                                                                
                                                                                
                           51.69   51.69
                                                                                
                                                                                
                                                                                
                                                                                
                                                                
       0       7      14      21      28      35      42      49      56      63
   70.01   77.01   84.01   91.01   98.01  105.01  112.01  119.01  126.01  133.01
  140.01  147.01  154.01  161.01  168.01  175.01  182.01  189.01  196.01  203.02
  210.02  217.02  224.02  231.02  238.02  245.02  252.02  259.02  266.02  273.02
  280.02  287.02  293.02  300.02  307.02  314.03  321.03  328.03  335.03  342.04
  349.04  356.04  363.04  370.05  377.05  384.05  391.05  398.06  405.06  412.06
  419.06  426.07  433.07  440.07  447.07  454.08  461.08  468.08  475.08  482.08
  489.09  496.09  503.09  510.09   517.1   524.1   531.1   538.1  545.11  552.11
  559.11  563.08  570.09   577.1  584.11  591.13  598.14  605.15  612.17  619.18
  626.19  633.21  640.22  647.23  654.24  661.26  668.27  675.28   682.3  689.31
  696.32  706.66  729.23  729.23  770.76  770.76  790.75  795.65  802.69  809.73
  816.77  825.43  832.45  841.95  849.08  856.21  863.34  870.47  878.69  885.82
  892.95  900.09  907.22  914.35  921.48  932.16  939.19  946.22  953.25  960.29
  967.32  974.35  981.38  988.42  995.45 1001.51 1008.57 1015.63  1022.7 1029.76
 1036.82 1043.89 1050.95 1058.02 1065.08 1072.14 1082.22 1089.28 1096.33 1103.38
 1110.43 1117.49 1124.54 1131.59 1138.65  1145.7 1152.75 1162.66
   58.31   58.16   57.95   57.81   57.66   57.51   57.39   57.57   57.45   57.41
   57.48   57.32   57.44   57.43    57.4   57.33   57.39   57.34   57.27   57.16
   56.88   56.67    56.7   56.62   56.46   56.35   56.18   56.08   56.13   56.04
   55.76   55.68   55.59   55.51   55.49   55.41    55.3   55.11   54.91   54.94
   54.87   54.69   54.54   54.48   54.31   54.04   53.92   53.82   53.74   53.63
    53.5    53.4   53.26   53.06   52.84   52.78   52.64   52.37   52.16   52.09
    52.2   52.28    52.2   51.94    51.7   51.66   51.89   51.96   51.62   51.26
   50.95   51.06   51.29   51.22   51.11   50.91   50.77   50.66   50.52   50.63
   50.94   51.11   51.27   51.25   51.01   50.61   50.93   51.17    51.2   51.24
    51.4   51.67   51.77   51.86   51.98   52.13   52.38   52.52    52.7   53.24
   53.37   53.63   54.19   54.19   54.19   54.19   54.36   54.31    54.2   54.08
    53.8   53.45   53.41   53.55   53.63   53.83   54.32   54.81   55.14   55.64
   55.99   56.25   56.82   57.42   58.15    58.6   58.83   59.34   59.84   60.29
   60.62   60.68    60.6   60.64   60.81      61   61.21   61.39   61.56   61.63
   61.91   62.05   62.15   62.54   62.74   62.67   63.02   63.42   63.46   63.55
   63.69   63.82   64.29   64.21   64.41   64.66   64.83    65.1
                                                                                
                                                                                
                                                                                
                                                                                
                                                                                
                                                                                
                                                                                
                                                                                
                                                                                
                                                                                
                           51.69   51.69
                                                                                
                                                                                
                                                                                
                                                                                
                                                                
BR Coef=-1 , 0 , 0 ,, 0 ,,,0.8,0,,0,
WSPro=,,,, 1 ,,,, 0 ,,,, 0 ,,,,-1 ,-1 ,-1 , 0 , 0 , 0 , 0 , 0
BC Design=,, 0 ,, 0 ,,,,,,
BC Use User HTab Curves=0
BC User HTab FreeFlow(D)= 0

Type RM Length L Ch R = 1 ,3788.488,53.87,66.28,63.79
XS GIS Cut Line= 6
1630156.70462802716680.3279284091629595.49764256716669.639684543
1629435.14801601716664.3534334751629332.72448733716653.389266834
1629211.22004703 716672.998460651628984.57909781716700.151147708
#Sta/Elev= 30
       0   58.62      42   57.39  119.01    57.7  231.02   55.94  425.35    51.7
  516.38    50.2  624.36    50.7  645.37   49.95  673.38   49.81  680.39   49.26
   701.4   51.14   708.4    51.2  715.41   51.12  726.03    49.3  729.24   44.17
  770.76   44.17  778.09   49.88  786.37   50.29  800.44   49.29  814.52   50.65
  831.78   51.34  845.81   53.56  863.29   55.22  891.82   56.11  948.04   59.05
  1004.3    59.7 1078.01   62.56 1117.62   63.73 1145.84   63.93 1176.33   65.08
#Mann= 3 , 0 , 0
       0      .1       0  726.03     .04       0  778.09      .1       0
#XS Ineff= 2 , 0
          706.42   50.67
Permanent Ineff=
       F       F
Bank Sta=726.03,778.09
XS Rating Curve= 0 ,0
Exp/Cntr=0.5,0.3

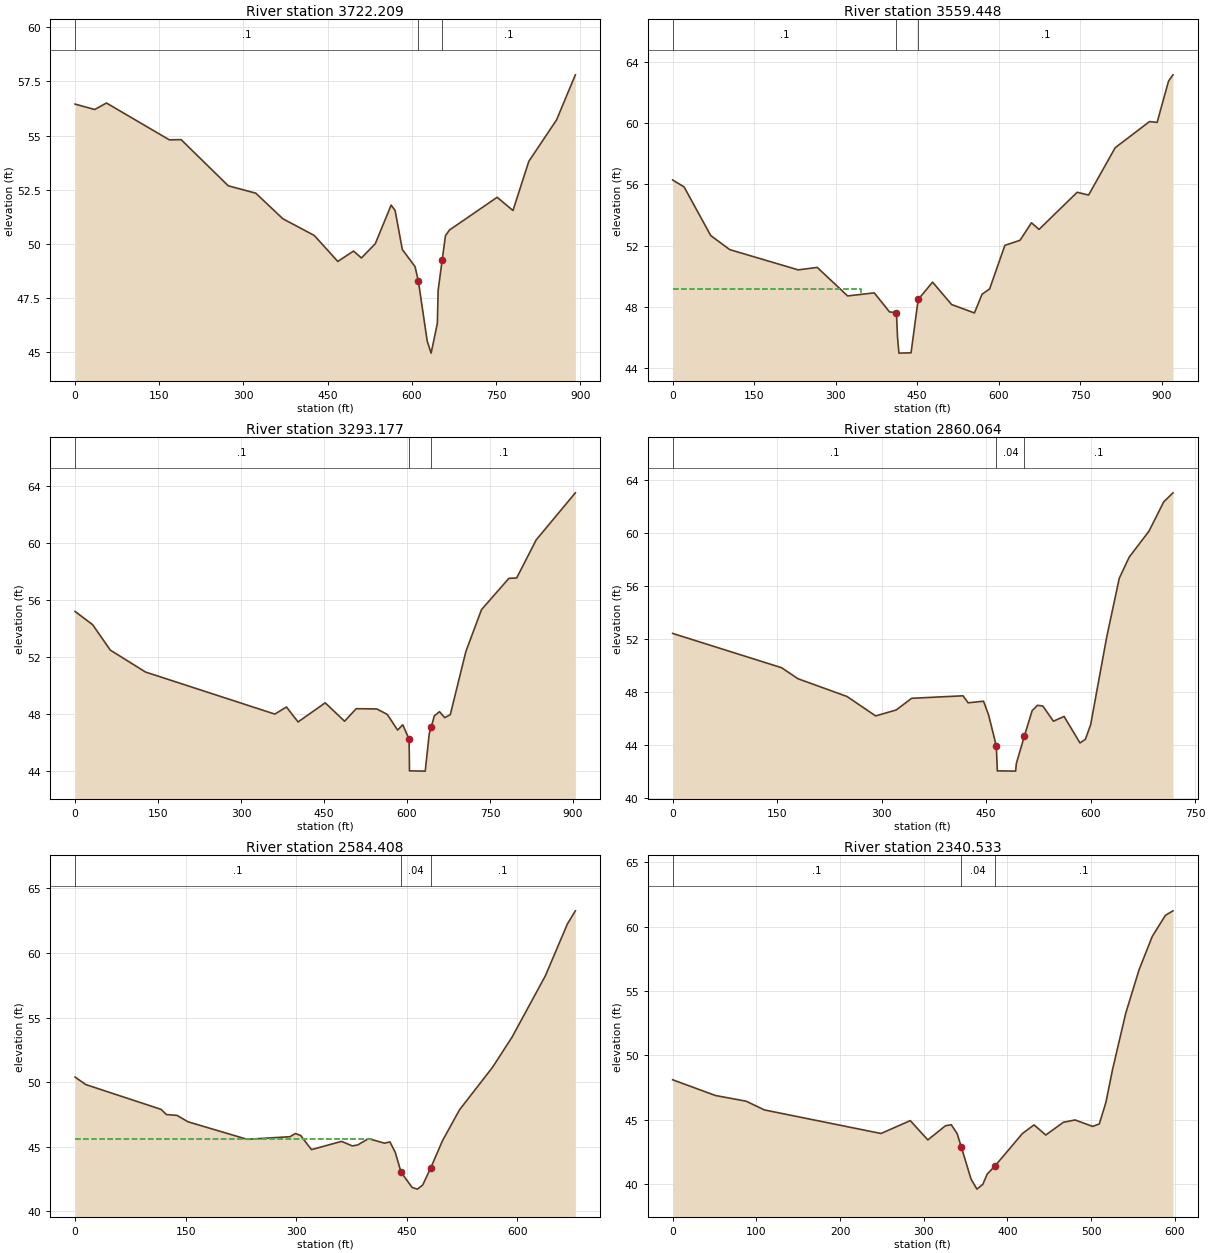
Type RM Length L Ch R = 1 ,3722.209,170.85,162.76,114.4
XS GIS Cut Line= 6
1630059.57500595716617.6049007771629524.59654406716616.451929972
1629484.18199925716611.253000274 1629455.7229996716601.527000442
1629410.30299954716593.0200004731629174.09341387716625.675696537
#Sta/Elev= 30
       0   56.45      35    56.2      56    56.5     168    54.8     189   54.81
     273   52.68     322   52.34  370.19   51.16  426.19   50.39  468.19   49.19
  496.19   49.67  510.19   49.35  534.98   50.01  563.21   51.79  570.27   51.54
  583.13   49.74   605.8   48.95  611.67   48.29  627.41   45.52  634.42   44.96
   645.5   46.33   646.9   47.85   654.1   49.26     660   50.38  667.11   50.64
  752.03   52.15  780.26   51.54   808.5   53.81  857.91   55.72  891.39    57.8
#Mann= 3 , 0 , 0
       0      .1       0  611.67     .04       0   654.1      .1       0
#XS Ineff= 2 , 0
          558.96   50.01
Permanent Ineff=
       F       F
Bank Sta=611.67,654.1
XS Rating Curve= 0 ,0
Exp/Cntr=0.3,0.1

Type RM Length L Ch R = 1 ,3559.448,210.59,266.27,196.19
XS GIS Cut Line= 6
1629905.33699991716448.1919994351629497.86499982716446.629999176
1629486.82900047716458.874000564 1629449.4069996716487.844999313
 1629295.5084624716484.6013537651629000.34793173716470.765703872
#Sta/Elev= 30
       0   56.29      21   55.84      70   52.67     105   51.75     231   50.43
     266   50.59     322   48.73     371   48.93     399   47.69  411.74   47.63
  413.79   46.02  416.39      45  438.67   45.02  451.79    48.5  478.29   49.63
  513.29   48.17   555.3   47.62  569.31   48.84  583.31   49.19  611.32   52.03
  639.23   52.36  660.26    53.5  674.27   53.07  744.35   55.49  765.37   55.31
  814.42    58.4  877.49    60.1  891.51   60.05  912.53   62.74   920.7   63.15
#Mann= 3 , 0 , 0
       0      .1       0  411.74     .04       0  451.79      .1       0
#XS Ineff= 2 , 0
          347.08   49.21
Permanent Ineff=
       F       F
Bank Sta=411.74,451.79
XS Rating Curve= 0 ,0
Exp/Cntr=0.3,0.1

Type RM Length L Ch R = 1 ,3293.177,254.62,433.11,412.26
XS GIS Cut Line= 6
1629901.34799962716320.7259998321629768.66099931716248.836000457
1629374.37299919716234.1830005651629310.71500018716290.961999893
1629275.13599972716322.2810001521629050.96500018716293.381000519
#Sta/Elev= 30
       0    55.2   31.85   54.27   63.69   52.49  127.38   50.95  361.06      48
  382.07    48.5  403.08   47.45  452.12   48.79  487.14    47.5  508.16   48.38
  545.47   48.36  564.23   47.98  582.98   46.88  592.36   47.25  603.64   46.24
  604.12    45.2  604.41   44.02  632.89      44   640.1   46.61  643.88   47.12
  649.42   47.88  658.75   48.17  668.07   47.75  678.17   47.96   706.4    52.4
  734.63   55.33  784.04   57.52  798.16   57.55  833.45   60.22   904.2   63.52
#Mann= 3 , 0 , 0
       0      .1       0  603.64     .04       0  643.88      .1       0
Bank Sta=603.64,643.88
XS Rating Curve= 0 ,0
Exp/Cntr=0.3,0.1

Type RM Length L Ch R = 1 ,2860.064,269.99,275.66,267.73
XS GIS Cut Line= 6
1629844.65351954716122.3710156981629616.78800015716008.979000106
1629412.59399989715941.1350002441629366.22400622715941.936419696
1629258.01799969715894.9069996031629174.95100026715881.183000565
#Sta/Elev= 30
       0    52.4  156.38   49.81  179.83   48.98   250.2   47.64   291.4   46.17
  320.91   46.62  343.03    47.5   416.8   47.69  424.17   47.16   446.3   47.28
  453.68   46.22  464.64   43.89  466.06   42.02  492.32      42  493.41   42.59
     505   44.66  516.07   46.57   523.7   46.97  531.34   46.92   546.6   45.77
  561.87   46.13  584.76   44.13   592.4    44.4  600.03    45.5  622.93   52.08
  641.15   56.57  655.34   58.16  683.72   60.12  705.01   62.34  718.25   63.02
#Mann= 3 , 0 , 0
       0      .1       0  464.64     .04       0     505      .1       0
Bank Sta=464.64,505
XS Rating Curve= 0 ,0
Exp/Cntr=0.3,0.1

Type RM Length L Ch R = 1 ,2584.408,257.37,243.88,189.87
XS GIS Cut Line= 6
1629879.93300058715803.8950004581629553.78199965715709.148000717
 1629440.8349991 715676.128999711629395.63800052715666.295999527
1629337.64999965715619.8610000611629243.57099915715583.587999359
#Sta/Elev= 30
       0   50.39   14.58   49.81  116.63   47.89  123.92   47.49   138.5   47.42
  153.08   46.93  233.26   45.57  291.58   45.77  298.86   46.02  306.15   45.86
  320.73   44.77  361.51   45.41   376.1   45.06  383.39   45.13  397.98   45.62
  419.86   45.27  427.15   45.37  434.44   44.55  442.23   43.02  457.31   41.84
  464.47   41.71  471.63   42.03  482.61   43.37  498.44   45.46   521.5   47.85
  566.34   51.15  592.86   53.49  637.87   58.22  667.88   62.25  678.68   63.27
#Mann= 3 , 0 , 0
       0      .1       0  442.23     .04       0  482.61      .1       0
#XS Ineff= 2 , 0
          405.37   45.62
Permanent Ineff=
       F       F
Bank Sta=442.23,482.61
XS Rating Curve= 0 ,0
Exp/Cntr=0.3,0.1

Type RM Length L Ch R = 1 ,2340.533,152.11,220.85,228.29
XS GIS Cut Line= 6
1629920.45299916715542.788999558 1629722.2339993715483.413000107
1629572.67700008 715484.878999711629553.54400066715487.749000549
 1629419.5559998715486.870000854 1629341.5300007715446.076999664
#Sta/Elev= 30
       0   48.11   51.15   46.89   87.69   46.45  109.61   45.77  248.92   43.94
  283.92   44.94  304.93   43.44  325.93   44.54  332.93   44.62  339.93   43.93
  344.73   42.93  356.49   40.41  363.56   39.62  370.64   39.99  375.83   40.79
  384.91    41.4  417.83   43.93  431.83   44.61  445.83   43.82  466.83   44.81
  480.83   44.99  501.83   44.49  509.82   44.68  517.72   46.36  525.62    48.9
  541.42   53.28  557.22   56.63  573.01   59.23  588.81   60.88  597.87   61.23
#Mann= 3 , 0 , 0
       0      .1       0  344.73     .04       0  384.91      .1       0
Bank Sta=344.73,384.91
XS Rating Curve= 0 ,0
Exp/Cntr=0.3,0.1