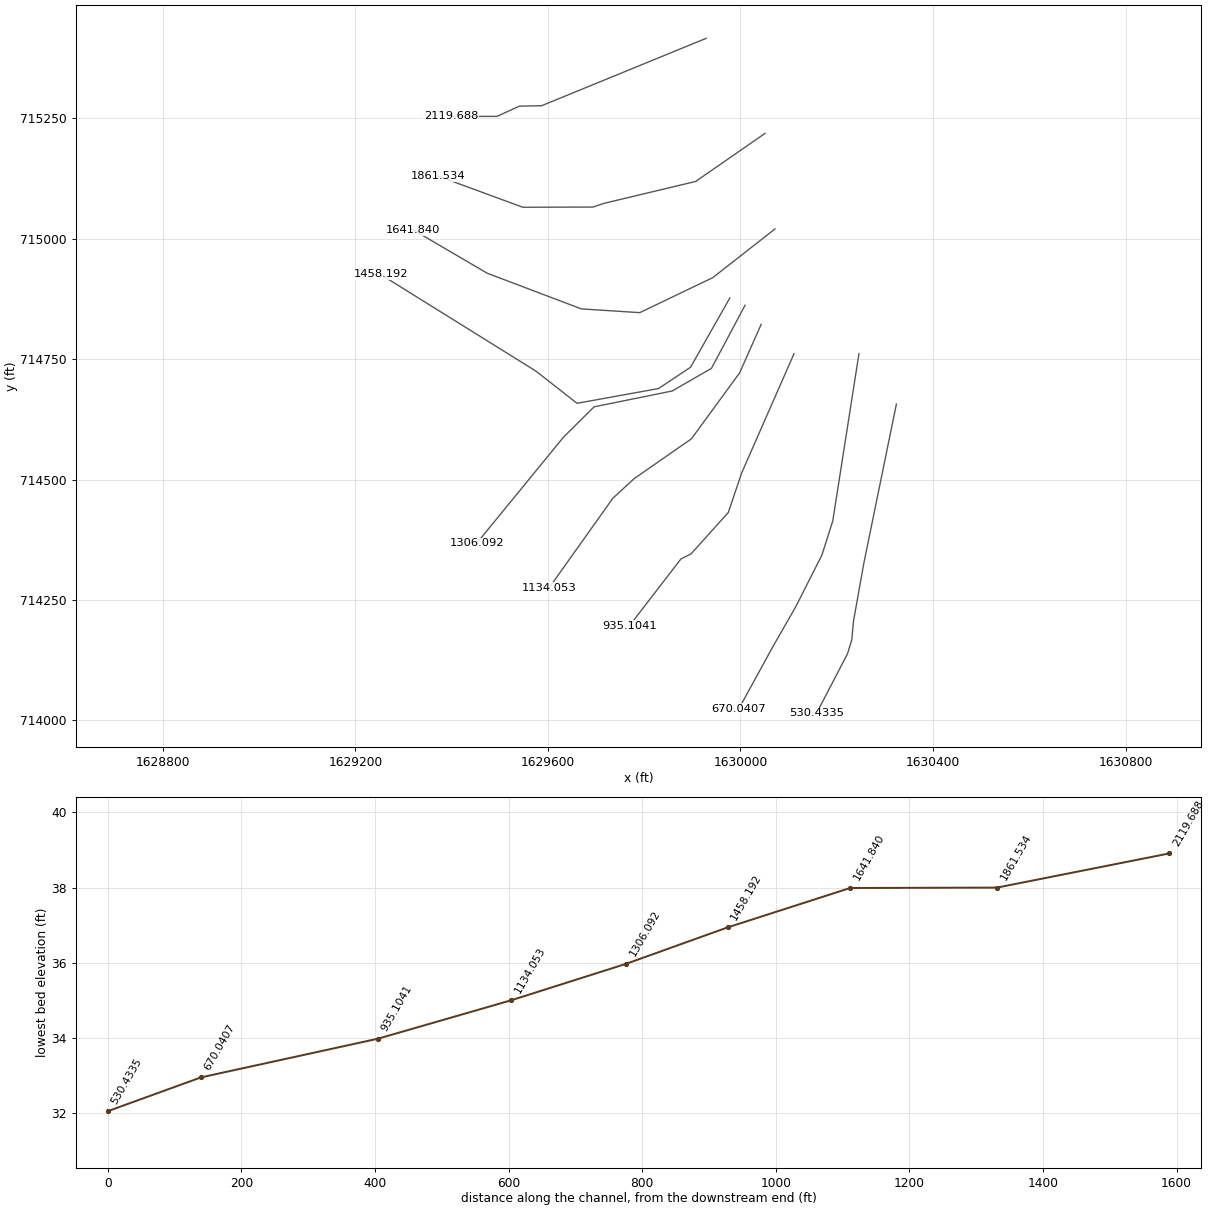
HEC-RAS study LaurelRun.prj: LaurelRun

--- LaurelRun.g02 (geometry) --- (continued)

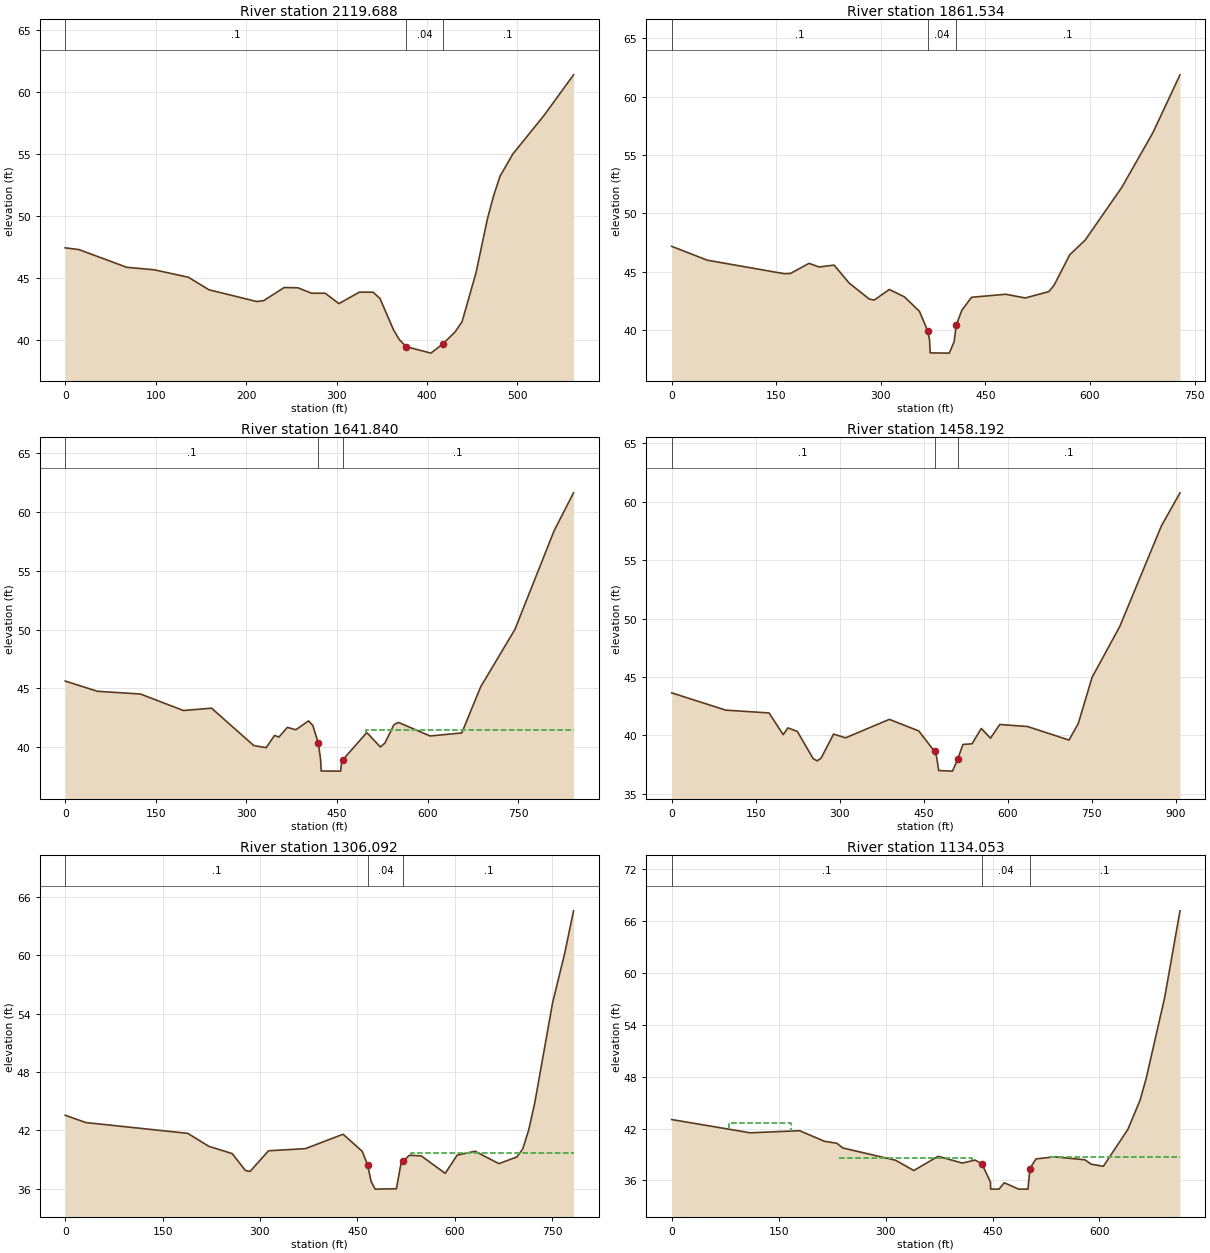
Type RM Length L Ch R = 1 ,2119.688,251.62,258.15,227.35
XS GIS Cut Line= 5
1629928.72999959715416.4330005651629586.98299982715276.465000153
1629540.65399939715275.5310001521629494.10400011 715254.26099968
1629398.94799997 715254.26099968
#Sta/Elev= 30
       0    47.4   15.13   47.26   68.08   45.83   98.34   45.63  136.16   45.03
  158.85   44.02   211.8   43.07  219.37   43.14  242.06    44.2  257.19   44.18
  272.32   43.74  287.45   43.74  302.57    42.9  325.27   43.83   340.4   43.82
  347.96   43.32  363.09   40.77   369.3   40.01  377.03   39.43  404.31   38.91
  417.15   39.63  431.03   40.62  438.73   41.44  454.12   45.38  466.82   49.75
  473.82   51.65  480.82   53.19  494.82   54.96  529.82   58.12  561.97   61.35
#Mann= 3 , 0 , 0
       0      .1       0  377.03     .04       0  417.15      .1       0
Bank Sta=377.03,417.15
XS Rating Curve= 0 ,0
Exp/Cntr=0.3,0.1

Type RM Length L Ch R = 1 ,1861.534,240.1,219.69,181.07
XS GIS Cut Line= 6
1630051.02400017715218.9510002141629906.85300064715119.093999878
1629716.48699951715073.6410007631629693.79400067 715065.93000032
1629547.84199907715065.548000351 1629371.4009991715130.445999146
#Sta/Elev= 30
       0   47.16   51.09   45.97  161.79   44.81   170.3   44.83  196.97    45.7
  211.36   45.39  232.95   45.55  254.54   44.01  283.33   42.64  290.52   42.55
  312.11   43.46   333.7   42.83   355.3   41.59  367.42   39.87  369.84   39.13
  370.72   38.02  398.14      38  405.07   38.98  408.03   40.37  416.06   41.67
  430.06   42.79  479.06   43.05  507.06   42.73  541.01   43.28  548.47   43.83
  570.85   46.43  593.22   47.71  645.43   52.21  690.18   56.91  729.01   61.87
#Mann= 3 , 0 , 0
       0      .1       0  367.42     .04       0  408.03      .1       0
Bank Sta=367.42,408.03
XS Rating Curve= 0 ,0
Exp/Cntr=0.3,0.1

Type RM Length L Ch R = 1 ,1641.840,167.17,183.65,139.37
XS GIS Cut Line= 6
1630071.85899927715020.5629997251629942.25399973714919.156999603
1629790.79700089714846.5949993131629669.45899968714854.423000336
1629474.08300023714928.4449996951629320.40500069715018.436000839
#Sta/Elev= 30
       0   45.63   53.33   44.76  124.43   44.53  195.61   43.13  242.18   43.33
  312.04   40.16   332.5   39.98  346.56   41.02  353.59   40.87  367.64    41.7
   381.7    41.5  402.78   42.25  409.81   41.86  419.02   40.34  422.64   38.97
  423.66      38  455.92   37.99  456.93   38.57  459.39   38.95  499.12   41.26
  521.58   40.04  529.07   40.37  544.04   41.93  551.52   42.12  603.92   40.97
  656.32   41.23  687.48   45.13  744.26   50.01  809.15   58.38  841.23   61.59
#Mann= 3 , 0 , 0
       0      .1       0  419.02     .04       0  459.39      .1       0
#XS Ineff= 2 , 0
          391.18   41.26  498.56            41.5
Permanent Ineff=
       F       F
Bank Sta=419.02,459.39
XS Rating Curve= 0 ,0
Exp/Cntr=0.3,0.1

Type RM Length L Ch R = 1 ,1458.192,13,152.1,303.14
XS GIS Cut Line= 6
1629978.03400041714877.2189998781629896.34900099714733.232999802
1629829.89399914 714688.930000321629660.51399998714658.287000656
1629575.03300101714725.2280006411629252.68300061714925.875999466
#Sta/Elev= 30
       0   43.64   96.58   42.16  173.96   41.92  199.19   40.06  207.61   40.64
  224.43   40.34  252.54   38.02  259.66   37.82  266.79   38.04  289.23   40.11
  310.56   39.79  388.79   41.37  441.32   40.38  469.68   38.62  473.03    38.2
     477   36.99  501.56   36.94  510.81   37.95  520.15   39.22  536.49   39.28
  552.98   40.59  569.47   39.76  585.96   40.93  635.43   40.76  709.64    39.6
  726.13      41  750.87   44.96  800.34   49.32  874.55   57.91  907.94   60.76
#Mann= 3 , 0 , 0
       0      .1       0  469.68     .04       0  510.81      .1       0
#XS Ineff= 2 , 0
          389.26   40.71  604.03            40.4
Permanent Ineff=
       F       F
Bank Sta=469.68,510.81
XS Rating Curve= 0 ,0
Exp/Cntr=0.3,0.1

Type RM Length L Ch R = 1 ,1306.092,137.56,172.04,161.8
XS GIS Cut Line= 6
1630009.54299927714861.9039993441629939.79199985714730.906999603
1629858.13200001714683.8390007171629695.94599918714650.948999405
1629632.43300058714588.0020008241629452.31249438714367.746922672
#Sta/Elev= 30
       0   43.56   31.72   42.81  188.81    41.7  221.13   40.37  257.27   39.62
  277.59   37.88  284.71   37.79  313.18   39.91  370.12   40.13     428   41.61
  457.56   39.85  465.85   38.43   471.2   36.75  477.45   35.97  510.12   36.01
  516.83   38.47  520.95   38.88  530.14   39.45  548.53   39.38  585.29   37.59
  603.68   39.46  631.26   39.86  668.03   38.59   695.6   39.27  704.79   40.11
  713.99   42.07  723.18   44.81  750.76   55.13  769.14   60.13  782.95   64.56
#Mann= 3 , 0 , 0
       0      .1       0  465.85     .04       0  520.95      .1       0
#XS Ineff= 2 , 0
          415.72    39.6  533.08           39.66
Permanent Ineff=
       F       F
Bank Sta=465.85,520.95
XS Rating Curve= 0 ,0
Exp/Cntr=0.3,0.1

Type RM Length L Ch R = 1 ,1134.053,168.65,198.95,186.37
XS GIS Cut Line= 6
1630043.00099951714822.208000183 1629998.2989998714721.520000473
1629898.12787928714584.5054374041629778.56100085714501.297000885
1629734.96199991714461.0919990691629602.96734855 714275.50925681
#Sta/Elev= 30
       0   43.04  110.17   41.51  179.54   41.75  214.22   40.53  231.56    40.3
  240.23   39.75  314.01   38.34  339.59   37.15   373.7   38.79  407.82   38.01
  425.56   38.36  435.17   37.91   447.2    35.8  447.23   35.23  447.48      35
  459.16      35  466.39   35.74   486.6      35  499.76      35  502.37   37.37
  510.96   38.49  536.73   38.73  579.68   38.39  588.27   37.88  605.45   37.64
  639.81    41.9  656.99   45.29  665.58   47.82  691.35   57.11  712.93   67.16
#Mann= 3 , 0 , 0
       0      .1       0  435.17     .04       0  502.37      .1       0
#XS Ineff= 3 ,-1
   80.54  167.21   42.66  234.72  421.0938.65317  530.01  712.93   38.72
Permanent Ineff=
       F       F       F
Bank Sta=435.17,502.37
XS Rating Curve= 0 ,0
Exp/Cntr=0.3,0.1

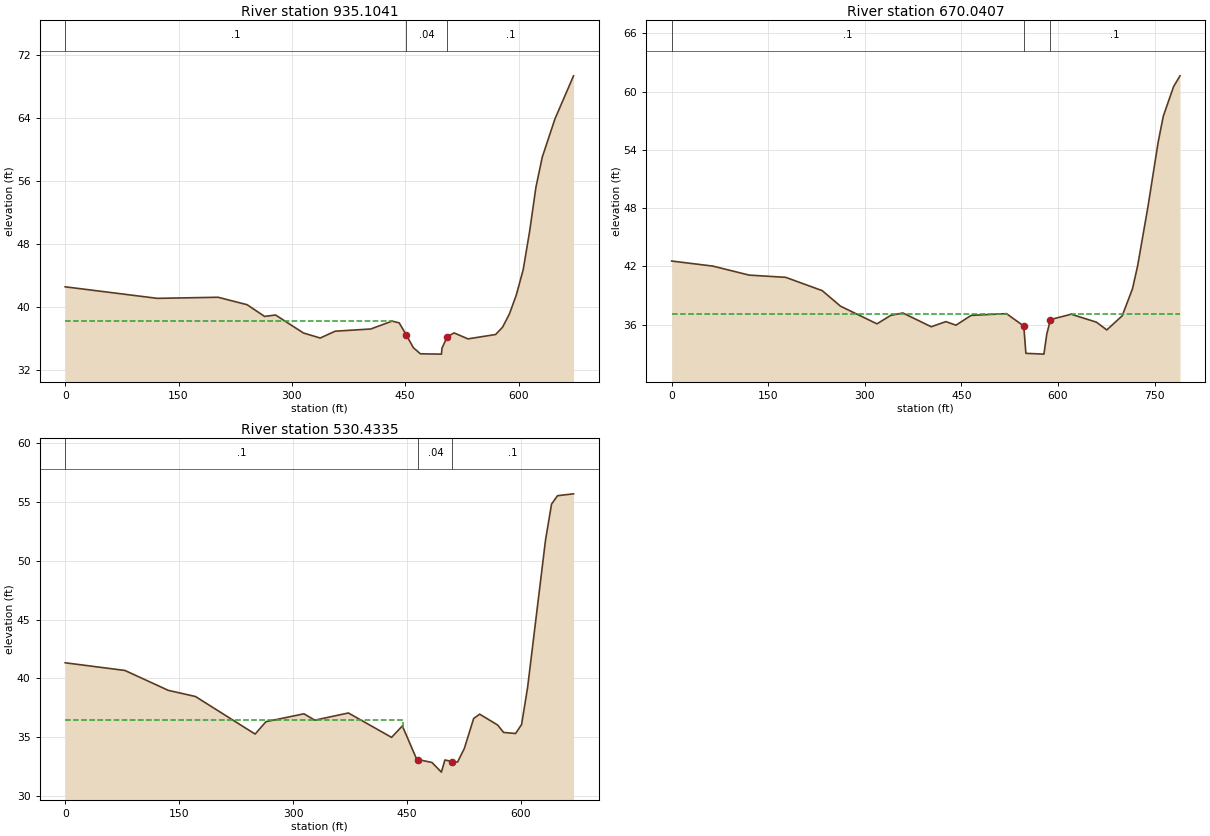
Type RM Length L Ch R = 1 ,935.1041,216.34,265.06,264.54
XS GIS Cut Line= 6
1630111.28499991 714761.448999421630002.39399914714513.298000336
1629974.77199939714431.5380001221629897.54199988714345.663000122
1629876.42000009714335.0499992371629768.99514708714195.569946453
#Sta/Elev= 30
       0   42.55  121.88   41.08   202.3   41.22  240.79   40.27  263.89   38.78
   278.4   38.96  315.34   36.67  337.51   36.03  357.31    36.9  404.38   37.18
  432.62   38.18  442.04   37.96  451.45   36.42  460.76    34.8  470.15   34.02
  498.02   33.98  498.62   34.72  505.59   36.19  514.74   36.68  533.04   35.92
  569.64   36.48  578.79    37.4  587.94    39.1  597.09   41.52  606.19   44.75
  614.59   49.57  622.98   55.21  631.38   59.06  648.16   63.92  672.77   69.41
#Mann= 3 , 0 , 0
       0      .1       0  451.45     .04       0  505.59      .1       0
#XS Ineff= 2 , 0
          433.56   38.18
Permanent Ineff=
       F       F
Bank Sta=451.45,505.59
XS Rating Curve= 0 ,0
Exp/Cntr=0.3,0.1

Type RM Length L Ch R = 1 ,670.0407,94.09,139.61,145.53
XS GIS Cut Line= 6
1630246.17200089714761.315000534 1630191.7511155714413.865755573
1630169.30200008714343.2560005341630115.36100008714236.586000457
1630066.42600062714151.1200008541629996.51472282714023.392970175
#Sta/Elev= 30
       0   42.54   63.77   42.02  120.45   41.09  177.13   40.86  233.82   39.49
  262.16   37.89  318.84   36.07   340.1   36.94  359.03   37.19   403.1   35.77
  425.78    36.3  441.47   35.93     465   36.94  519.91   37.12  546.82   35.84
  550.07   33.03  578.07   32.95  582.53   35.02  588.2636.51119  620.49   37.06
  659.75   36.24  675.71   35.44  699.65    36.9  715.61   39.68  723.59   42.04
  739.55    48.1  755.51    54.8  763.49   57.47  779.45   60.51   789.4   61.62
#Mann= 3 , 0 , 0
       0      .1       0  546.82     .04       0  588.26      .1       0
#XS Ineff= 2 , 0
          521.57   37.09  618.98           37.09
Permanent Ineff=
       F       F
Bank Sta=546.82,588.26
XS Rating Curve= 0 ,0
Exp/Cntr=0.3,0.1

Type RM Length L Ch R = 1 ,530.4335,120.52,118.39,71.53
XS GIS Cut Line= 6
1630323.95843659714656.7582756281630256.31748161714326.239973024
1630234.81500055714205.6030006411630231.21100046714166.693000808
1630222.32799916714137.8460006711630157.93063807714014.169203609
#Sta/Elev= 30
       0   41.33    78.6   40.68  135.76   38.99  171.48   38.47  250.08   35.28
  264.37   36.33  314.38      37  328.67   36.46  372.91   37.07  429.78      35
  443.99   35.97   462.5    33.2  465.24   33.11  482.92   32.87  495.39   32.05
  500.02   33.08  509.75   32.94  516.61    32.9  525.62   34.06  537.86    36.6
  545.75   36.97  569.43   36.05  577.32   35.42   593.1   35.33     601   36.09
  608.89   39.22  632.56   51.77  640.46    54.8  648.35   55.51   669.4   55.67
#Mann= 3 , 0 , 0
       0      .1       0  465.24     .04       0  509.75      .1       0
#XS Ineff= 2 , 0
          444.97    36.5  546.31           36.38
Permanent Ineff=
       F       F
Bank Sta=465.24,509.75
XS Rating Curve= 0 ,0
Exp/Cntr=0.3,0.1