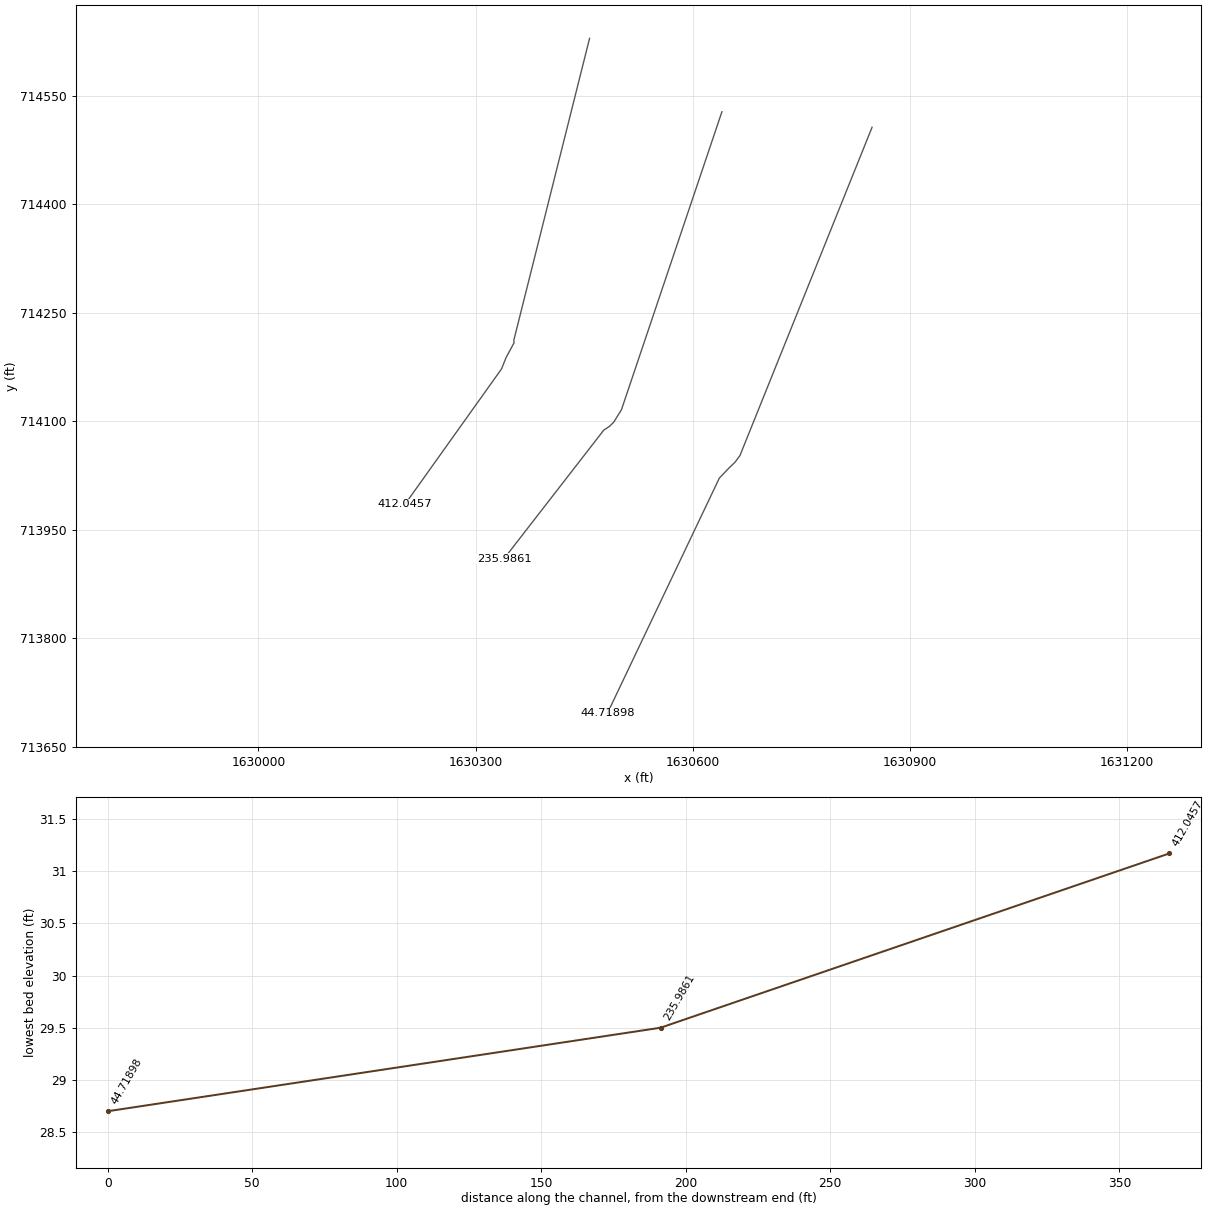
HEC-RAS study LaurelRun.prj: LaurelRun

--- LaurelRun.g02 (geometry) --- (continued)

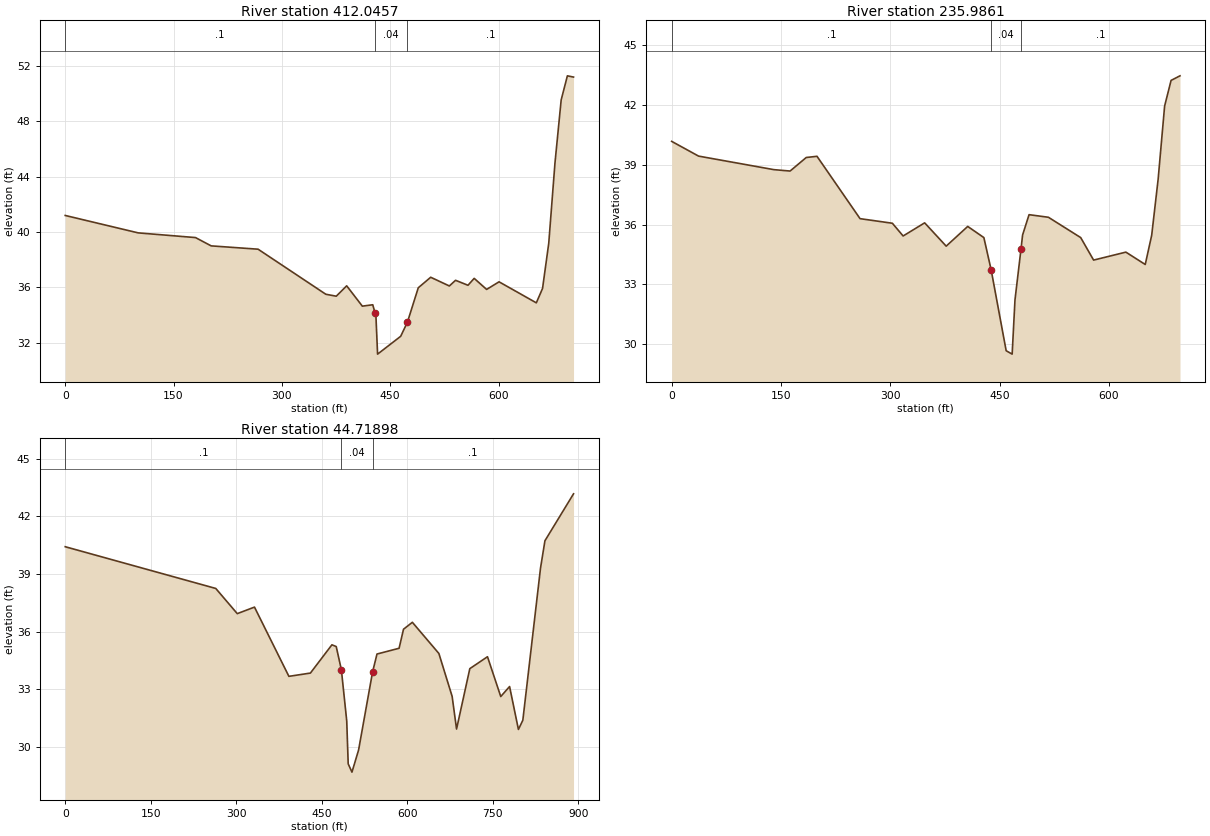
Type RM Length L Ch R = 1 ,412.0457,178.38,176.06,161.03
XS GIS Cut Line= 6
1630457.70305206714629.0869758731630352.98900037714211.827999115
1630353.20899965714208.0540008691630342.29100037714187.865999222
1630336.05299954714172.2010002291630202.51217654713984.960609406
#Sta/Elev= 30
       0    41.2  101.04   39.94  180.43    39.6  202.08      39  267.03   38.76
  360.85    35.5  375.29   35.36  389.72   36.11  411.37   34.64  425.81   34.74
  429.09   34.13   430.2   33.93   432.5   31.17  464.48   32.46  473.79   33.48
  488.83   35.97  506.03   36.73  531.84    36.1  540.44   36.51  557.65   36.15
  566.25   36.65  583.45   35.85  600.66    36.4  652.27   34.88  660.88   35.92
  669.48   39.19  678.08   44.99  686.68   49.56  695.28    51.3  703.78   51.21
#Mann= 3 , 0 , 0
       0      .1       0  429.09     .04       0  473.79      .1       0
#XS Ineff= 2 , 0
          388.88   35.83   504.7           36.24
Permanent Ineff=
       F       F
Bank Sta=429.09,473.79
XS Rating Curve= 0 ,0
Exp/Cntr=0.3,0.1

Type RM Length L Ch R = 1 ,235.9861,185.32,191.27,200.85
XS GIS Cut Line= 6
1630640.64108928714527.6255434451630501.79100037714115.820999146
1630491.03400043714098.4050006871630485.17300037714092.733999252
1630477.27400017714087.4540004881630339.42746176713909.777303696
#Sta/Elev= 30
       0   40.18   36.94   39.44  140.36   38.76  162.52   38.69  184.68   39.37
  199.45   39.43  258.55    36.3  302.88   36.07  317.65   35.43   347.2   36.09
  376.75   34.92   406.3   35.91  428.46   35.35  438.46   33.73  459.07   29.67
  467.29    29.5  471.16   32.22  479.48   34.79  481.61   35.48  490.47    36.5
  517.05   36.37  561.35   35.35  579.07   34.22  623.36   34.62  649.94      34
   658.8   35.47  667.66   38.29  676.52   41.95  685.38   43.24  697.63   43.47
#Mann= 3 , 0 , 0
       0      .1       0  438.46     .04       0  479.48      .1       0
#XS Ineff= 2 , 0
                          507.38           35.17
Permanent Ineff=
       F       F
Bank Sta=438.46,479.48
XS Rating Curve= 0 ,0
Exp/Cntr=0.3,0.1

Type RM Length L Ch R = 1 ,44.71898,55.98,44.72,39.52
BEGIN DESCRIPTION:
End of Detailed Reach
END DESCRIPTION:
XS GIS Cut Line= 6
1630848.17583744714506.103421435 1630665.5919991714052.406999588
1630658.70999911714043.0919990691630650.38699916714035.100999847
1630637.08600046714021.236000061 1630482.2997629 713695.94925645
#Sta/Elev= 30
       0   40.42   264.1   38.25  301.82   36.94  332.01   37.28  392.37   33.68
   430.1   33.85  467.83   35.32  475.37   35.23  484.43   34.02  493.83   31.36
  496.39   29.13  502.99    28.7  514.61   29.85  539.16   33.91  546.91   34.84
  585.67   35.14  593.42   36.13  608.93   36.49  655.44   34.87   678.7   32.64
  686.45   30.94  709.71   34.08  740.71    34.7  763.97   32.63  779.47   33.15
  794.98   30.92  802.73    31.4  833.74   39.31  841.49   40.73  891.64   43.17
#Mann= 3 , 0 , 0
       0      .1       0  484.43     .04       0  539.16      .1       0
#XS Ineff= 2 , 0
                          599.23           34.28
Permanent Ineff=
       F       F
Bank Sta=484.43,539.16
XS Rating Curve= 0 ,0
Exp/Cntr=0.3,0.1

Chan Stop Cuts=-1
Use User Specified Reach Order=0