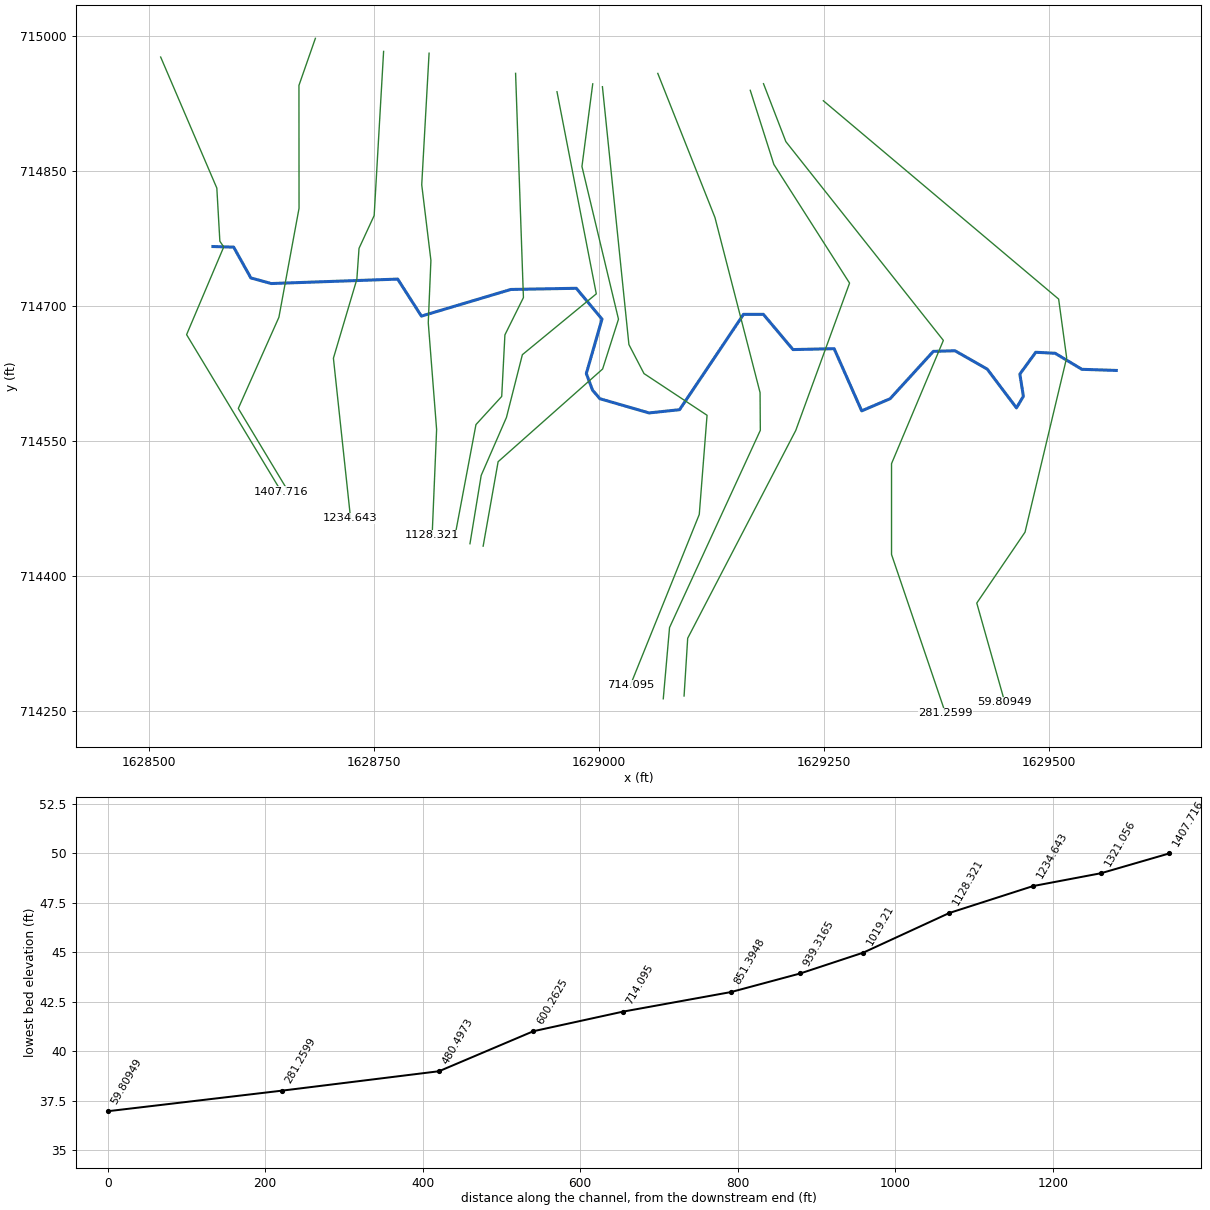
--- LaurelRunTrib.prj (project) ---

Proj Title=Laurel Run Trib
Current Plan=p01
Default Exp/Contr=0.3,0.1
English Units
Geom File=g01
Flow File=f01
Flow File=f02
Plan File=p01
Plan File=p02
Y Axis Title=Elevation
X Axis Title(PF)=Main Channel Distance
X Axis Title(XS)=Station
BEGIN DESCRIPTION:
Unnamed Trib to Laurel Run - Cecil County, MD.  Georeferenced HEC-RAS model.
Maryland Stateplain.  Horizontal datum NAD 83.  Vertical Datum NAVD88.  Units: Feet
Created by Andy Richter, USACE - St. Louis District, as a part of a FEMA Map Modernization Study for Cecil County.
NOTE - this stream was included in a LOMR, 06-03-B926P.  It was not included in the original FIS.  The entire stream was modeled using Detailed Stream methods.  Flow values were taken directly from the LOMR.
END DESCRIPTION:
DSS File=dss
DSS Export Rating Curves= 0
DSS Export Rating Curve Sorted= 0
DSS Export Volume Flow Curves= 0
DXF OffsetX= 0
DXF OffsetY= 0
DXF ScaleX= 1
DXF ScaleY= 10

--- LaurelRunTrib.p01 (plan) ---

Plan Title=Laurel Run Trib Frequency Profiles
Program Version=4.00
Short Identifier=Laurel Run T
Geom File=g01
Flow File=f01
Subcritical Flow
K Sum by GR= 0
Std Step Tol= 0.01
Critical Tol= 0.01
Num of Std Step Trials= 20
Max Error Tol= 0.3
Flow Tol Ratio= 0.001
Split Flow NTrial= 30
Split Flow Tol= 0.02
Split Flow Ratio= 0.02
Log Output Level= 0
Friction Slope Method= 1
Unsteady Friction Slope Method= 2
Unsteady Bridges Friction Slope Method= 1
Parabolic Critical Depth
Global Vel Dist= 0 , 0 , 0
Global Log Level= 0
CheckData=True
Encroach Param=-1 ,0,0, 0
BEGIN DESCRIPTION:
Flows taken directly from LOMR
Boundary Condition - normal depth slope - adjusted per engineers judgement
END DESCRIPTION:
Computation Interval=1HOUR
Output Interval=1HOUR
Run HTab= 0
Run UNet= 0
Run PostProcess= 0
Run WQNet= 0
UNET Theta= 1
UNET Theta Warmup= 1
UNET ZTol= 0.02
UNET ZSATol= 0.05
UNET MxIter= 20
UNET MaxInSteps= 0
UNET DtIC= 0
UNET DtMin= 0
UNET MaxCRTS= 20
UNET WFStab= 2
UNET SFStab= 1
UNET WFX= 1
UNET SFX= 1
UNET DSS MLevel= 4
UNET DZMax Abort= 100
UNET Convert EG Bridges= 0
UNET Use Existing IB Tables=-1
UNET Froude Reduction=False
UNET Froude Limit= 1
UNET Froude Power= 10
UNET Time Slicing=0,0, 5
Instantaneous Interval=1HOUR
DSS File=dss
Write IC File= 0
Echo Input=False
Echo Output=False
Write Detailed= 0
Detailed Automatic Start=False, 10
WQ ULTIMATE=-1
WQ Max Comp Step=1HOUR
WQ Output Interval=15MIN
WQ Output Selected Increments= 0
WQ Output face flow=0
WQ Output face velocity=0
WQ Output face area=0
WQ Output face dispersion=0
WQ Output cell volume=0
WQ Output cell surface area=0
WQ Output cell continuity=0
WQ Output face conc=0
WQ Output face dconc_dx=0
WQ Output face courant=0
WQ Output face peclet=0
WQ Output face adv mass=0
WQ Output face disp mass=0
WQ Output cell mass=0
WQ Output cell source sink temp=0
WQ Output cell source sink nsm=0
WQ Output MaxMinRange=-1
WQ Daily Max Min Mean=-1
WQ Daily Range=0
WQ Daily Time=0
WQ Create Restart=0
WQ Fixed Restart=0
WQ System Summary=False
Sorting and Armoring Iterations= 10
XS Update Threshold= 0.02
Hydraulics Update Threshold= 0.02
Energy Slope Method= 1
Volume Change Method= 0
XS Weighting Method= 0
Number of US Weighted Cross Sections= 1
Number of DS Weighted Cross Sections= 1
Upstream XS Weight=0.25
Main XS Weight=0.5
Downstream XS Weight=0.25
Number of DS XS's Weighted with US Boundary= 1
Upstream Boundary Weight= 1
Weight of XSs Associated with US Boundary= 0
Number of US XS's Weighted with DS Boundary= 1
Downstream Boundary Weight= 0.5
Weight of XSs Associated with DS Boundary= 0.5
Sediment Output Level= 4
Mass or Volume Output= 0
Output Increment Type= 1
Profile and TS Output Increment= 10
XS Output Flag= 0
XS Output Increment= 10
Disregard all LS=0
Disregard all Conn=0
Disregard all Breaches=0
Disregard all Pumps=0

--- LaurelRunTrib.p02 (plan) ---

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Plan Title=Laurel Run Trib Floodway
Short Identifier=floodway
Geom File=g01
Flow File=f02
Encroach Param=-1 ,0,0, 2
Encroach River=Laurel Run Trib
Encroach Reach=Herron
Encroach Node=1407.716
       4       1
Encroach Node=1321.056
       4       1
Encroach Node=1234.643
       4       1
Encroach Node=1128.321
       4       1
Encroach Node=1019.21
       4       1
Encroach Node=939.3165
       4       1
Encroach Node=851.3948
       4       1
Encroach Node=714.095
       4       1
Encroach Node=600.2625
       1     276     297
Encroach Node=480.4973
       4       1
Encroach Node=281.2599
       4       1
Encroach Node=59.80949
       4       1

--- LaurelRunTrib.f01 (steady flow) ---

Flow Title=Laurel Run Trib Frequency Flows
Program Version=4.00
Number of Profiles= 4
Profile Names=10yr,50yr,100yr,500yr
River Rch & RM=Laurel Run Trib,Herron          ,1407.716
      74     140     176     284
Boundary for River Rch & Prof#=Laurel Run Trib,Herron          , 1
Up Type= 0
Dn Type= 3
Dn Slope=0.0044
Boundary for River Rch & Prof#=Laurel Run Trib,Herron          , 2
Up Type= 0
Dn Type= 3
Dn Slope=0.0044
Boundary for River Rch & Prof#=Laurel Run Trib,Herron          , 3
Up Type= 0
Dn Type= 3
Dn Slope=0.0044
Boundary for River Rch & Prof#=Laurel Run Trib,Herron          , 4
Up Type= 0
Dn Type= 3
Dn Slope=0.0044
DSS Import GetInterval= 0
DSS Import GetPeak= 0
DSS Import FillOption= 0

--- LaurelRunTrib.f02 (steady flow) ---

Flow Title=Laurel Run Trib Encroached Flows
Program Version=4.00
Number of Profiles= 2
Profile Names=100yr,100yrenc
River Rch & RM=Laurel Run Trib,Herron          ,1407.716
     176     176
Boundary for River Rch & Prof#=Laurel Run Trib,Herron          , 1
Up Type= 0
Dn Type= 1
Dn Known WS=39.49
Boundary for River Rch & Prof#=Laurel Run Trib,Herron          , 2
Up Type= 0
Dn Type= 1
Dn Known WS=40.49
DSS Import GetInterval= 0
DSS Import GetPeak= 0
DSS Import FillOption= 0

--- LaurelRunTrib.g01 (geometry) ---

Geom Title=Laurel Run Trib Geometry
Program Version=4.00
BEGIN GEOM DESCRIPTION:
Overbanks taken from Cecil Co GRID, channel taken from LOMR HEC-RAS model
END GEOM DESCRIPTION:

River Reach=Laurel Run Trib ,Herron
Reach XY= 30
1628570.82116242714766.1031761021628593.85274841 714765.44513081
1628612.93606254714731.2267744691628635.63862585714724.975343987
1628776.13130039714729.9106838411628802.45311296714688.782851726
 1628901.8179554 714718.39489086 1628974.5319626714719.710981473
1629003.15693372714685.4926251621628985.71873291714624.952456251
1628992.62820871714606.5271874821629000.85377511714596.985530406
1629055.47153619714581.1924428791629089.36086987714584.811692119
1629160.42976379714690.756987661 1629182.4742818714690.756987661
 1629215.3765475714651.6032914671629261.11069684714652.590359464
1629291.70980391714583.4956014751629323.29597901714596.985530406
1629371.33328691714649.6291555461629395.35194086714650.287200838
1629431.21541047714629.8877961041629463.70061424714586.780687064
1629471.40437134714599.6896853751629467.44838794 714624.36252892
1629485.14620824714648.6189531531629506.69590701714647.473800078
1629536.36578216714629.6718750151629574.65377715714628.408411905

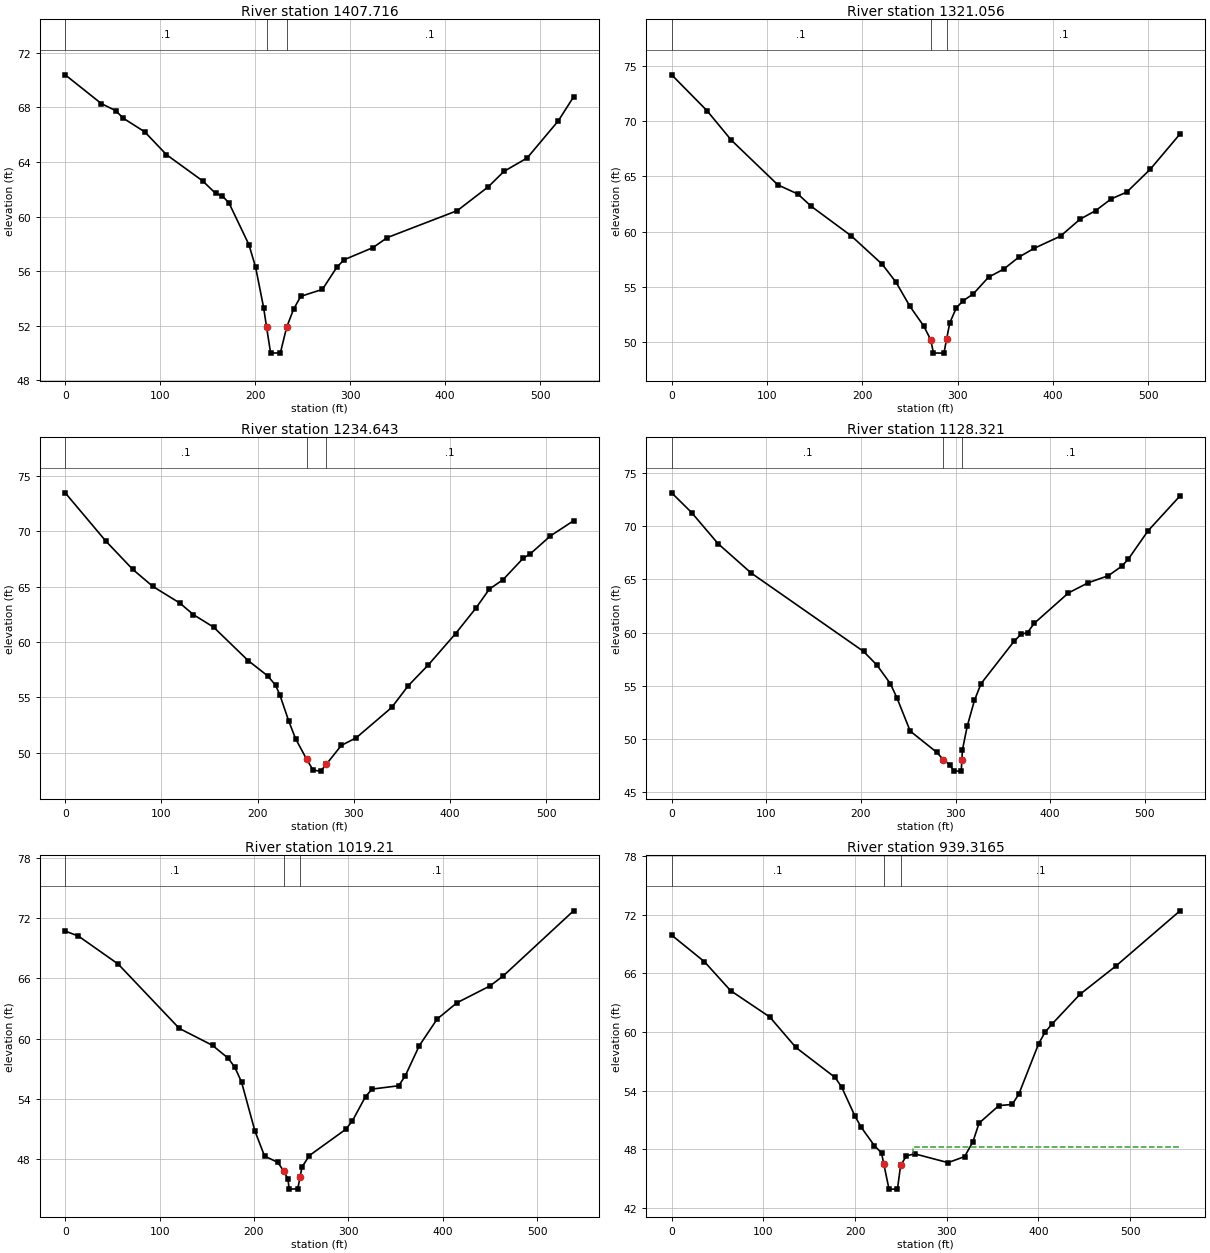
Type RM Length L Ch R = 1 ,1407.716,86.51,86.66,80.49
BEGIN DESCRIPTION:
Section C
END DESCRIPTION:
XS GIS Cut Line= 6
1628512.72800064 714976.676000611628575.14100078714831.045999542
1628578.52000047714771.9559993741628582.84399988714765.714000702
1628541.54800038714668.1849994811628647.01899911714493.385000244
#Sta/Elev= 30
       0   70.39   38.08   68.28   53.31   67.76   60.93   67.22   83.77   66.21
  106.62   64.54   144.7   62.62  158.44    61.7  165.45   61.52  172.46      61
   193.5   57.94  200.51   56.29  208.92   53.34  212.11   51.88  216.31      50
   226.6   50.02  233.17   51.89  240.42   53.21  248.03   54.16  270.83   54.67
  286.03   56.29  293.64   56.84  324.04   57.73  339.31   58.47  412.89   60.44
  445.59   62.19  461.94   63.31  486.47    64.3  519.17   67.01  535.29   68.77
#Mann= 3 , 0 , 0
       0      .1       0  212.11     .04       0  233.17      .1       0
Bank Sta=212.11,233.17
XS Rating Curve= 0 ,0
Exp/Cntr=0.3,0.1

Type RM Length L Ch R = 1 ,1321.056,80.79,86.41,80.42
XS GIS Cut Line= 6
1628684.65200047714997.4510002141628666.39699937714945.177999511
1628666.49600032714808.5760002291628644.11800003714687.489000335
1628598.99799919714586.1900005341628653.07699969714496.413999558
#Sta/Elev= 30
       0   74.21   37.07   70.96   62.37   68.31  111.37   64.24  132.37   63.41
  146.37    62.3  188.37   59.62  220.92   57.04  235.39   55.41  249.86   53.24
  264.33   51.46  271.63   50.22  274.56   49.01  285.53      49  288.29   50.24
  291.65   51.74  298.66   53.12  305.67   53.74  316.38   54.37  332.31   55.88
  348.23   56.61  364.16    57.7  380.09   58.49  407.81    59.6  428.32   61.13
  444.66   61.91  461.01   62.97  477.35   63.59  501.87   65.65  533.13   68.85
#Mann= 3 , 0 , 0
       0      .1       0  271.63     .04       0  288.29      .1       0
Bank Sta=271.63,288.29
XS Rating Curve= 0 ,0
Exp/Cntr=0.3,0.1

Type RM Length L Ch R = 1 ,1234.643,86.26,106.32,93.38
XS GIS Cut Line= 6
1628760.46400072714982.9279994961628749.97100067714800.548999786
1628733.15299992714764.0839996491628730.74500084714729.746999741
1628704.69100003714641.9850006251628723.76199916714464.100999832
#Sta/Elev= 30
       0   73.46   42.07   69.12   70.12   66.56   91.15   65.01   119.2   63.51
  133.22   62.47  154.25   61.34  190.07   58.33  210.48   56.94   218.6   56.11
  223.05   55.24  232.41   52.85  239.41   51.28  251.02   49.41  257.74   48.43
  265.57   48.35  271.31   48.96  287.03   50.67  302.53   51.36  339.43    54.1
  356.48   56.05   377.6   57.95  405.76   60.76  426.88   63.06  440.96   64.78
  455.04   65.62  476.16   67.57   483.2   67.94  504.32   69.57  528.35   70.94
#Mann= 3 , 0 , 0
       0      .1       0  251.02     .04       0  271.31      .1       0
Bank Sta=251.02,271.31
XS Rating Curve= 0 ,0
Exp/Cntr=0.3,0.1

Type RM Length L Ch R = 1 ,1128.321,99.19,109.11,93.08
XS GIS Cut Line= 6
1628810.99500084714980.9400005341628802.83399966714834.722999588
1628813.03000072714750.6849994661628810.09000018714681.486000061
1628819.36000064714562.8090000151628814.39500047 714445.04000093
#Sta/Elev= 30
       0   73.13   21.03   71.28   49.08   68.35   84.13   65.59  202.86   58.23
  216.96   56.95   231.1   55.21  238.11   53.87  252.12   50.75  280.14   48.76
  287.15   48.07  294.16   47.57  298.27   46.99  306.07      47  306.72   48.01
  307.36      49  312.43   51.22     320   53.63  327.02   55.21  362.12   59.21
  369.14   59.83  376.16   60.01  383.18   60.87  419.42   63.73  440.44   64.69
  461.45   65.34  475.47   66.22  482.47   66.88  503.49   69.56  537.29   72.84
#Mann= 3 , 0 , 0
       0      .1       0  287.15     .04       0  306.72      .1       0
Bank Sta=287.15,306.72
XS Rating Curve= 0 ,0
Exp/Cntr=0.3,0.1

Type RM Length L Ch R = 1 ,1019.21 ,85.22,79.89,42.79
BEGIN DESCRIPTION:
Section B
END DESCRIPTION:
XS GIS Cut Line= 6
1628907.12400058714958.5419998171628915.83399969714709.367000595
1628895.26399998714667.947999954 1628891.7059994714599.527000427
1628863.09399991714568.2530002591628839.13899997714441.160999313
#Sta/Elev= 30
       0   70.73   14.03   70.23   56.11   67.44  120.87   61.02  156.06   59.33
  172.72   58.04  179.78   57.13  186.84   55.66  200.96   50.79  211.17   48.29
  225.35   47.65  231.66   46.76  235.95   46.01  237.22   44.99  246.37   45.02
  248.91   46.24  250.87    47.2  258.69   48.34  297.12   50.95  304.13   51.78
  318.14   54.22  325.15   54.97  353.19    55.3   360.2   56.28  375.12    59.3
  394.09   61.96  415.05   63.58  450.23   65.27   464.3   66.28  538.51   72.75
#Mann= 3 , 0 , 0
       0      .1       0  231.66     .04       0  248.91      .1       0
Bank Sta=231.66,248.91
XS Rating Curve= 0 ,0
Exp/Cntr=0.3,0.1

Type RM Length L Ch R = 1 ,939.3165,62.94,87.92,52.6
BEGIN DESCRIPTION:
section not in LOMR HEC-RAS, added to smooth out floodplain delineation
END DESCRIPTION:
XS GIS Cut Line= 6
1628953.13274848714938.1159546231628996.80745971714713.503154129
1628914.65740766714645.9113391341628896.97954835 714576.23977603
1628868.90294831714511.7675832811628856.42445938714435.856775716
#Sta/Elev= 30
       0   69.92   35.66   67.21   64.18   64.25  106.97   61.55  135.49   58.43
  178.28   55.36  185.41   54.37  199.67   51.45   206.8   50.25  221.06   48.39
  228.82   47.65  231.39   46.47  237.01   43.94  246.21   43.94  249.66   46.37
  256.01   47.34  265.08   47.55  301.34   46.65  319.47   47.27  328.53   48.79
   335.2   50.69  356.87   52.49  371.31    52.6  378.53   53.65   400.2   58.82
  407.08   59.98  414.72   60.82  445.26   63.87   484.5   66.77  554.33   72.41
#Mann= 3 , 0 , 0
       0      .1       0  231.39     .04       0  249.66      .1       0
#XS Ineff= 2 , 0
                           262.9           48.23
Permanent Ineff=
       F       F
Bank Sta=231.39,249.66
XS Rating Curve= 0 ,0
Exp/Cntr=0.3,0.1

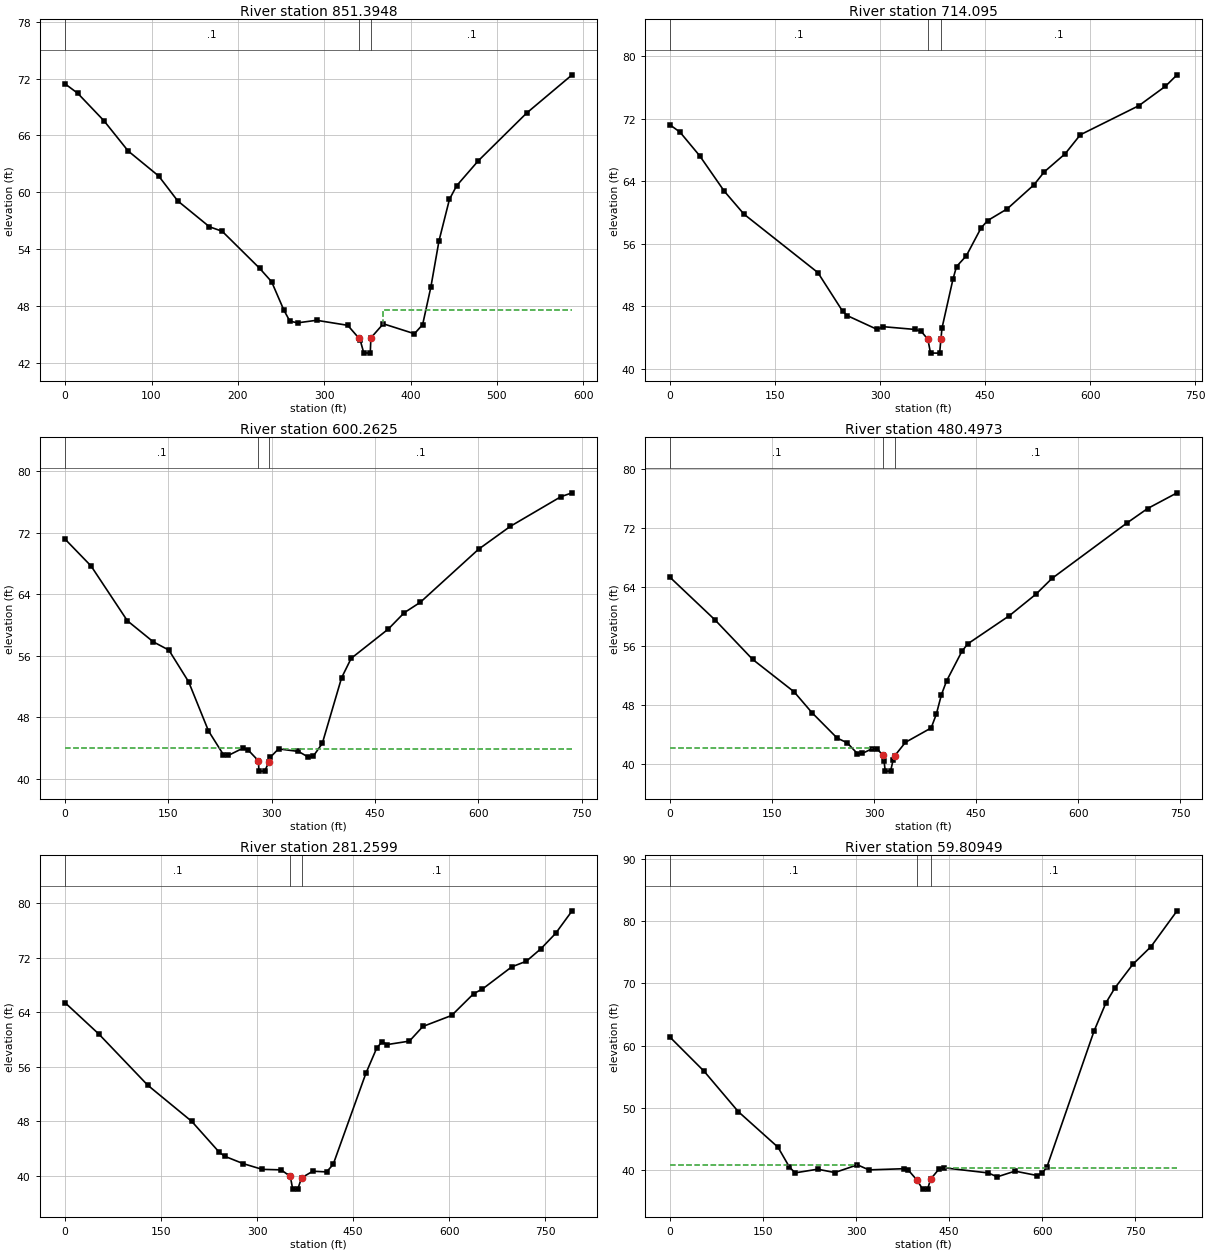
Type RM Length L Ch R = 1 ,851.3948,76.38,137.3,181.41
XS GIS Cut Line= 6
1628992.84700015714946.8670005951628980.87000087714855.041000366
1629021.45999913 714685.364000321629003.84399988714630.030000702
1628887.71400072714526.997999206 1628871.0790005714433.176000595
#Sta/Elev= 30
       0   71.45   14.56   70.46   44.99   67.55   72.99   64.36  108.27   61.72
  130.33   59.09   167.1   56.35   181.8   55.88  225.03   51.98  239.08   50.54
  253.12   47.57  260.15   46.38  269.07    46.2   291.1   46.47  327.14   45.94
  340.14   44.58  341.42   44.44  345.75   43.02  353.28      43  353.98   44.61
  368.35    46.1  404.42   45.05   413.9   46.01  423.39   49.96  432.88   54.88
  444.98   59.26   453.3   60.69  478.28   63.32  534.33   68.37  586.96   72.41
#Mann= 3 , 0 , 0
       0      .1       0  340.14     .04       0  353.98      .1       0
#XS Ineff= 2 , 0
                          367.59           47.59
Permanent Ineff=
       F       F
Bank Sta=340.14,353.98
XS Rating Curve= 0 ,0
Exp/Cntr=0.3,0.1

Type RM Length L Ch R = 1 ,714.095 ,133.58,113.83,80.66
XS GIS Cut Line= 6
1629003.61300091714943.7099990991629033.05599977  714657.1720009
1629049.81500058714624.9309997711629119.88200001714578.589000702
1629111.22999957714468.3889999391629034.71899989714278.774999619
#Sta/Elev= 30
       0   71.22   14.07   70.31   42.22   67.28   77.41   62.74  105.55    59.8
  211.11   52.32  246.29    47.4  253.33    46.8  295.94   45.04  303.83    45.4
   350.1   45.04  358.67   44.81  368.28   43.77  372.02   42.02  385.04   42.01
  386.91   43.83  388.41   45.21  404.08   51.47  409.15   53.09  423.17   54.47
   444.2   58.03  453.47   58.97   481.6   60.48  519.71   63.55  534.59   65.22
  564.35   67.53     586   69.96  669.66   73.69  707.69   76.18  724.25   77.64
#Mann= 3 , 0 , 0
       0      .1       0  368.28     .04       0  386.91      .1       0
Bank Sta=368.28,386.91
XS Rating Curve= 0 ,0
Exp/Cntr=0.3,0.1

Type RM Length L Ch R = 1 ,600.2625,120.39,119.76,70.62
XS GIS Cut Line= 6
1629065.14599991714958.4699993281629128.63699916 714798.43700029
1629178.78400041714603.8250007631629179.08200078714561.865999222
1629078.19199944714342.690000549 1629071.2339993714263.544000641
#Sta/Elev= 30
       0   71.16   37.65   67.68   90.37   60.56  128.02   57.82  150.62   56.75
  179.36   52.62  208.14   46.24  229.72   43.17  236.91   43.06  258.49   44.02
  265.68   43.77  280.64   42.36  281.36   41.02  289.67   41.02  295.63   42.15
  297.66    42.8  309.78   43.91  338.75   43.58  353.23   42.83  360.47   42.99
  373.36   44.62  401.36   53.15  415.32   55.68  469.27   59.49  492.38   61.61
   515.5   62.95  600.27   69.86   646.5   72.84  719.85   76.69  736.06   77.19
#Mann= 3 , 0 , 0
       0      .1       0  280.64     .04       0  295.63      .1       0
#XS Ineff= 2 , 0
          258.04   44.02  316.28           43.92
Permanent Ineff=
       F       F
Bank Sta=280.64,295.63
XS Rating Curve= 0 ,0
Exp/Cntr=0.3,0.1

Type RM Length L Ch R = 1 ,480.4973,110.1,199.24,169.13
BEGIN DESCRIPTION:
Section A
END DESCRIPTION:
XS GIS Cut Line= 6
1629167.90099907714939.6879997251629194.13899995714857.304000854
1629278.23500064714725.457000747 1629218.4710007714561.795999542
1629098.37500003714330.851999283 1629094.3460007714266.653999344
#Sta/Elev= 30
       0    65.3   66.12   59.52  121.35   54.17  182.39   49.76  208.55   46.94
   245.6   43.49  260.43   42.84  275.26   41.39  282.67   41.41  297.49   42.06
  304.91      42  312.32   41.18  314.64   40.35  316.31   39.01  324.18      39
  327.98   40.52  330.61   41.12  346.07   42.91  383.85   44.86   391.4   46.71
  398.96   49.37  406.51   51.24  428.96   55.24  437.56   56.27  498.99   60.11
  538.07   63.03  561.52   65.16  671.51   72.67  702.18   74.65  745.46   76.78
#Mann= 3 , 0 , 0
       0      .1       0  312.32     .04       0  330.61      .1       0
#XS Ineff= 2 , 0
          297.45   42.11
Permanent Ineff=
       F       F
Bank Sta=312.32,330.61
XS Rating Curve= 0 ,0
Exp/Cntr=0.3,0.1

Type RM Length L Ch R = 1 ,281.2599,144.68,221.45,141.55
XS GIS Cut Line= 6
1629182.61199951714947.0429992821629207.43700032714882.681999207
 1629382.4710007714661.7980003361629324.88599972 714524.88999939
1629324.87800027714423.8780002741629384.88999939714247.346000671
#Sta/Elev= 30
       0   65.38   52.52    60.8  129.13   53.27  197.87   47.96  240.83   43.43
  249.42   42.84  278.56   41.75     308   40.92  337.44   40.85  351.71   39.89
  355.54   38.02  363.42   38.02  369.32   39.67   386.8   40.65  408.36   40.55
  418.73   41.64  469.79   55.01  486.64    58.7  495.06   59.68  502.84   59.24
  537.84   59.75  558.84    61.9  603.85   63.52  638.26   66.72  651.97    67.4
  697.66   70.65  720.51   71.48  743.36   73.32   766.2   75.56  792.01   78.88
#Mann= 3 , 0 , 0
       0      .1       0  351.71     .04       0  369.32      .1       0
Bank Sta=351.71,369.32
XS Rating Curve= 0 ,0
Exp/Cntr=0.3,0.1

Type RM Length L Ch R = 1 ,59.80949,64.11,59.81,81.23
XS GIS Cut Line= 6
1629249.09199905714928.0879993591629510.56999969714707.698999405
1629519.47100069 714642.492000581629473.21599965714448.711000443
1629419.59600069714369.9230003361629450.80299953714259.451000229
#Sta/Elev= 30
       0   61.36   54.93   55.89  109.86   49.43  173.94   43.71  192.25   40.55
  201.41   39.59  238.02   40.18  265.49   39.64  302.11   40.88  320.42   40.07
  377.29   40.26  384.36      40  398.34    38.4  407.15   36.98  415.17      37
  420.17   38.59  434.01   40.26  441.19   40.41  513.01   39.58  527.37   38.95
   556.1   39.87     592   39.16  599.18   39.51  607.35   40.46  683.56   62.35
  702.66   66.87   717.2   69.28   746.3   73.09   775.4   75.91  817.45   81.66
#Mann= 3 , 0 , 0
       0      .1       0  398.34     .04       0  420.17      .1       0
#XS Ineff= 2 , 0
          301.88   40.89  443.22           40.44
Permanent Ineff=
       F       F
Bank Sta=398.34,420.17
XS Rating Curve= 0 ,0
Exp/Cntr=0.3,0.1
Stream Node=Laurel Run Trib ,Herron          , 0 , 0 ,Upstream end
Stream Node=Laurel Run Trib ,Herron          , 0 , 1 ,Downstream end

Chan Stop Cuts=-1
Use User Specified Reach Order=0