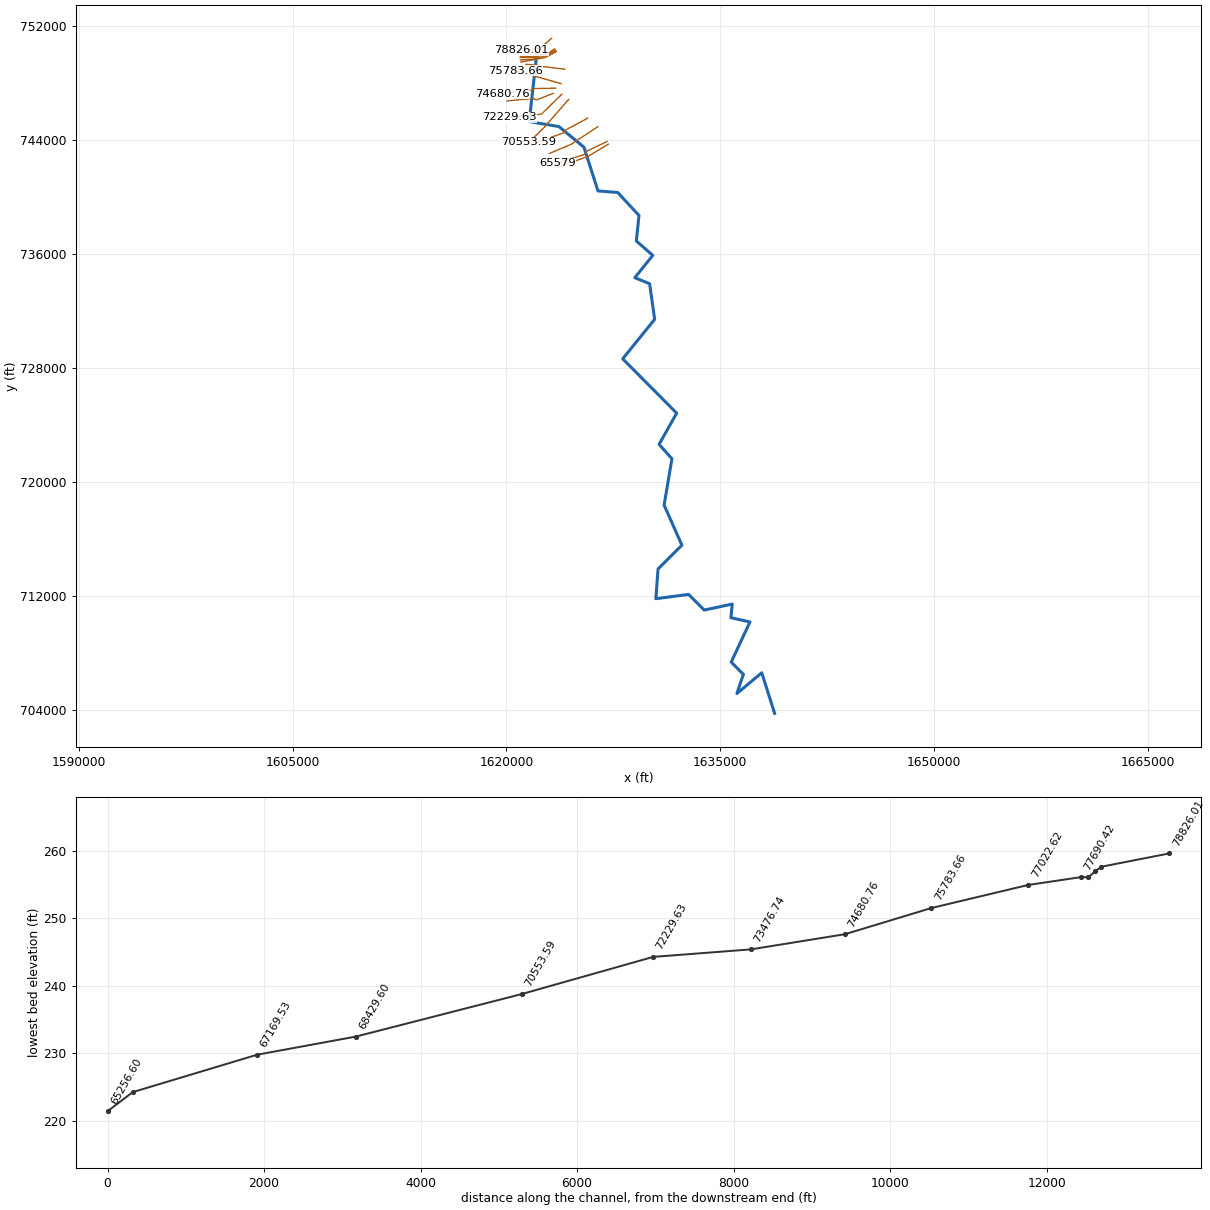
--- LittleElkCreek.prj (project) ---

Proj Title=Little Elk Creek
Current Plan=p01
Default Exp/Contr=0.3,0.1
English Units
Geom File=g01
Geom File=g02
Flow File=f01
Flow File=f02
Plan File=p01
Plan File=p02
Y Axis Title=Elevation
X Axis Title(PF)=Main Channel Distance
X Axis Title(XS)=Station
BEGIN DESCRIPTION:
Little Elk Creek - Georeferenced HEC-RAS model.  There was an existing detailed model for approximately 2.7 miles between the mouth of Little Elk Creek and Zeitler Road.  The remaining portion of the stream is an approximate method stream.  Projection:  MD Stateplane.  Horizontal datum:  NAD83.  Vertical datum: NAVD88.  Units:Feet.  Created by: Ann Banitt, USACE- St Paul District as part of FEMA Map Modernization study for Cecil County, MD.
NOTE - LOMR 06-03-B926P converted a section of the stream into detailed, from station 24874 to 31069.  The LOMR was used to lay out sections, the sections were cut from the county DEM, and channel data was imported from the LOMR HEC-RAS model.
END DESCRIPTION:
DSS Export Rating Curves= 0
DSS Export Rating Curve Sorted= 0
DSS Export Volume Flow Curves= 0
DXF Filename=LittleElkCreek2.
DXF OffsetX= 0
DXF OffsetY= 0
DXF ScaleX= 1
DXF ScaleY= 10

--- LittleElkCreek.p01 (plan) ---

Plan Title=Little Elk Creek - Frequency Profiles
Program Version=4.00
Short Identifier=Little Elk Creek
Geom File=g01
Flow File=f01
Subcritical Flow
K Sum by GR= 0
Std Step Tol= 0.01
Critical Tol= 0.01
Num of Std Step Trials= 20
Max Error Tol= 0.3
Flow Tol Ratio= 0.001
Split Flow NTrial= 30
Split Flow Tol= 0.02
Split Flow Ratio= 0.02
Log Output Level= 0
Friction Slope Method= 1
Unsteady Friction Slope Method= 2
Unsteady Bridges Friction Slope Method= 1
Secant Critical Depth
Global Vel Dist= 0 , 0 , 0
Global Log Level= 0
CheckData=True
Encroach Param=-1 ,0,0, 0
Computation Interval=1HOUR
Output Interval=1HOUR
Run HTab= 0
Run UNet= 0
Run PostProcess= 0
Run WQNet= 0
UNET Theta= 1
UNET Theta Warmup= 1
UNET ZTol= 0.02
UNET ZSATol= 0.05
UNET MxIter= 20
UNET MaxInSteps= 0
UNET DtIC= 0
UNET DtMin= 0
UNET MaxCRTS= 20
UNET WFStab= 2
UNET SFStab= 1
UNET WFX= 1
UNET SFX= 1
UNET DSS MLevel= 4
UNET DZMax Abort= 100
UNET Convert EG Bridges= 0
UNET Use Existing IB Tables=-1
UNET Froude Reduction=False
UNET Froude Limit= 1
UNET Froude Power= 10
UNET Time Slicing=0,0, 5
Instantaneous Interval=1HOUR
Write IC File= 0
Echo Input=False
Echo Output=False
Write Detailed= 0
Detailed Automatic Start=False, 10
WQ ULTIMATE=-1
WQ Max Comp Step=1HOUR
WQ Output Interval=15MIN
WQ Output Selected Increments= 0
WQ Output face flow=0
WQ Output face velocity=0
WQ Output face area=0
WQ Output face dispersion=0
WQ Output cell volume=0
WQ Output cell surface area=0
WQ Output cell continuity=0
WQ Output face conc=0
WQ Output face dconc_dx=0
WQ Output face courant=0
WQ Output face peclet=0
WQ Output face adv mass=0
WQ Output face disp mass=0
WQ Output cell mass=0
WQ Output cell source sink temp=0
WQ Output cell source sink nsm=0
WQ Output MaxMinRange=-1
WQ Daily Max Min Mean=-1
WQ Daily Range=0
WQ Daily Time=0
WQ Create Restart=0
WQ Fixed Restart=0
WQ System Summary=False
Sorting and Armoring Iterations= 10
XS Update Threshold= 0.02
Hydraulics Update Threshold= 0.02
Energy Slope Method= 0
Volume Change Method= 0
XS Weighting Method= 0
Number of US Weighted Cross Sections= 1
Number of DS Weighted Cross Sections= 1
Upstream XS Weight=0.25
Main XS Weight=0.5
Downstream XS Weight=0.25
Number of DS XS's Weighted with US Boundary= 1
Upstream Boundary Weight= 1
Weight of XSs Associated with US Boundary= 0
Number of US XS's Weighted with DS Boundary= 1
Downstream Boundary Weight= 0.5
Weight of XSs Associated with DS Boundary= 0.5
Sediment Output Level= 4
Mass or Volume Output= 0
Output Increment Type= 1
Profile and TS Output Increment= 10
XS Output Flag= 0
XS Output Increment= 10
Disregard all LS=0
Disregard all Conn=0
Disregard all Breaches=0
Disregard all Pumps=0

--- LittleElkCreek.p02 (plan) ---

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Plan Title=Little Elk Creek _Floodway
Short Identifier=Little Elk FW
Geom File=g01
Flow File=f02
Encroach Param=-1 ,0,0, 2
Encroach River=LittleElkCreek
Encroach Reach=One
Encroach Node=31069.11
       1    1625    2060
Encroach Node=30936.02
       1    1580    2080
Encroach Node=30663.39
       1    1500    2000
Encroach Node=30305.15
       1    1300    1800
Encroach Node=30000.60
       1    1000    1610
Encroach Node=29646.95
       1    1150    1740
Encroach Node=29272.22
       1    1310    1880
Encroach Node=29090.12
       1    1395    1995
Encroach Node=28976.02
       1    1400    2000
Encroach Node=28851.74
       1    1400    2020
Encroach Node=28695.04
       1    1120    1740
Encroach Node=28448.97
       1     800    1350
Encroach Node=28175.93
       1     430     940
Encroach Node=27890.25
       1     270     740
Encroach Node=27624.96
       1     300     730
Encroach Node=27348.47
       1     760    1120
Encroach Node=27100.34
       1     860    1220
Encroach Node=26748.37
       1     970    1330
Encroach Node=26490.20
       1     990    1350
Encroach Node=26251.77
       1    1120    1480
Encroach Node=26052.87
       1    1180    1560
Encroach Node=25833.45
       1    1180    1700
Encroach Node=25524.04
       1    1340    1920
Encroach Node=25162.46
       1    1600    2250
Encroach Node=24975.59
       1    1650    2230
Encroach Node=24874.92
       1    1690    2200
Encroach Node=15456.97
       1    1620 2439.06
Encroach Node=14589.35
       1 1237.99 2120.79
Encroach Node=14047.48
       1    1340    1950
Encroach Node=13903.91
       1  1272.7 1816.85
Encroach Node=13159.58
       1 1115.49  1571.8
Encroach Node=12966.81
       1    1088    1620
Encroach Node=12843.91
       1    1080    1600
Encroach Node=12685.25
       1  901.38 1377.64
Encroach Node=12255.67
       1     900    1500
Encroach Node=11960.66
       1     610    1200
Encroach Node=11735.16
       1     720    1190
Encroach Node=11657.55
       1 1847.35  2265.8
Encroach Node=11619.98
       1    1320    1730
Encroach Node=11583.56
       1    1267    1700
Encroach Node=11408.34
       1    1150 1643.84
Encroach Node=10303.51
       1    1106    1900
Encroach Node=10159.46
       1    1209    1660
Encroach Node=9918.001
       1     766    1197
Encroach Node=9848.929
       1  716.69    1280
Encroach Node=9749.913
       1  816.64    1500
Encroach Node=9576.880
       1 1028.73    1700
Encroach Node=9514.142
       1 1238.81    1560
Encroach Node=9347.895
       1 1737.24 2044.98
Encroach Node=9253.849
       1    2100    2770
Encroach Node=9141.933
       1    1370    2100
Encroach Node=9056.404
       1  936.45    1687
Encroach Node=8710.909
       1     720    1575
Encroach Node=8541.319
       1     615 1703.16
Encroach Node=8245.082
       1  686.36 2181.08
Encroach Node=7472.504
       1    1423 2804.86
Encroach Node=5962.369
       1    2000    3300
Encroach Node=2854.345
       1 1138.89    1920
Encroach Node=2417.971
       1     848    1750
Encroach Node=2319.868
       1     770    1750
Encroach Node=2123.127
       1   714.2    1820
Encroach Node=2004.561
       1  729.12    1900
Encroach Node=1274.915
       1 1031.15    2300
Encroach Node=309.7835
       1 1947.34 3235.52

--- LittleElkCreek.f01 (steady flow) ---

Flow Title=Little Elk Creek - Frequency Profiles
Program Version=4.00
Number of Profiles= 5
Profile Names=TQ10CUR,TQ50CUR,TQ100CUR,TQ500CUR,TQ100ULT
River Rch & RM=LittleElkCreek,One             ,78826.01
    2930    5850    7640   13500    7680
River Rch & RM=LittleElkCreek,One             ,77022.62
    3040    6080    7930   14000    7970
River Rch & RM=LittleElkCreek,One             ,65579
    3460    6870    8940   15700    9040
River Rch & RM=LittleElkCreek,One             ,65256.60
    3550    7040    9160   16100    9350
River Rch & RM=LittleElkCreek,One             ,55745.01
    3740    7400    9600   16800    9880
River Rch & RM=LittleElkCreek,One             ,44633.14
    3950    7760   10100   17500   10400
River Rch & RM=LittleElkCreek,One             ,42055.32
    3970    7810   10100   17600   10400
River Rch & RM=LittleElkCreek,One             ,41903.01
    4020    7890   10200   17800   10600
River Rch & RM=LittleElkCreek,One             ,39604.79
    4119    8080   10500   18201   10900
River Rch & RM=LittleElkCreek,One             ,29090.12
    4268    8461   10957   19071   11519
River Rch & RM=LittleElkCreek,One             ,25162.46
    4468    9012   11726   20409   12717
River Rch & RM=LittleElkCreek,One             ,14589.35
    4680    9524   12362   21710   14361
River Rch & RM=LittleElkCreek,One             ,5962.369
    4996   10397   13525   23721   16356
Boundary for River Rch & Prof#=LittleElkCreek,One             , 1
Up Type= 0
Dn Type= 3
Dn Slope=0.0008
Boundary for River Rch & Prof#=LittleElkCreek,One             , 2
Up Type= 0
Dn Type= 3
Dn Slope=0.0008
Boundary for River Rch & Prof#=LittleElkCreek,One             , 3
Up Type= 0
Dn Type= 3
Dn Slope=0.0008
Boundary for River Rch & Prof#=LittleElkCreek,One             , 4
Up Type= 0
Dn Type= 3
Dn Slope=0.0008
Boundary for River Rch & Prof#=LittleElkCreek,One             , 5
Up Type= 0
Dn Type= 3
Dn Slope=0.0008
DSS Import GetInterval= 0
DSS Import GetPeak= 0
DSS Import FillOption= 0

--- LittleElkCreek.f02 (steady flow) ---

Flow Title=Little Elk Creek - Floodway
Program Version=4.00
Number of Profiles= 2
Profile Names=TQ100CUR,Floodway
River Rch & RM=LittleElkCreek,One             ,78826.01
    7640    7640
River Rch & RM=LittleElkCreek,One             ,77022.62
    7930    7930
River Rch & RM=LittleElkCreek,One             ,65579
    8940    8940
River Rch & RM=LittleElkCreek,One             ,65256.60
    9160    9160
River Rch & RM=LittleElkCreek,One             ,55745.01
    9600    9600
River Rch & RM=LittleElkCreek,One             ,44633.14
   10100   10100
River Rch & RM=LittleElkCreek,One             ,42055.32
   10100   10100
River Rch & RM=LittleElkCreek,One             ,41903.01
   10200   10200
River Rch & RM=LittleElkCreek,One             ,39604.79
   10500   10500
River Rch & RM=LittleElkCreek,One             ,29090.12
   10957   10957
River Rch & RM=LittleElkCreek,One             ,25162.46
   11726   11726
River Rch & RM=LittleElkCreek,One             ,14589.35
   12362   12362
River Rch & RM=LittleElkCreek,One             ,5962.369
   13525   13525
Boundary for River Rch & Prof#=LittleElkCreek,One             , 1
Up Type= 0
Dn Type= 3
Dn Slope=0.0008
Boundary for River Rch & Prof#=LittleElkCreek,One             , 2
Up Type= 0
Dn Type= 3
Dn Slope=0.0008
Set Internal Change=LittleElkCreek  ,One             ,24874.92, 2 , 3 ,39.72
DSS Import GetInterval= 0
DSS Import GetPeak= 0
DSS Import FillOption= 0

--- LittleElkCreek.g01 (geometry) ---

Geom Title=Little Elk Creek Geometry
Program Version=4.00

River Reach=LittleElkCreek  ,One
Reach XY= 30
1622169.69119398750411.7115118951621596.16319795745271.887650624
1623680.69193062744926.2883896681625436.85503845743479.033575699
1626420.84006557740411.2610475121627806.00469844740304.071033031
1629295.33283441738691.061667755 1629112.4375269736898.749524027
1630264.12621686735891.6010075211629004.03239678734325.749128133
1630043.60979836733899.540924266 1630395.6948363731402.516773418
1628155.13081315 728633.61565128 1631941.4745819724821.644698814
1630707.07086109722634.6366178391631607.60360032721622.303045318
1631059.32006179718369.3582525851632309.03896524715560.553756401
1630634.68065551713895.638538793  1630480.406158711808.334009618
1632774.51902346712105.0597817151633875.78214931711007.349957541
1635838.25696725711432.1681855321635744.02586085710472.357058838
1637082.78139412710174.2040219311635765.03612828707359.337748647
1636620.26287842706498.5601883231636164.90880895 705154.74424623
1637908.50632438706611.8171649581638811.86551417703761.737050563

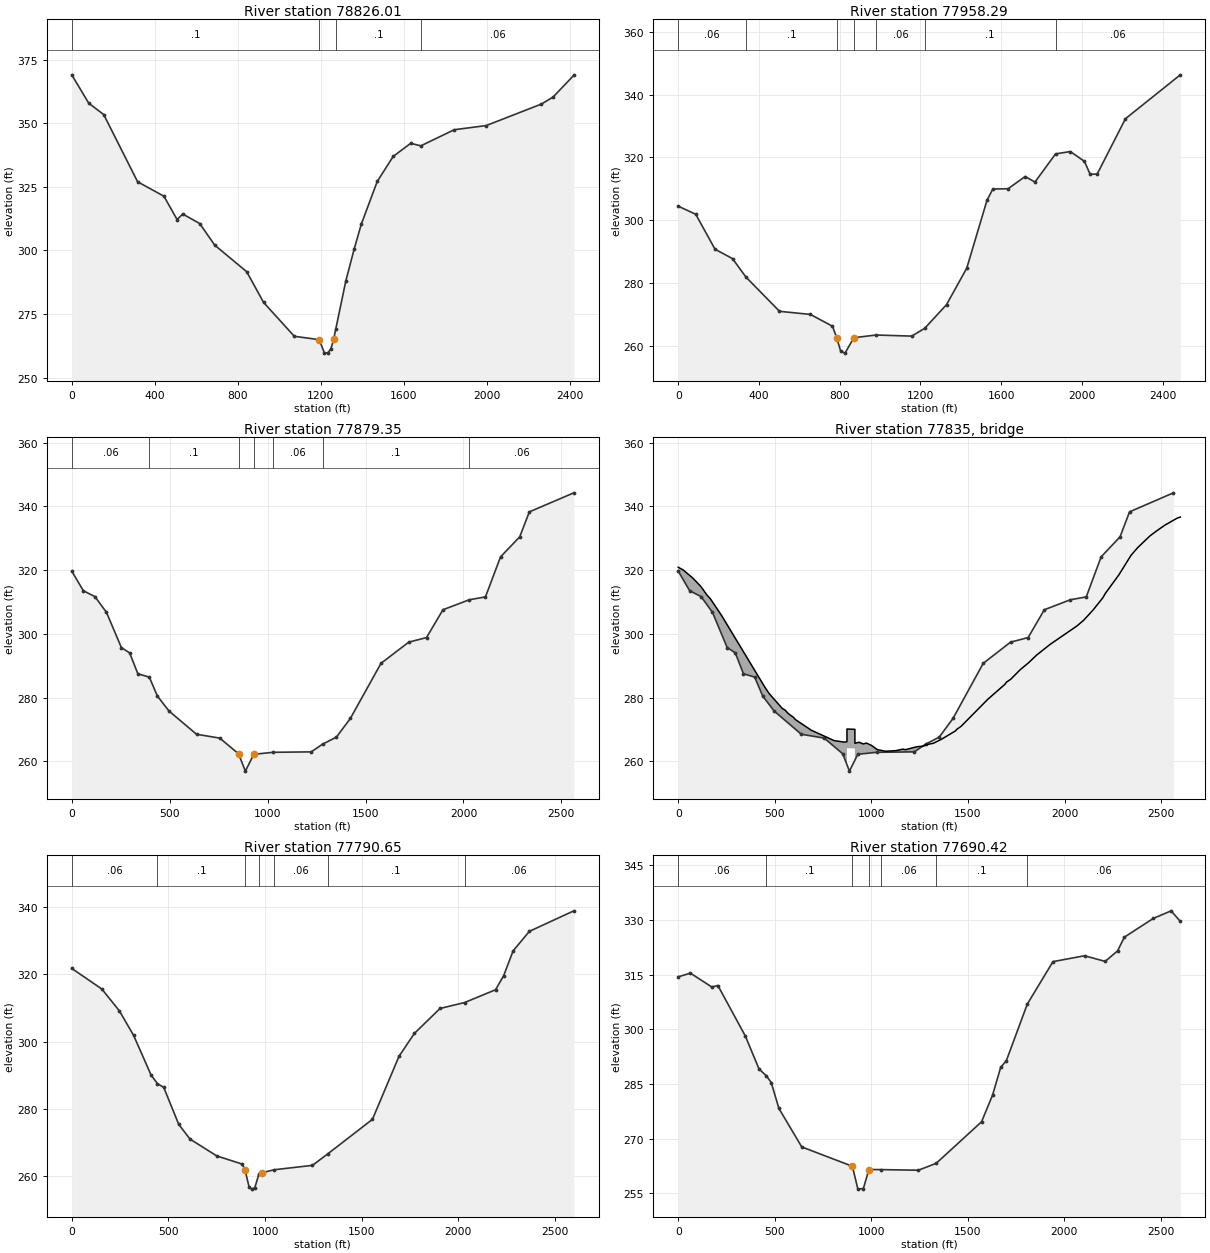
Type RM Length L Ch R = 1 ,78826.01,721.14,867.72,495.82
XS GIS Cut Line= 4
1623170.67149222751115.521621913 1622361.0596866750450.299182862
1622082.59447955750295.5962900671621030.61480847750295.596290067
#Sta/Elev= 30
       0  369.11   81.54  357.97  154.02  353.46  317.09  327.04  443.93  321.35
  507.35  312.16  534.53  314.36  616.07  310.61  688.55  302.11  842.57  291.65
  924.11  279.55 1071.88  266.25 1191.99  264.91 1216.01  259.86 1232.03  259.62
 1248.05  261.32 1261.91  265.16 1272.07  269.27 1320.11  288.05 1360.15  300.53
  1394.4  310.31  1471.4  327.16  1548.4  337.02  1632.4  342.16 1681.26341.1768
  1842.4  347.51  1996.4  349.15  2262.4  357.62  2318.4  360.37 2418.38  368.93
#Mann= 4 ,-1 , 0
       0      .1       0 1191.99     .04       0 1272.07      .1       0
 1681.26     .06       0
Bank Sta=1191.99,1261.91
XS Rating Curve= 0 ,0
Exp/Cntr=0.3,0.1

Type RM Length L Ch R = 1 ,77958.29,77.44,78.93,85.72
XS GIS Cut Line= 6
1623355.26034112750369.2559416291623032.89442645750133.192712814
1622657.22391173750024.045198381 1622578.5361688750013.891941234
1621839.25213224749850.4879589081620979.39816697749863.179530352
#Sta/Elev= 30
       0  304.47   86.76  301.89   182.2  290.76  268.96  287.76  334.52281.9562
  501.61  270.97  654.69  269.98  764.03  266.22   785.9  262.38  788.19  261.84
  804.88  258.25  826.05  257.65   870.1  262.57  980.44263.4191 1156.86  263.07
  1221.2265.5689 1328.92  273.09 1429.28  284.72 1529.65  306.36 1558.32  309.93
 1634.23  310.03 1718.24  313.92 1767.24  312.16 1869.11321.1227 1942.26  321.88
 2012.27  318.76 2040.27  314.65 2075.28  314.69 2215.29  332.33 2487.17  346.32
#Mann= 7 ,-1 , 0
       0     .06       0  334.52      .1       0  788.19     .04       0
   870.1      .1       0  980.44     .06       0  1221.2      .1       0
 1869.11     .06       0
Bank Sta=785.9,870.1
XS Rating Curve= 0 ,0
Exp/Cntr=0.5,0.3

Type RM Length L Ch R = 1 ,77879.35,91.01,88.71,97.96
BEGIN DESCRIPTION:
Under water portion adjusted as per bridge inspection notes.
END DESCRIPTION:
XS GIS Cut Line= 6
1623413.64156975750323.5662844331623063.35419792750087.503055602
1622672.45379744749952.9723983111622560.76796877749925.050941125
1621842.42502508749772.752083808 1620964.1682812749775.290398106
#Sta/Elev= 30
       0   319.7   59.09  313.55  118.18  311.71  177.27  306.77  253.24  295.73
  295.44  294.05  337.65  287.49  395.81286.4609  437.21  280.52  496.44  275.82
  637.09  268.53  755.54  267.33  851.61   262.4  886.32  256.97  929.61  262.25
  1028.5 262.873 1222.37  263.01 1280.75265.4283 1350.94  267.62 1422.37  273.49
 1578.93  290.78  1720.3  297.42  1811.3  298.86  1895.3  307.59 2029.82310.7198
  2112.3  311.62  2189.3  324.18  2287.3  330.46  2336.3  338.29 2563.55  344.26
#Mann= 7 ,-1 , 0
       0     .06       0  395.81      .1       0  851.61     .04       0
  929.61      .1       0  1028.5     .06       0 1280.75      .1       0
 2029.82     .06       0
Bank Sta=851.61,929.61
XS Rating Curve= 0 ,0
Exp/Cntr=0.5,0.3

Type RM Length L Ch R = 3 ,77835   ,,,
BEGIN DESCRIPTION:
Blake Road.  CE#050407PF-3.  Top of road from LIDAR.  Bridge geometry from Bridge inspection dimensions and photgraphs.
END DESCRIPTION:
Bridge Culvert--1,0,-1,-1, 0
Deck Dist Width WeirC Skew NumUp NumDn MinLoCord MaxHiCord MaxSubmerge Is_Ogee
30,29,2.6,0, 60, 60, , , 0.95, 0, 0,0,,
       0      25   75.01  116.68  150.01  166.68  225.02  447.98  471.46  538.82
  553.76   568.7  598.59  606.06  688.72  806.34  857.79   873.4   873.5   914.5
   914.6  936.09  957.86  972.37  979.62 1001.39 1030.41 1073.95 1126.67 1162.56
 1176.91 1234.34 1270.23 1284.58 1320.47 1363.54 1435.32  1442.5 1464.03 1603.43
  1691.8 1698.95 1720.42 1770.51 1813.44 1854.97 1925.09 2064.24 2099.24 2148.24
 2197.24 2211.24 2281.24 2344.25 2379.25 2442.25 2477.25 2519.25 2582.25 2599.18
  320.92  320.09  317.55  314.92  312.11  311.01  305.72  283.35  281.23  276.63
  276.09  275.08  273.73  273.17   269.8  266.56  266.08  266.18  270.18  270.08
  265.71  266.02  265.49  265.75  265.64  264.99  263.72   263.2   263.4  263.85
   263.7  264.61  264.82  265.28   265.7  266.99  269.59  270.11  271.01  279.55
  284.23  284.87  285.75  288.79  290.95  293.35  296.72  302.51  304.32  307.55
  311.27  312.72  318.54  324.68  327.12  330.76  332.34  334.12   336.3  336.67
                                                                                
                                                                  264.18  264.08
                                                                                
                                                                                
                                                                                
                                                                                
       0      25   75.01  116.68  150.01  166.68  225.02  447.98  471.46  538.82
  553.76   568.7  598.59  606.06  681.37  754.88  798.99  806.34  857.79  892.56
   909.4   909.5   950.5   950.6  957.86  979.62 1001.39 1030.41 1073.95 1126.67
 1162.56 1176.91 1234.34 1270.23 1284.58 1320.47 1363.54 1435.32  1442.5 1464.03
 1603.43  1691.8 1698.95 1720.42 1770.51 1854.97 1925.09 2064.24 2099.24 2148.24
 2197.24 2211.24 2281.24 2344.25 2379.25 2442.25 2477.25 2519.25 2582.25 2599.18
  320.92  320.09  317.55  314.92  312.11  311.01  305.72  283.35  281.23  276.63
  276.09  275.08  273.73  273.17  270.08  267.83  266.91  266.56  266.08  266.21
  265.84  269.84  269.74  265.67  265.49  265.64  264.99  263.72   263.2   263.4
  263.85   263.7  264.61  264.82  265.28   265.7  266.99  269.59  270.11  271.01
  279.55  284.23  284.87  285.75  288.79  293.35  296.72  302.51  304.32  307.55
  311.27  312.72  318.54  324.68  327.12  330.76  332.34  334.12   336.3  336.67
                                                                                
                                                                                
          263.84  263.74
                                                                                
                                                                                
                                                                                
BR Coef=-1 , 0 , 0 ,, 0 ,,,0.8,0,,0,
WSPro=,,,, 1 ,,,, 0 ,,,, 0 ,,,,-1 ,-1 ,-1 , 0 , 0 , 0 , 0 , 0
BR U #Sta/Elev= 30
       0   319.7   59.09  313.55  118.18  311.71  177.27  306.77  253.24  295.73
  295.44  294.05  337.65  287.49  395.81 286.461  437.21  280.52  496.44  275.82
  637.09  268.53  755.54  267.33  851.61   262.4  886.32  256.97  929.61  262.25
  1028.5 262.873 1222.37  263.01 1280.75 265.428 1350.94  267.62 1422.37  273.49
 1578.93  290.78  1720.3  297.42  1811.3  298.86  1895.3  307.59 2029.82  310.72
  2112.3  311.62  2189.3  324.18  2287.3  330.46  2336.3  338.29 2563.55  344.26
BR U #Mann= 7
       0     .06  395.81      .1  851.61    .035  929.61      .1  1028.5     .06
 1280.75      .1 2029.82     .06
BR D #Sta/Elev= 30
       0  321.74   155.9   315.6  246.15  309.14     320  301.82  410.25  290.05
  443.49 287.468  475.89  286.36  553.42  275.37  611.75  270.99  750.29  265.97
  881.54  263.56  896.59   261.8     918  256.64  932.58   256.1  947.17  256.51
  969.04  260.72 1047.79 261.866 1245.48  263.17 1323.45  266.53 1418.74  269.82
 1555.91  276.86 1693.08  295.57 1772.49  302.39 1905.59  309.83 2032.71 311.592
  2192.8  315.39 2234.83  319.57 2283.87  326.97 2367.93  332.77 2598.05  338.87
BR D #Mann= 7
       0     .06  443.49      .1  896.59    .035  969.04      .1 1047.79     .06
 1323.45      .1 2032.71     .06
BC Design=,, 0 ,, 0 ,,,,,,
BC Use User HTab Curves=0
BC User HTab FreeFlow(D)= 0

Type RM Length L Ch R = 1 ,77790.65,104.96,100.23,91.29
BEGIN DESCRIPTION:
Under water portion adjusted as per bridge inspection notes.
END DESCRIPTION:
XS GIS Cut Line= 5
1623463.77327695750237.5808879141623022.74116927 749967.88499476
1622489.69516869749812.4132445751621810.69609647749641.077030092
1620985.74395269749609.348101482
#Sta/Elev= 30
       0  321.74   155.9   315.6  246.15  309.14     320  301.82  410.25  290.05
  443.49287.4683  475.89  286.36  553.42  275.37  611.75  270.99  750.29  265.97
  881.54  263.56  896.59   261.8     918  256.64  932.58   256.1  947.17  256.51
  969.04  260.72  983.63  260.97 1047.79 261.866 1245.48  263.17 1323.45266.5304
 1555.91  276.86 1693.08  295.57 1772.49  302.39 1905.59  309.83 2032.71 311.592
  2192.8  315.39 2234.83  319.57 2283.87  326.97 2367.93  332.77 2598.05  338.87
#Mann= 7 ,-1 , 0
       0     .06       0  443.49      .1       0  896.59     .04       0
  969.04      .1       0 1047.79     .06       0 1323.45      .1       0
 2032.71     .06       0
Bank Sta=896.59,983.63
XS Rating Curve= 0 ,0
Exp/Cntr=0.5,0.3

Type RM Length L Ch R = 1 ,77690.42,667.47,667.8,598.55
XS GIS Cut Line= 3
1623489.15641984750177.2959235611622702.27899034749764.819851667
 1621017.4728813749450.703458443
#Sta/Elev= 30
       0  314.41   63.23  315.41  173.88  311.61  205.49  312.02  347.75  298.15
  418.88  289.08  455.92287.2628  482.11  285.38  521.63  278.27  640.18  267.69
  902.68  262.37  931.16   256.1  959.64  256.27  988.12  261.48  1052.1261.4597
 1244.46  261.29 1336.79263.1756 1572.01  274.59 1628.98  281.89  1671.7  289.61
 1700.18  291.31 1809.36306.9364 1942.28  318.58 2106.06  320.19 2212.87  318.64
 2276.95  321.53 2312.55   325.3 2462.09  330.44 2554.66  332.53 2602.27  329.63
#Mann= 7 ,-1 , 0
       0     .06       0  455.92      .1       0  902.68     .04       0
  988.12      .1       0  1052.1     .06       0 1336.79      .1       0
 1809.36     .06       0
Bank Sta=902.68,988.12
XS Rating Curve= 0 ,0
Exp/Cntr=0.3,0.1

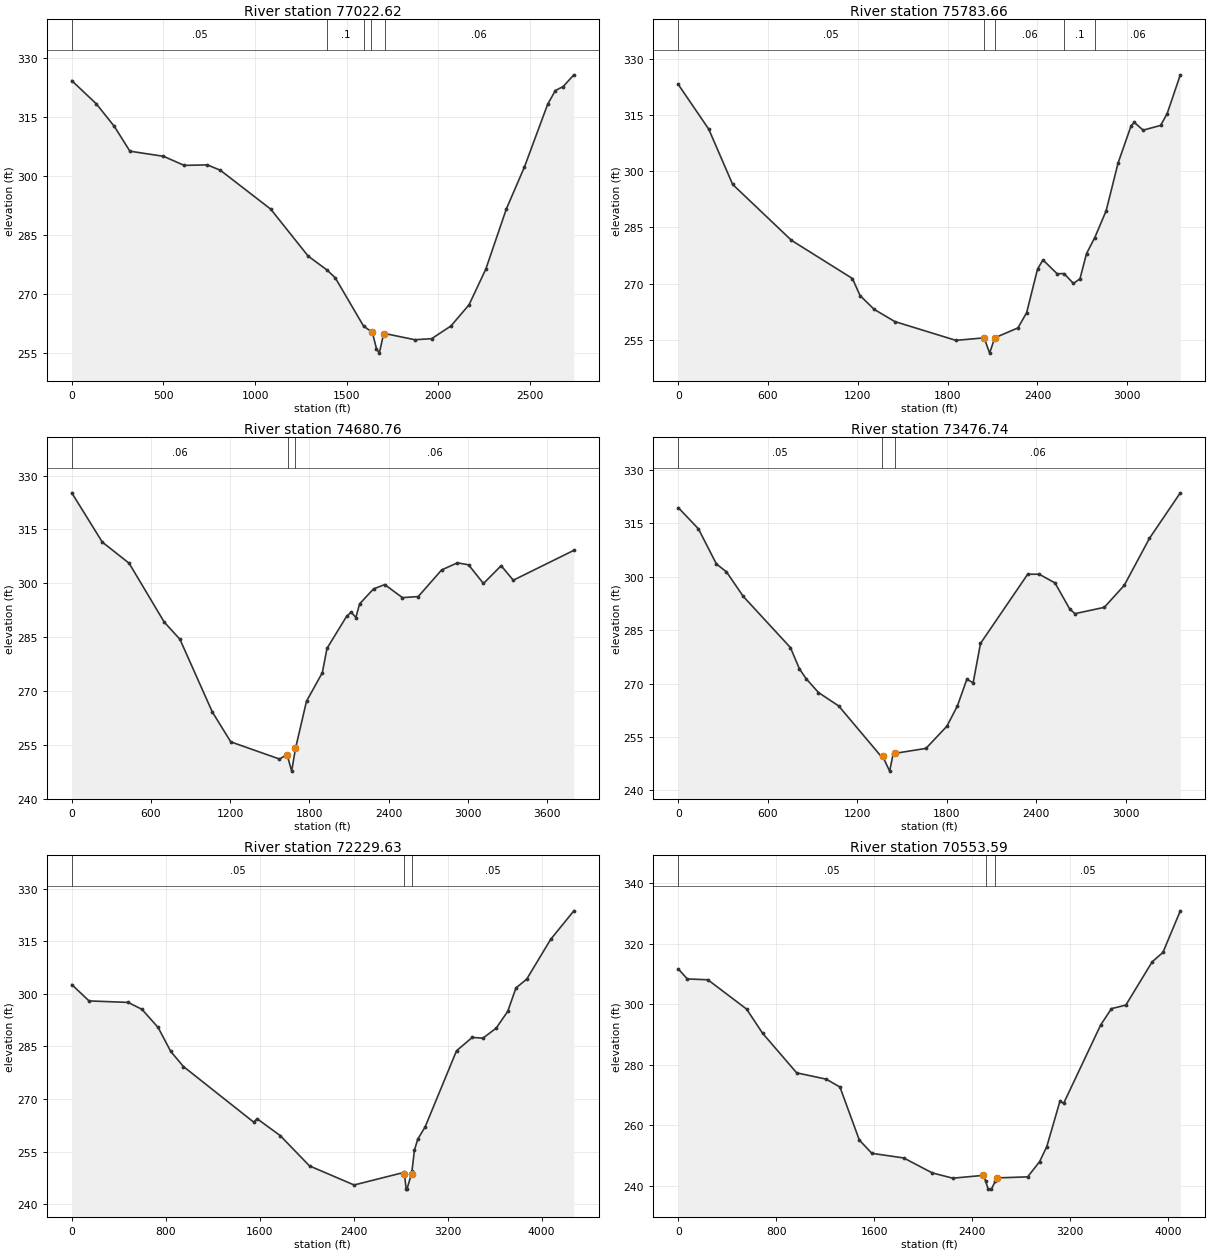
Type RM Length L Ch R = 1 ,77022.62,900.79,1238.96,1034.06
XS GIS Cut Line= 4
1624085.17446901748950.7698083371622496.43756598749140.478816643
1622384.89055139 749196.252323941621374.65585545749295.744904608
#Sta/Elev= 30
       0  324.32  133.94  318.42  232.64  312.65  317.24  306.36  500.53  305.06
  613.33  302.75  740.22  302.87  810.72  301.51 1085.66  291.61  1290.1  279.65
 1392.67276.1249 1438.14  274.11 1592.13261.8487 1631.33  260.54 1639.15  260.45
 1662.63   256.1 1678.28  254.95 1701.76  259.86 1706.93  259.95 1872.44  258.36
 1963.88  258.63 2069.39  261.87 2167.87  267.25 2259.31  276.32 2371.85   291.7
 2470.33  302.35 2596.94   318.3 2639.14  321.81 2681.34  322.81 2739.86   325.8
#Mann= 5 ,-1 , 0
       0     .05       0 1392.67      .1       0 1592.13     .06       0
 1631.33     .04       0 1706.93     .06       0
Bank Sta=1639.15,1701.76
XS Rating Curve= 0 ,0
Exp/Cntr=0.3,0.1

Type RM Length L Ch R = 1 ,75783.66,903.79,1102.89,1153.45
XS GIS Cut Line= 2
1623830.54999323747940.4855978191620602.56873523748852.205495134
#Sta/Elev= 30
       0  323.12  203.67  311.21  363.69  296.47  756.48  281.58 1163.82   271.4
 1214.73  266.86 1309.29  263.18 1447.49  259.93 1854.83  254.93 2043.95   255.6
 2080.32  251.53  2114.2   255.6 2269.44  258.25 2327.63  262.31 2400.37  273.91
 2436.74  276.36  2531.3  272.68 2577.42272.7186 2640.41  270.09 2684.05  271.35
  2727.7  278.05  2782.7 282.307 2858.63  289.43 2938.64   302.2 3025.93  312.15
 3047.75  312.97 3105.94  310.93 3222.32  312.19 3265.97  315.29 3354.27  325.67
#Mann= 5 ,-1 , 0
       0     .05       0 2043.95     .04       0  2114.2     .06       0
 2577.42      .1       0  2782.7     .06       0
Bank Sta=2043.95,2114.2
XS Rating Curve= 0 ,0
Exp/Cntr=0.3,0.1

Type RM Length L Ch R = 1 ,74680.76,958.37,1204.02,653.73
XS GIS Cut Line= 4
1623452.72012587747620.1515798721621889.12604184747591.214724451
1621758.98785815747479.6677098271619707.76220012 747225.58839871
#Sta/Elev= 30
       0   325.2  231.04  311.48  434.07  305.59  700.12  289.19  819.14  284.39
 1064.18  264.16 1204.21  255.81 1573.08  251.03  1628.4  252.24 1633.79  251.81
 1665.28  247.66 1694.24  253.98 1777.59  267.14  1897.5  275.08 1932.77  281.86
 2080.89  290.76 2116.16  291.96 2151.42  290.45 2179.64  294.26 2285.44  298.44
 2370.08  299.63  2504.1     296    2624   296.3 2800.34   303.7 2920.25   305.7
 3004.89  305.14 3117.75  299.94 3251.76   304.9 3343.46  300.85 3802.16  309.18
#Mann= 3 ,-1 , 0
       0     .06       0 1633.79     .04       0 1694.24     .06       0
Bank Sta=1628.4,1694.24
XS Rating Curve= 0 ,0
Exp/Cntr=0.3,0.1

Type RM Length L Ch R = 1 ,73476.74,1074.49,1247.11,1241.75
XS GIS Cut Line= 4
1623288.44627051747258.7490980331622098.70936419746790.931172699
1621860.20907114746900.5123884231620044.03762701746724.859068111
#Sta/Elev= 30
       0   319.4  135.39  313.43  255.74  303.57  323.43  301.35  436.26  294.45
  752.17  280.09  812.35  274.13  857.48  271.36  940.21  267.47 1075.61  263.71
 1363.15  249.41 1370.85  249.54 1417.07  245.41 1440.18  250.15 1451.22  250.39
 1660.43  251.79 1801.09  258.03 1871.42  263.73 1934.71   271.2 1976.91  270.21
 2026.14  281.26 2342.61   300.7 2419.97  300.68 2525.46  298.25 2623.92  290.95
 2659.08  289.62    2856  291.39 2989.62  297.56  3158.4  310.75 3365.54  323.54
#Mann= 3 ,-1 , 0
       0     .05       0 1363.15     .04       0 1451.22     .06       0
Bank Sta=1370.85,1451.22
XS Rating Curve= 0 ,0
Exp/Cntr=0.3,0.1

Type RM Length L Ch R = 1 ,72229.63,1268.99,1676.04,1589.23
XS GIS Cut Line= 3
1623879.83214982747193.0395559071622459.25522782745800.265433893
1620183.67040403745583.155773297
#Sta/Elev= 30
       0  302.66  147.05     298  480.35  297.57  597.99  295.59  735.23  290.42
  843.07  283.57   950.9  279.28 1548.89  263.42  1578.3  264.38 1774.36  259.59
  2024.6  250.92 2404.31  245.48 2826.21  249.05 2833.25  248.49 2847.31  244.45
 2854.34   244.3 2893.04  248.71 2896.53  249.33 2917.63  255.37 2945.75  258.53
 3009.04  262.06 3276.24  283.77 3409.85  287.58 3501.26  287.38 3613.77  290.22
 3712.21  295.01 3782.53   301.7 3873.94  304.21 4077.86  315.55 4275.34   323.7
#Mann= 3 ,-1 , 0
       0     .05       0 2826.21     .04       0 2896.53     .05       0
Bank Sta=2833.25,2893.04
XS Rating Curve= 0 ,0
Exp/Cntr=0.3,0.1

Type RM Length L Ch R = 1 ,70553.59,1667.7,2124,1731.1
XS GIS Cut Line= 3
1624364.44002315746831.6370740831622626.57574974744845.918753132
1621579.99817471743825.425520867
#Sta/Elev= 30
       0  311.61   74.42  308.29  241.86  308.02  558.13  298.34  688.36  290.37
  967.43  277.25 1209.29  275.16 1320.91  272.55 1479.05  255.03 1581.38  250.64
 1841.84  249.11  2074.4  244.18 2241.84  242.43    2493  243.36  2511.6  241.38
 2530.21  238.93 2558.11  238.81 2588.27  241.36 2604.62  242.52 2853.89  242.87
 2951.66  247.92 3010.32   252.9 3117.87  267.94  3147.2  267.13 3450.28  293.09
 3538.27  298.48 3655.59  299.64 3870.68  313.95 3958.68  317.07 4100.55  330.81
#Mann= 3 ,-1 , 0
       0     .05       0  2511.6     .04       0 2588.27     .05       0
Bank Sta=2493,2604.62
XS Rating Curve= 0 ,0
Exp/Cntr=0.3,0.1

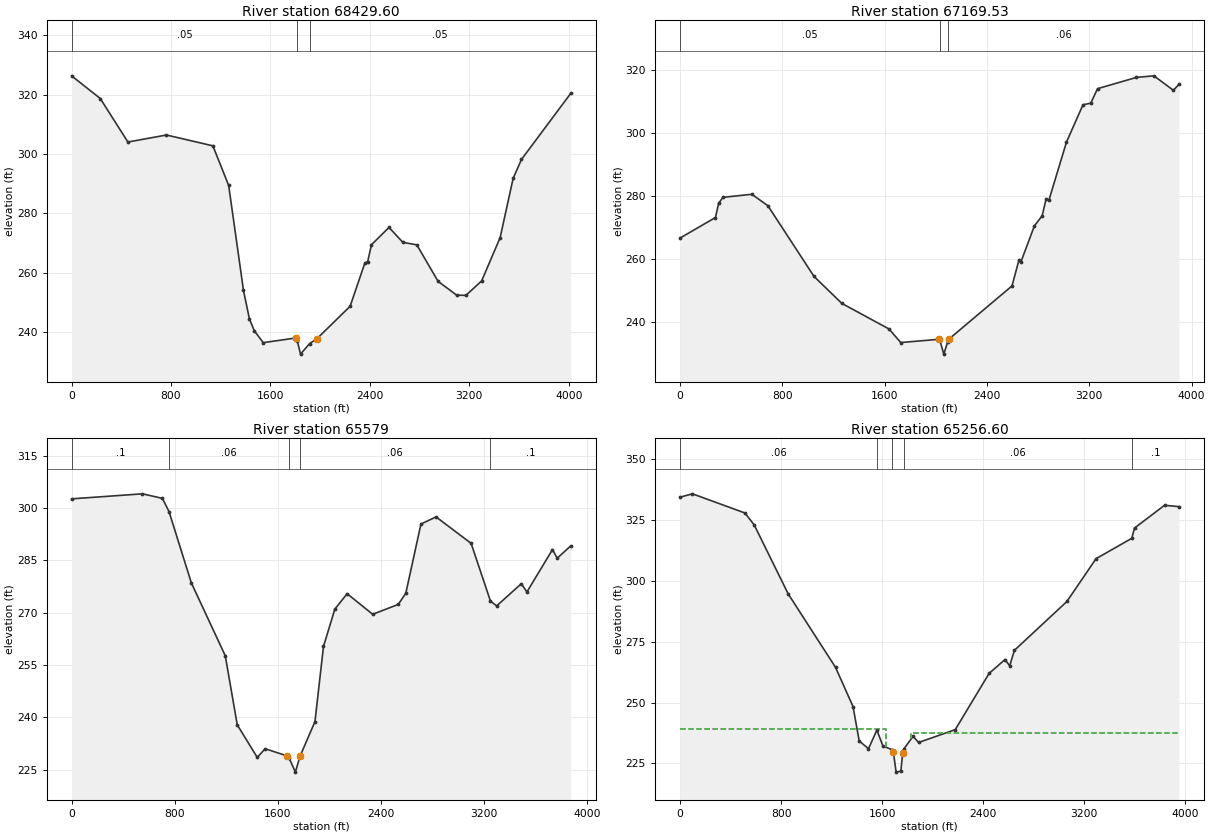
Type RM Length L Ch R = 1 ,68429.60,1114.03,1260.06,1003.27
XS GIS Cut Line= 4
1625703.27194439745517.4462311421624200.09032476744708.888073727
1624032.49552423744502.6175499711622113.88820463743800.784442574
#Sta/Elev= 30
       0  326.37   230.5  318.72  453.06  304.04  763.05  306.41 1136.62  302.76
  1263.8  289.39 1383.02  253.99 1430.71  244.36 1470.46  240.35 1541.99  236.37
 1806.05  237.96 1815.83  236.97 1842.13   232.5 1914.28  236.01 1972.61  237.65
 2240.94  248.63  2360.2  263.29 2382.56  263.67 2412.38  269.39    2554  275.23
  2665.8  270.19  2777.6  269.37 2949.04  257.05 3098.11   252.4 3172.65  252.32
 3299.36  257.19 3448.43  271.82 3552.78  291.77 3619.86  298.16 4015.55  320.41
#Mann= 3 ,-1 , 0
       0     .05       0 1815.83     .04       0 1914.28     .05       0
Bank Sta=1806.05,1972.61
XS Rating Curve= 0 ,0
Exp/Cntr=0.3,0.1

Type RM Length L Ch R = 1 ,67169.53,1270.79,1590.54,1347.26
XS GIS Cut Line= 4
1626409.64952247744917.8466590641624954.26692718 743961.15742518
1624541.72587973743683.9814089091623009.18071637743036.911015123
#Sta/Elev= 30
       0  266.65  276.44  273.16  301.57  277.68  335.08  279.56  561.25  280.53
  686.91  276.88 1047.12  254.48 1264.92  245.91  1633.5   237.8 1725.65   233.5
  2028.4  234.54 2032.67  234.05 2062.13  229.82 2092.77  233.75  2104.3  234.66
  2595.8  251.47 2648.99  259.57 2664.19  258.96 2770.56   270.5 2831.35  273.72
 2861.74  278.94 2884.54  278.72 3021.31  297.07 3150.48  308.93 3211.27  309.43
 3264.46  314.03 3568.39  317.61 3705.17  318.11 3857.13  313.53 3902.23  315.44
#Mann= 3 ,-1 , 0
       0     .05       0 2032.67     .04       0 2092.77     .06       0
Bank Sta=2028.4,2104.3
XS Rating Curve= 0 ,0
Exp/Cntr=0.3,0.1

Type RM Length L Ch R = 1 ,65579   ,394.08,322.39,260.28
XS GIS Cut Line= 4
1627058.00967692743876.1024680581625682.65971416743226.318684369
1625476.38919038742968.480529681 1623550.1778888742358.704128861
#Sta/Elev= 30
       0   302.6  549.68  304.04  704.51  302.74  755.76298.9386  929.03  278.51
 1192.26  257.62 1285.16  237.83    1440  228.52 1501.93  230.98 1673.52  228.91
 1686.91  228.35 1736.27  224.28 1772.13  228.83 1888.03  238.75 1954.11  260.29
 2042.22  270.99 2137.67  275.42 2335.91  269.51 2534.15  272.34 2592.89  275.55
 2710.37  295.39 2827.84  297.42 3099.51  289.85 3249.53273.3094 3297.75  271.92
 3488.65  278.27  3532.7  275.92 3730.95  288.06 3767.66   285.6 3871.72  289.09
#Mann= 5 ,-1 , 0
       0      .1       0  755.76     .06       0 1686.91     .04       0
 1772.13     .06       0 3249.53      .1       0
Bank Sta=1673.52,1772.13
XS Rating Curve= 0 ,0
Exp/Cntr=0.5,0.3

Type RM Length L Ch R = 1 ,65256.60,158.26,137.3,135.71
BEGIN DESCRIPTION:
Under water portion adjusted -2 feet.
 Although the flow is fully expanded with respect to the bridge downstream, ineffective flow limit are coded define ineffective flow areas in backwater ponding areas.
END DESCRIPTION:
XS GIS Cut Line= 3
1627150.15937364743691.803074628 1625700.3374787742825.595925555
1623568.60782811742063.825099409
#Sta/Elev= 30
       0  334.28   97.85  335.65  513.71  327.79   587.1  322.89  856.19  294.59
 1231.28  264.43  1369.9  248.35 1418.83  234.22 1492.22  231.08 1558.92238.6913
 1606.37   232.2 1679.76  230.63 1688.87  229.88 1711.17  221.45 1748.34  221.86
 1763.21  229.21 1770.64  230.83 1844.98  236.15 1889.58  233.63 2179.48  238.88
 2447.09  261.93 2573.46  267.66 2610.63  265.05  2647.8  271.42 3064.08  291.49
 3294.52  309.03 3577.53317.3899  3599.3  321.59 3837.18  330.95 3952.64  330.39
#Mann= 5 ,-1 , 0
       0     .06       0 1558.92     .06       0 1679.76     .04       0
 1770.64     .06       0 3577.53      .1       0
#XS Ineff= 2 , 0
       0    1628  239.07    1830       0  237.69
Permanent Ineff=
       F       F
Bank Sta=1688.87,1763.21
XS Rating Curve= 0 ,0
Exp/Cntr=0.5,0.3