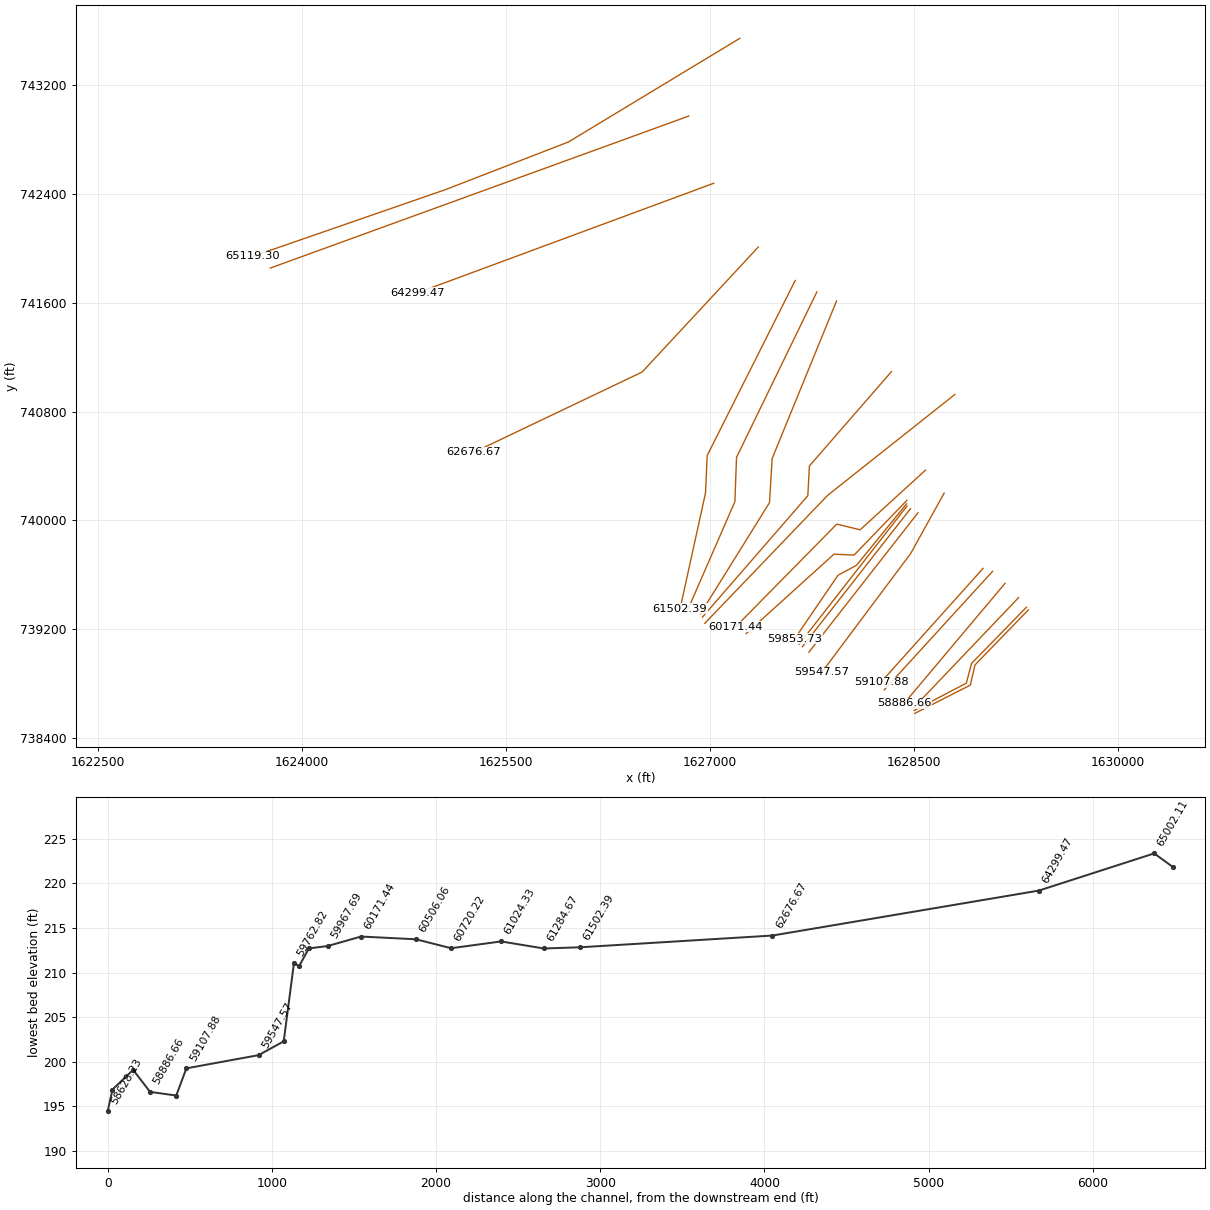
HEC-RAS study LittleElkCreek.prj: Little Elk Creek

--- LittleElkCreek.g01 (geometry) --- (continued)

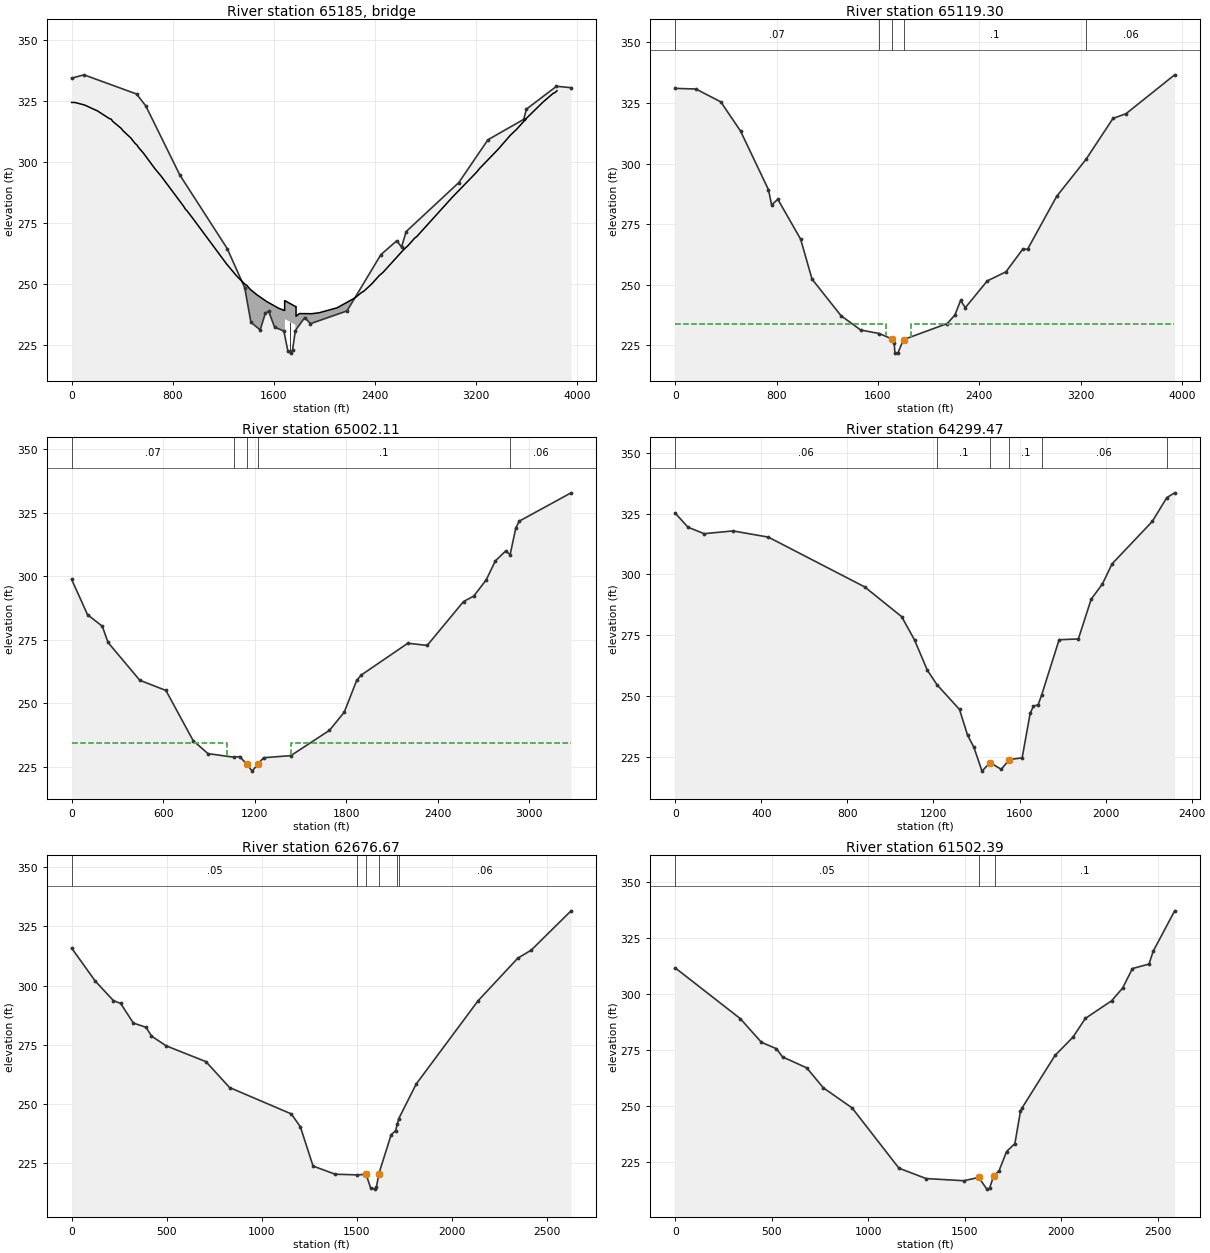
Type RM Length L Ch R = 3 ,65185   ,,,
BEGIN DESCRIPTION:
Telegraph Road  CE050407PF-2.  Top of road from LIDAR. Bridge geometry from bridge survey dimensions and photographs.
END DESCRIPTION:
Bridge Culvert--1,0,-1,-1, 0
Deck Dist Width WeirC Skew NumUp NumDn MinLoCord MaxHiCord MaxSubmerge Is_Ogee
60,46,2.6,0, 60, 60, , , 0.95, 0, 0,0,,
       0   25.51  102.03  204.07   297.6   314.6   323.1  391.13  408.13  467.65
  501.66  518.67  527.17  569.68     659  707.79  886.69  902.95  911.08  951.74
 1226.59 1304.41 1366.66 1390.01 1413.35 1467.83 1545.64 1639.02  1681.9  1685.7
 1685.71    1688    1771    1776 1776.01 1802.44  1901.2 1960.44 2101.13 2241.82
 2301.06 2308.46  2375.1 2434.34 2463.96 2626.87 2663.89 2715.72 2730.53 3011.91
 3204.44 3226.65 3374.75 3471.01 3522.84  3604.3 3730.18 3811.63 3826.44 3841.25
  324.33  324.32  323.28  320.87  317.74  317.43  316.66  313.74  312.65   309.8
  307.56   306.8  306.01  303.45  297.18  294.15  281.74  280.35  280.05  277.31
   258.1   253.3  250.07  249.16  247.72  245.43  242.67  239.95   239.1  239.06
  243.06  243.06   240.7   240.7   236.7  237.79  237.74  238.15  240.16  244.22
  246.71  246.77  249.94  253.38  254.66  263.96  265.73  268.77  269.31  285.43
  295.71  297.16   305.1  310.83  313.38  318.08  324.47  328.09  328.39  329.11
                                                                                
                                                                                
                                                                                
           235.5   233.2
                                                                                
                                                                                
      30   55.51  132.03  234.07   327.6   344.6   353.1  421.13  438.13  497.65
  531.66  548.67  557.17  599.68     689  737.79  916.69  932.95  941.08  981.74
 1256.59 1334.41 1396.66 1420.01 1443.35 1497.83 1575.64 1669.02  1711.9  1715.7
 1715.71    1718    1801    1806 1806.01 1832.44  1931.2 1990.44 2131.13 2271.82
 2331.06 2338.46  2405.1 2464.34 2493.96 2656.87 2693.89 2745.72 2760.53 3041.91
 3234.44 3256.65 3404.75 3501.01 3552.84  3634.3 3760.18 3841.63 3856.44 3871.25
  324.33  324.32  323.28  320.87  317.74  317.43  316.66  313.74  312.65   309.8
  307.56   306.8  306.01  303.45  297.18  294.15  281.74  280.35  280.05  277.31
   258.1   253.3  250.07  249.16  247.72  245.43  242.67  239.95   239.1  239.06
  243.06  243.06   240.7   240.7   236.7  237.79  237.74  238.15  240.16  244.22
  246.71  246.77  249.94  253.38  254.66  263.96  265.73  268.77  269.31  285.43
  295.71  297.16   305.1  310.83  313.38  318.08  324.47  328.09  328.39  329.11
                                                                                
                                                                                
                                                                                
           235.5   233.2
                                                                                
                                                                                
Pier Skew, UpSta & Num, DnSta & Num=  ,1730, 2 ,1758, 2 , 0 , 0 , 0 ,,
       2       2
       0     240
       2       2
       0     240
BR Coef=-1 , 1 , 0 ,, 0 ,,,0.8,0,0.5,0,
WSPro=,,,, 1 ,,,, 0 ,,,, 0 ,,,,-1 ,-1 ,-1 , 0 , 0 , 0 , 0 , 0
BR U #Sta/Elev= 30
       0  334.28   97.85  335.65  513.71  327.79   587.1  322.89  856.19  294.59
 1231.28  264.43  1369.9  248.35 1418.83  234.22 1492.22  231.08 1532.99  237.91
 1558.92 238.691 1606.37   232.2 1679.76  230.63 1711.17  222.45 1733.47  221.58
 1748.34  222.86 1770.64  230.83 1844.98  236.15 1889.58  233.63 2179.48  238.88
 2447.09  261.93 2573.46  267.66 2610.63  265.05  2647.8  271.42 3064.08  291.49
 3294.52  309.03 3577.53  317.39  3599.3  321.59 3837.18  330.95 3952.64  330.39
BR U #Mann= 5
       0     .06 1558.92     .06 1679.76    .035 1770.64     .06 3577.53      .1
BR D #Sta/Elev= 30
       0  331.04  163.62  330.79  359.96  325.48   515.4  313.47  736.29  289.21
  760.83  282.95  809.91  285.28   989.9  268.84 1079.89  252.36 1308.95  237.23
 1464.39  231.34  1610.8 229.882 1712.09  227.63 1728.28  225.93 1734.62   221.8
 1757.14  221.82 1802.19  227.39 2147.55  234.01 2207.61  237.53 2252.66  243.52
  2290.2  240.57 2462.65  251.59 2610.81  255.36 2744.15  264.77 2781.19  264.66
 3010.84  286.49 3242.49 301.758 3455.31  318.64 3559.03  320.62 3942.23  336.64
BR D #Mann= 5
       0     .07  1610.8      .1 1712.09    .035 1802.19      .1 3242.49     .06
BC Design=,, 0 ,, 0 ,,,,,,
BC Use User HTab Curves=0
BC User HTab FreeFlow(D)= 0

Type RM Length L Ch R = 1 ,65119.30,119.85,117.19,139.05
BEGIN DESCRIPTION:
Under water portion adjusted -2 feet.
END DESCRIPTION:
XS GIS Cut Line= 4
1627217.73581789743544.3635598871625958.35662952742782.592733741
1625055.28960171742432.4238862541623636.18427238741940.958837107
#Sta/Elev= 30
       0  331.04  163.62  330.79  359.96  325.48   515.4  313.47  736.29  289.21
  760.83  282.95  809.91  285.28   989.9  268.84 1079.89  252.36 1308.95  237.23
 1464.39  231.34  1610.8229.8823 1712.09  227.63 1728.28  225.93 1734.62   221.8
 1757.14  221.82 1802.19  227.39 2147.55  234.01 2207.61  237.53 2252.66  243.52
  2290.2  240.57 2462.65  251.59 2610.81  255.36 2744.15  264.77 2781.19  264.66
 3010.84  286.49 3242.49301.7575 3455.31  318.64 3559.03  320.62 3942.23  336.64
#Mann= 5 ,-1 , 0
       0     .07       0  1610.8      .1       0 1712.09     .04       0
 1802.19      .1       0 3242.49     .06       0
#XS Ineff= 2 ,-1
       0    1660  233.75    1860 3938.63  233.75
Permanent Ineff=
       F       F
Bank Sta=1712.09,1802.19
XS Rating Curve= 0 ,0
Exp/Cntr=0.5,0.3

Type RM Length L Ch R = 1 ,65002.11,671.65,702.64,671.25
XS GIS Cut Line= 2
1626842.99371797742973.0354402811623765.19384776741854.952453509
#Sta/Elev= 30
       0  298.77  104.27   284.9  201.08  280.36  238.32  274.01  446.85  259.11
  618.15   255.1  796.89  235.36  893.71  230.26  1062.6228.8493 1102.24  229.08
  1148.4  226.08 1184.17  223.37  1221.4   226.2 1258.64  228.64 1437.38  229.47
  1690.6  239.42 1787.42  246.57 1869.35  259.11 1899.14  261.18 2204.49  273.68
  2331.1  272.81 2569.42  290.07 2636.44  292.21 2718.37  298.61 2777.95  306.05
 2844.97  309.91 2875.09308.5591    2912  318.96 2934.34  321.68 3274.59  332.83
#Mann= 5 ,-1 , 0
       0     .07       0  1062.6      .1       0  1148.4     .04       0
  1221.4      .1       0 2875.09     .06       0
#XS Ineff= 2 ,-1
       0 1018.91 234.448  1441.4 3274.59234.2736
Permanent Ineff=
       F       F
Bank Sta=1148.4,1221.4
XS Rating Curve= 0 ,0
Exp/Cntr=0.3,0.1

Type RM Length L Ch R = 1 ,64299.47,1315.06,1622.8,1361.68
XS GIS Cut Line= 2
1627025.67648007742478.3799068481624849.04789649741673.438015565
#Sta/Elev= 30
       0  325.19   59.71  319.39  134.34  316.75  268.68  317.88  432.87  315.33
  880.67  294.87 1052.33  282.65 1112.04  273.08 1171.74  260.62 1217.21 254.607
 1321.01  244.54 1358.33  234.02 1388.18  228.93  1425.5   219.2 1462.81   222.7
 1515.06  219.93 1552.37  223.97 1612.08  224.65  1649.4  242.98 1664.33  245.82
 1686.72  246.52 1702.93250.5317 1783.74  273.17  1873.3  273.51 1933.01  289.87
 1985.25  296.12 2030.03  304.37 2216.62  321.76 2284.27331.5674 2320.71  333.53
#Mann= 6 ,-1 , 0
       0     .06       0 1217.21      .1       0 1462.81     .04       0
 1552.37      .1       0 1702.93     .06       0 2284.27      .1       0
Bank Sta=1462.81,1552.37
XS Rating Curve= 0 ,0
Exp/Cntr=0.3,0.1

Type RM Length L Ch R = 1 ,62676.67,967.11,1174.28,1206.32
XS GIS Cut Line= 3
1627354.22419085742010.199419066 1626499.7359802741090.502593696
1625259.73253489740498.879949689
#Sta/Elev= 30
       0  315.87  124.21  301.97  219.76  293.74  257.98  292.52  324.87  284.25
  391.75  282.45  420.42  278.76  496.86  274.66  707.07  267.96  831.28  257.04
 1156.16  245.91 1203.93   240.5  1270.9  223.91 1387.24  220.45  1502.9220.1796
 1550.11  220.41 1573.38  214.81 1596.64  214.16  1604.4  214.98 1617.51  220.64
 1619.11  221.13 1681.96  237.09 1705.23  238.84 1715.35241.7849 1721.66243.8359
 1813.81   258.5 2139.55  293.64 2348.96  311.64 2418.77  314.97 2629.29   331.6
#Mann= 6 ,-1 , 0
       0     .05       0  1502.9      .1       0 1550.11     .04       0
 1619.11      .1       0 1715.35     .06       0 1721.66     .06       0
Bank Sta=1550.11,1617.51
XS Rating Curve= 0 ,0
Exp/Cntr=0.3,0.1

Type RM Length L Ch R = 1 ,61502.39,216.04,217.72,218.63
XS GIS Cut Line= 4
1627625.27605219741763.7886360291626978.29644136740477.119360179
1626965.40453361740199.9433438931626778.47187145739349.077433482
#Sta/Elev= 30
       0  311.67  336.91  289.03   446.6  278.45  524.95  275.54  556.29   271.9
  681.66  267.01  767.84  258.09  916.71  249.14  1159.6   222.2 1300.63  217.56
 1496.23  216.59 1573.32  218.07 1615.36  212.84 1629.38  213.22  1650.4  218.67
 1657.41  219.28 1678.43  221.01 1717.65  229.64 1760.65  233.15 1789.32  247.54
 1796.48  248.92 1968.49  272.53 2061.66  280.72 2126.17  289.12 2262.34  296.99
 2319.68  302.73 2369.84  311.37 2455.85  313.37 2477.35  319.07 2588.81  337.15
#Mann= 3 ,-1 , 0
       0     .05       0 1573.32     .04       0 1657.41      .1       0
Bank Sta=1573.32,1650.4
XS Rating Curve= 0 ,0
Exp/Cntr=0.3,0.1

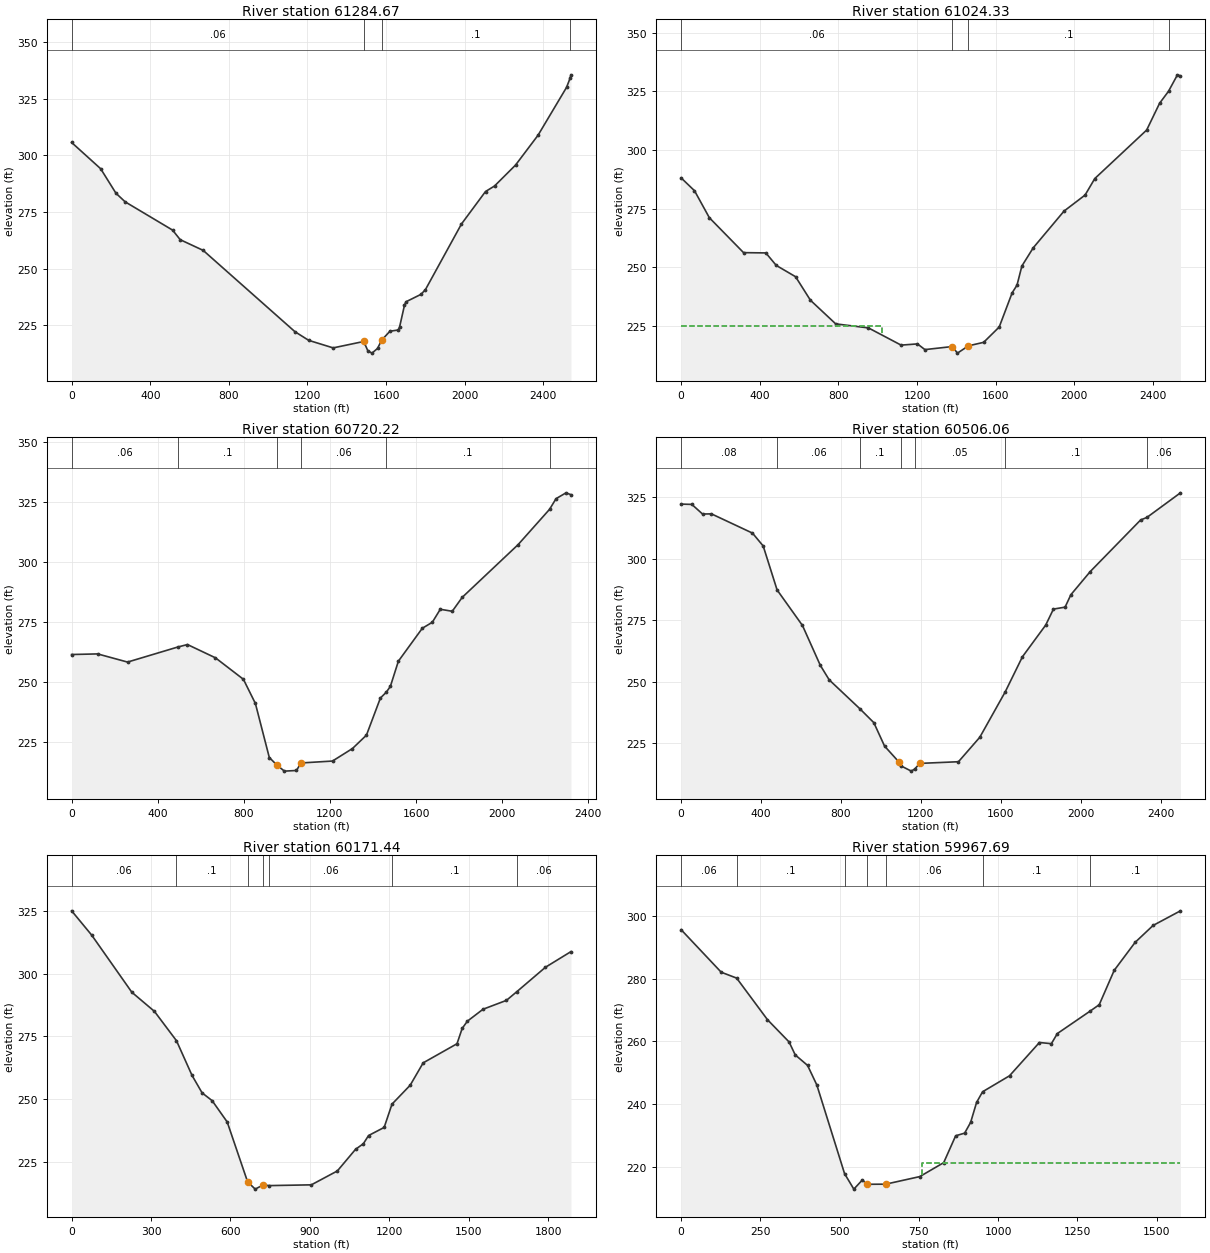
Type RM Length L Ch R = 1 ,61284.67,262.52,260.35,257.77
XS GIS Cut Line= 4
 1627784.5596796741679.8228351921627193.57323805740462.625594586
1627181.83178554740137.7787426111626837.41584611739347.187608853
#Sta/Elev= 30
       0  305.63  147.85  294.04  225.66  283.23  272.35  279.45  513.58  266.98
  552.48  262.75  669.21  258.04  1136.1  222.17 1206.13  218.35 1330.63  215.02
 1486.17  217.85 1507.18  213.72  1528.2  212.71 1556.22  214.77 1577.23  218.41
 1619.26  222.37 1661.28  222.91 1668.29  224.12 1693.41  233.82 1701.05  235.36
  1777.4  238.64 1800.31  240.76 1983.56   269.7 2105.72     284 2151.54  286.43
 2258.43  295.66 2372.97  308.83 2518.04  329.94 2536.18  334.01  2540.5  335.48
#Mann= 4 ,-1 , 0
       0     .06       0 1486.17     .04       0 1577.23      .1       0
 2536.18     .06       0
Bank Sta=1486.17,1577.23
XS Rating Curve= 0 ,0
Exp/Cntr=0.3,0.1

Type RM Length L Ch R = 1 ,61024.33,284.7,304.1,263.72
XS GIS Cut Line= 4
1627929.37092689 741613.287937791627455.79901013740454.797959596
1627436.22992265740129.9511076211626927.43364845739311.963251397
#Sta/Elev= 30
       0  288.16   68.06  282.69  143.68  271.18  317.62  256.31  431.05  256.19
  483.99  250.87   582.3  246.05  657.92  236.03  786.48  225.96  952.85  224.25
 1119.22  216.91  1202.4  217.43 1240.21     215 1379.63   216.3 1405.82   213.5
 1461.93  216.61 1539.07   218.1  1618.2  224.61 1684.15   239.2 1708.88  242.47
 1733.61  250.62 1791.32  258.36 1947.94     274 2055.11  280.84 2104.57  287.87
 2368.37  308.53 2434.32  319.96 2479.58  325.05    2525  332.06  2540.3  331.61
#Mann= 4 ,-1 , 0
       0     .06       0 1379.63     .04       0 1461.93      .1       0
 2479.58     .06       0
#XS Ineff= 1 ,-1
       0 1020.54225.0656
Permanent Ineff=
       F
Bank Sta=1379.63,1461.93
XS Rating Curve= 0 ,0
Exp/Cntr=0.3,0.1

Type RM Length L Ch R = 1 ,60720.22,260.98,214.16,103.13
XS GIS Cut Line= 4
 1628332.4941287741092.7502111051627729.76623467740400.004514679
1627718.02478218740180.8307350281626943.08891843739288.480346426
#Sta/Elev= 30
       0  261.44  120.62  261.69   259.8  258.28  493.61  264.58  538.16   265.6
  668.06  260.06  797.96  251.09  853.63     241  918.25  218.43   953.3  215.29
  988.35  212.74 1044.43  213.01 1065.46  216.15  1211.9  216.95 1304.61  222.18
 1369.51  227.76 1434.41  243.27 1462.04  245.73 1480.77  248.15 1517.85  258.65
  1629.1  272.41 1675.46   274.9 1712.54  280.33 1768.17   279.5 1814.53  285.32
 2074.12  307.33 2220.32  322.09 2250.27  326.52 2296.62  328.96  2319.6  328.18
#Mann= 6 ,-1 , 0
       0     .06       0  493.61      .1       0   953.3     .04       0
 1065.46     .06       0 1462.04      .1       0 2220.32     .06       0
Bank Sta=953.3,1065.46
XS Rating Curve= 0 ,0
Exp/Cntr=0.3,0.1

Type RM Length L Ch R = 1 ,60506.06,381.14,334.62,212.64
XS GIS Cut Line= 3
1628799.83411807740925.9919736391627863.87372087740183.875407085
1626959.96693794739242.184956133
#Sta/Elev= 30
       0  322.24    53.6  322.12   107.2  318.21  151.87  318.27  357.34  310.45
  410.94  305.21  480.46287.3628  607.47  272.92   696.8  256.73  741.47  250.81
  893.67239.1734  964.81  233.43 1018.41  223.92 1089.87   217.5 1098.81  215.95
 1152.41  213.74 1170.27  214.65 1194.47  216.88 1388.53  217.56 1495.26   227.5
  1622.1245.8774 1708.72  260.21 1825.16  273.08 1863.97  279.58 1922.19  280.37
  1951.3  285.43 2048.32  294.84  2300.6  315.81 2331.79 316.818 2499.77  326.82
#Mann= 7 ,-1 , 0
       0     .08       0  480.46     .06       0  893.67      .1       0
 1098.81     .04       0 1170.27     .05       0  1622.1      .1       0
 2331.79     .06       0
Bank Sta=1089.87,1194.47
XS Rating Curve= 0 ,0
Exp/Cntr=0.3,0.1

Type RM Length L Ch R = 1 ,60171.44,190.51,203.76,190.65
XS GIS Cut Line= 4
1628582.82212886740368.5966100841628102.55135083739930.254233271
1627931.02607293739972.1826345181627187.74986883739217.471411869
#Sta/Elev= 30
       0  325.08   75.82  315.38  227.45  292.59  312.75  284.97  396.08  273.25
  454.91  259.39  492.82  252.45  530.73  249.35  587.59  240.85  664.65  216.96
  693.47  214.05   722.3  215.68  747.08  215.46  905.41  215.76 1003.66   221.3
 1072.43  229.94  1101.9  232.16 1121.55  235.43  1180.5  238.67 1210.11  247.96
 1278.75   255.5 1327.87  264.43  1455.6  272.05 1475.25  278.18  1494.9  281.06
 1553.85  285.81 1642.27  289.35 1681.25  292.79 1789.64  302.56 1886.08  308.81
#Mann= 7 ,-1 , 0
       0     .06       0  396.08      .1       0  664.65     .04       0
   722.3      .1       0  747.08     .06       0 1210.11      .1       0
 1681.25     .06       0
#XS Ineff= 1 ,-1
 1011.01 1011.41222.1393
Permanent Ineff=
       F
Bank Sta=664.65,722.3
XS Rating Curve= 0 ,0
Exp/Cntr=0.3,0.1

Type RM Length L Ch R = 1 ,59967.69,79.55,113.95,144.55
XS GIS Cut Line= 4
1628445.66443956740145.7330232261628057.94279973739744.286723569
1627910.40270674739751.1490534841627265.34369531739167.851011276
#Sta/Elev= 30
       0  295.56  126.51  282.02  175.17  280.15  272.49  266.91  340.61  259.83
  360.07   255.7     399  252.36   428.2  246.13  515.78  217.89  544.98  212.98
  572.13  215.93  585.45  214.52  645.63  214.56     753  216.97   828.5  221.41
  866.25  229.96  894.56   230.8  913.44  234.22  932.31  240.59  951.19  243.97
 1036.12  249.05  1130.5  259.65 1168.25  259.28 1187.12   262.5 1290.94  269.67
 1319.25  271.68 1366.44  282.61  1432.5  291.52 1489.12   296.9 1575.49  301.56
#Mann= 7 ,-1 , 0
       0     .06       0  175.17      .1       0  515.78     .06       0
  585.45     .04       0  645.63     .06       0  951.19      .1       0
 1290.94      .1       0
#XS Ineff= 2 , 0
                          760.49          221.36
Permanent Ineff=
       F       F
Bank Sta=585.45,645.63
XS Rating Curve= 0 ,0
Exp/Cntr=0.3,0.1

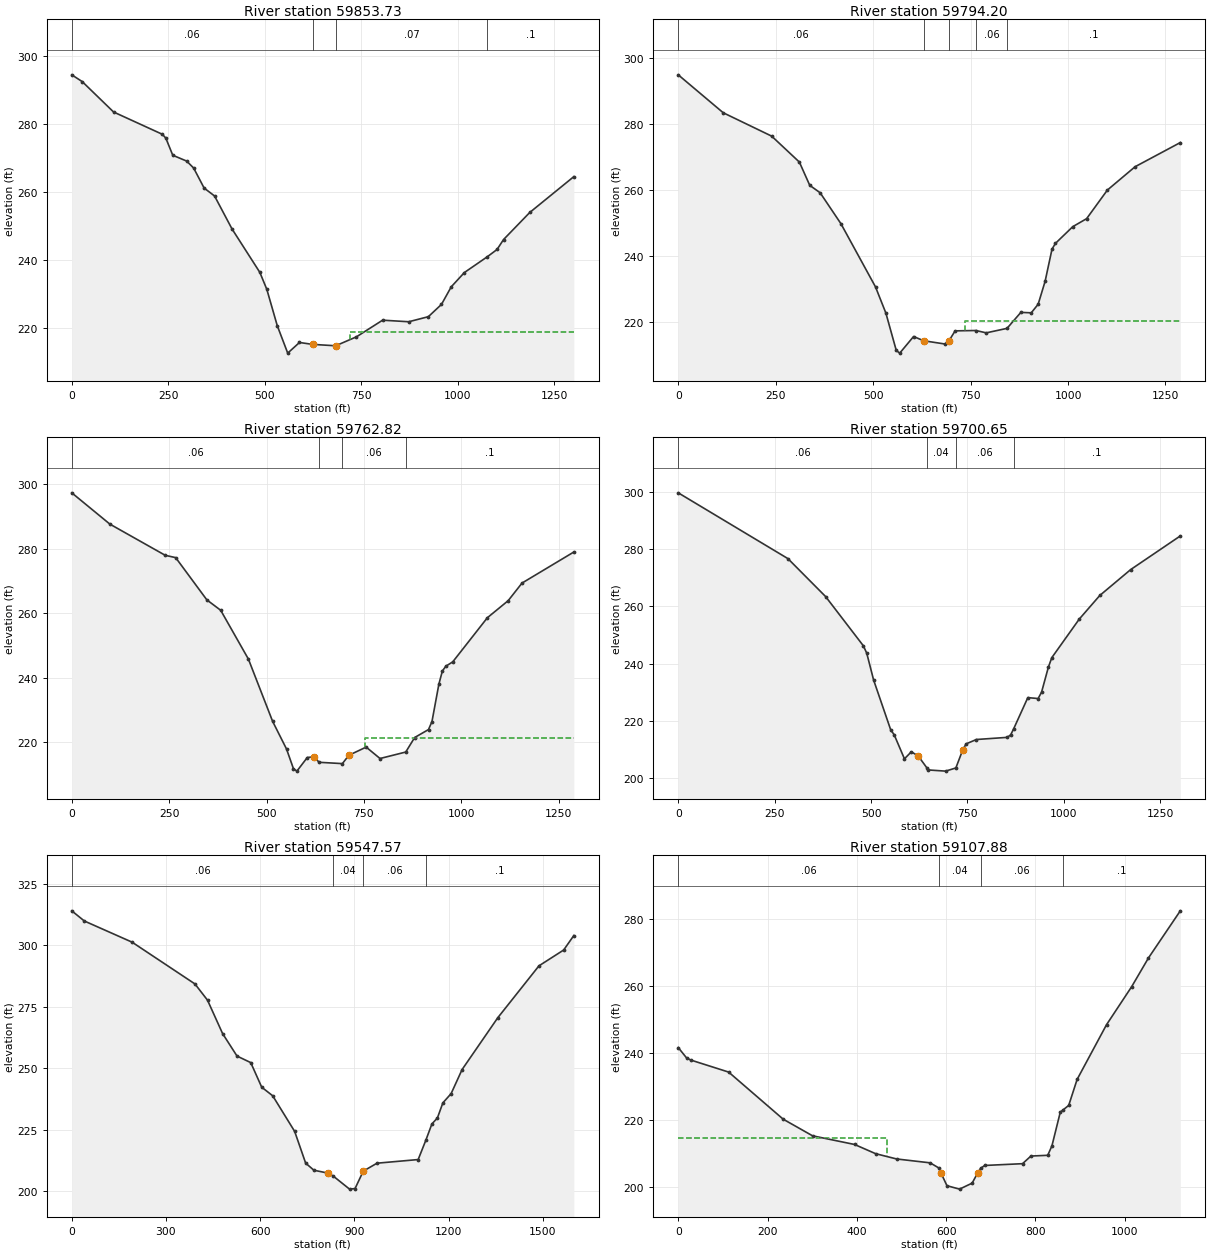
Type RM Length L Ch R = 1 ,59853.73,27.1,59.53,76.15
XS GIS Cut Line= 4
1628443.76366432740121.1495133641628076.33312204739669.687770844
1627939.57646279 739595.542594151627622.18485056 739130.10819675
#Sta/Elev= 30
       0  294.49   27.08   292.5   108.3  283.57  234.66  277.02  243.68   275.9
  261.73  270.86  297.84  269.14  315.89  267.09  342.96  261.22  370.04  258.89
  415.17  249.22  487.37  236.44  505.42  231.46  532.49  220.78  559.57  212.72
  590.05  215.85  623.96  215.29  683.94  214.88  737.65  217.51  805.43   222.4
  873.21  221.94  924.05  223.43  957.94  227.03  983.36  232.21 1017.25  236.39
 1076.55  241.02 1101.97  243.17 1118.92   246.1  1186.7  254.04    1301  264.58
#Mann= 4 ,-1 , 0
       0     .06       0  623.96     .04       0  683.94     .07       0
 1076.55      .1       0
#XS Ineff= 2 , 0
                          720.74          218.85
Permanent Ineff=
       F       F
Bank Sta=623.96,683.94
XS Rating Curve= 0 ,0
Exp/Cntr=0.3,0.1

Type RM Length L Ch R = 1 ,59794.20,32.74,31.38,31.34
XS GIS Cut Line= 2
 1628447.0590055 740104.672807411627654.71701382739089.185887754
#Sta/Elev= 30
       0  294.88  115.42  283.41  239.73  276.34  310.75   268.5  337.39  261.47
  364.03  259.22   417.3  249.88  506.09  230.75  532.72  222.83  559.36  211.54
  568.24  210.73  603.75  215.75  629.72  214.47  683.66   213.5  694.51  214.45
   710.3  217.46  763.57  217.57   790.2  216.86  843.48  218.22  878.99  223.05
  905.63  222.92  923.39  225.52  941.14  232.43   958.9  242.18  967.78  243.93
 1012.17  248.97 1047.69  251.39 1100.96  260.04 1171.99  267.09 1288.03   274.4
#Mann= 5 ,-1 , 0
       0     .06       0  629.72     .04       0  694.51      .1       0
  763.57     .06       0  843.48      .1       0
#XS Ineff= 2 , 0
                           736.3          220.42
Permanent Ineff=
       F       F
Bank Sta=629.72,694.51
XS Rating Curve= 0 ,0
Exp/Cntr=0.3,0.1

Type RM Length L Ch R = 1 ,59762.82,65.16,62.17,62.93
BEGIN DESCRIPTION:
Upstream side of rapids? Channel inverts are unknown.  This is an approximate study reach.
END DESCRIPTION:
XS GIS Cut Line= 2
1628472.91346702740085.4262369721627678.33724748739070.690359592
#Sta/Elev= 30
       0  297.34    97.8  287.64  240.05  277.96  266.72  277.25  346.74  264.15
   382.3  260.92  453.42  245.79  515.66  226.46  551.22  217.92     569  211.82
  577.89  211.05  604.57  215.27  622.35  215.51  634.74  213.79  694.67  213.38
  711.25  215.96  755.71   218.5  791.27  214.96  857.32  216.97  880.18  221.47
  915.74  223.94  924.63  226.43  942.41  238.05   951.3  242.09  960.19  243.58
  977.98  244.93 1066.88  258.62 1120.23   263.9 1155.79  269.36 1288.81  278.99
#Mann= 4 ,-1 , 0
       0     .06       0  634.74     .04       0  694.67     .06       0
  857.32      .1       0
#XS Ineff= 1 ,-1
  751.55 1288.52221.3693
Permanent Ineff=
       F
Bank Sta=622.35,711.25
XS Rating Curve= 0 ,0
Exp/Cntr=0.3,0.1

Type RM Length L Ch R = 1 ,59700.65,151.52,153.08,153.82
BEGIN DESCRIPTION:
Downstream side of rapids? Channel inverts are unknown.  This is an approximate study reach.
END DESCRIPTION:
XS GIS Cut Line= 2
1628528.18500343740055.5885752291627725.85241717739030.168391824
#Sta/Elev= 30
       0  299.81  284.42  276.76  382.19  263.46  479.96  246.23  488.85  243.63
  506.62  234.24  551.06  216.74  559.95  215.06  586.62  206.61  604.39  209.06
  622.17  207.64  644.23  203.55  648.83  202.71  693.27   202.3  719.94  203.41
  737.71  209.71   746.6  211.86  773.27  213.38  853.26  214.13  862.15  215.02
  870.13  217.21  906.59  228.06  933.25  227.73  942.14  229.94  959.92  238.75
  968.81  242.07 1039.91  255.56 1093.24  263.85 1173.23  272.91 1302.01  284.71
#Mann= 4 ,-1 , 0
       0     .06       0  644.23     .04       0  719.94     .06       0
  870.13      .1       0
Bank Sta=622.17,737.71
XS Rating Curve= 0 ,0
Exp/Cntr=0.3,0.1

Type RM Length L Ch R = 1 ,59547.57,455.86,439.69,439
XS GIS Cut Line= 3
1628720.65411979740200.0658067761628473.75773846739755.172527075
1627820.69623052738882.195229486
#Sta/Elev= 30
       0  313.96   40.03  309.82  192.14  301.21  392.28  284.22  432.31  277.62
  480.34  264.03  526.29  254.88     570  252.22  604.97  242.21  639.94  238.72
  709.87  224.23  744.84  211.34  771.07  208.44  814.78   207.3  832.26  206.11
  884.71  200.75   902.2  200.99  928.42  208.07  972.13   211.3 1103.26  212.78
 1127.95220.7354 1146.97  227.27 1164.46  229.69 1181.94  235.85 1208.17   239.6
 1243.13   249.4 1356.78  270.47 1487.91  291.58 1566.59  298.02 1599.03  303.92
#Mann= 4 ,-1 , 0
       0     .06       0  832.26     .04       0  928.42     .06       0
 1127.95      .1       0
Bank Sta=814.78,928.42
XS Rating Curve= 0 ,0
Exp/Cntr=0.3,0.1

Type RM Length L Ch R = 1 ,59107.88,77.9,61.77,60.18
BEGIN DESCRIPTION:
Left ineffetive flow limit placed to limit flow in the bulging backwater area.
END DESCRIPTION:
XS GIS Cut Line= 2
1629006.62204717739646.4865696281628255.70391306738809.441624403
#Sta/Elev= 30
       0   241.5   18.81  238.39   28.21  237.77  112.85  234.19   235.1  220.13
  300.93  215.17  394.97  212.59  441.99  209.85  489.01  208.27  564.24  207.11
  583.05  205.63  588.73  204.02  601.86  200.29  630.07  199.27  658.28  201.06
  670.36  204.02  677.09  205.46  686.49  206.33  771.13  206.86  789.94  209.14
  827.55  209.36  836.96  212.17  855.76  222.27  861.37222.8364  874.57  224.25
  893.38     232  959.21  248.31 1015.63  259.68 1053.25  268.25 1124.51  282.29
#Mann= 4 ,-1 , 0
       0     .06       0  583.05     .04       0  677.09     .06       0
  861.37      .1       0
#XS Ineff= 1 ,-1
       0  466.59214.6176
Permanent Ineff=
       F
Bank Sta=588.73,670.36
XS Rating Curve= 0 ,0
Exp/Cntr=0.5,0.3

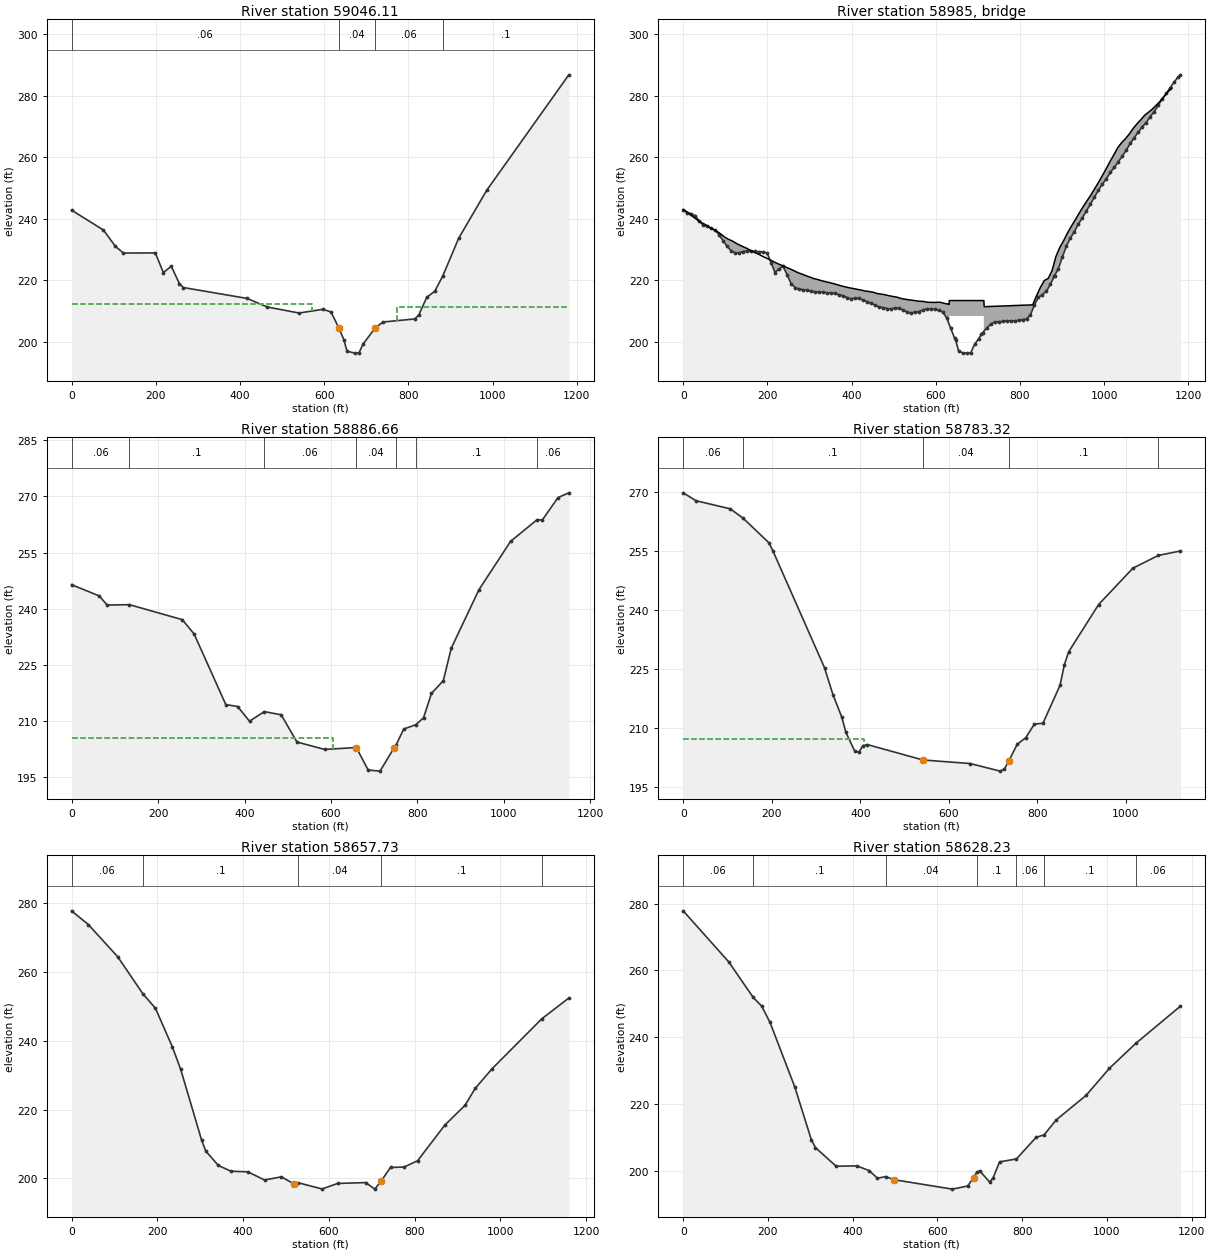
Type RM Length L Ch R = 1 ,59046.11,178.08,159.45,158.3
BEGIN DESCRIPTION:
Under water portion adjusted as per bridge inspection notes.
END DESCRIPTION:
XS GIS Cut Line= 2
1629076.60008119739624.9548668411628279.92707868738752.920904636
#Sta/Elev= 30
       0  242.78   75.85  236.29   104.3  230.97  123.26  228.81  199.11  228.84
  218.07  222.45  237.03   224.5     256  218.89  265.48  217.58  417.18  214.03
  464.59  211.25  540.44  209.28  597.33  210.48  616.29  209.63  635.25  204.33
  647.16  200.49  654.22  196.86  673.18  196.22  682.66  196.26  692.14  199.09
  720.59  204.32  739.55  206.35   815.4  207.35  824.88  208.68  843.84  214.42
  862.81  216.36  881.97221.3906  919.69  233.66  986.06  249.22 1181.16  286.84
#Mann= 4 ,-1 , 0
       0     .06       0  635.25     .04       0  720.59     .06       0
  881.97      .1       0
#XS Ineff= 2 , 0
       0     572  212.17     774       0  211.34
Permanent Ineff=
       F       F
Bank Sta=635.25,720.59
XS Rating Curve= 0 ,0
Exp/Cntr=0.5,0.3

Type RM Length L Ch R = 3 ,58985   ,,,
BEGIN DESCRIPTION:
Providence Road  CE050407PF-1.  Geometry from general dimensions reported in bridge inspeaction.  Top of road elevation estimated from LIDAR bridge approaches.
END DESCRIPTION:
Bridge Culvert--1,0,-1,-1, 0
Deck Dist Width WeirC Skew NumUp NumDn MinLoCord MaxHiCord MaxSubmerge Is_Ogee
60,18,2.6,0, 111, 111, , , 0.95, 0, 0,0,,
       0    9.77   19.54   29.31   39.08   48.85   58.62   68.39   78.16   87.93
    97.7  107.47  117.24  127.01  136.78  142.75  152.04  161.33  170.62  179.91
   189.2  198.49  207.79  217.08  226.37  235.66  244.95  254.24  263.53  272.82
  282.11   291.4  300.69  309.99  319.28  328.57  339.23  348.56   357.9  367.23
  376.57   385.9  395.24  404.57  413.91  423.24  432.58  441.91  451.25  460.59
  469.92  479.26  488.59  497.93  507.26   516.6  522.29  532.03  541.78  551.53
  561.28  571.03  580.78  590.52  600.27  610.02  619.77  629.52     631   631.9
     632     714   714.1     715  830.17  839.35  848.53  857.71  866.89  876.07
  885.25  894.43   903.6  912.78  921.96  931.14  940.32   949.5  958.68  967.86
  977.04  986.22  995.39 1004.57 1013.75 1022.93 1032.11 1041.29 1050.47 1059.65
 1068.83 1078.01 1087.18 1096.36 1105.54 1114.72  1123.9 1133.08 1142.26 1151.44
  1161.2
  242.99  242.15  241.06  240.03  239.02  238.35  237.55  236.69  236.02  235.16
  234.07  233.29  232.69  231.89  231.22  230.84  230.29  229.53  228.94  228.38
  227.69  227.11  226.51  225.83  225.24  224.71  224.16  223.63  223.03   222.4
  221.95  221.45  220.98  220.49  220.19   219.8  219.44  219.15  218.82  218.44
  218.08  217.76  217.47  217.24  216.98  216.74  216.43  216.27  216.05  215.63
  215.45  215.23  214.92  214.68  214.46  214.05  213.87  213.66  213.48   213.3
  213.11  213.05  212.78  212.74  212.74   212.8  212.44  212.17   212.1   212.1
  213.34  213.34  213.34  211.34  211.94  214.94  217.66  219.86  220.54  223.04
  227.66  230.63  232.82  235.34  237.53  239.59  241.75  243.79  245.73  247.61
  249.68  251.78  253.96  256.24   258.6   260.8  263.13  264.74  266.06  267.58
   269.4   270.9  272.25  273.73  274.69  275.73  276.98  278.28  279.75  281.32
  282.56
                                                                                
                                                                                
                                                                                
                                                                                
                                                                                
                                                                                
                                                                                
   208.3   208.3
                                                                                
                                                                                
                                                                                
        
      33   42.77   52.54   62.31   72.08   81.85   91.62  101.39  111.16  120.93
   130.7  140.47  150.24  160.01  169.78  175.75  185.04  194.33  203.62  212.91
   222.2  231.49  240.79  250.08  259.37  268.66  277.95  287.24  296.53  305.82
  315.11   324.4  333.69  342.99  352.28  361.57  372.23  381.56   390.9  400.23
  409.57   418.9  428.24  437.57  446.91  456.24  465.58  474.91  484.25  493.59
  502.92  512.26  521.59  530.93  540.26   549.6  555.29  565.03  574.78  584.53
  594.28  604.03  613.78  623.52  633.27  643.02  652.77  662.52     664   664.9
     665     747   747.1     748  863.17  872.35  881.53  890.71  899.89  909.07
  918.25  927.43   936.6  945.78  954.96  964.14  973.32   982.5  991.68 1000.86
 1010.04 1019.22 1028.39 1037.57 1046.75 1055.93 1065.11 1074.29 1083.47 1092.65
 1101.83 1111.01 1120.18 1129.36 1138.54 1147.72  1156.9 1166.08 1175.26 1184.44
  1194.2
  242.99  242.15  241.06  240.03  239.02  238.35  237.55  236.69  236.02  235.16
  234.07  233.29  232.69  231.89  231.22  230.84  230.29  229.53  228.94  228.38
  227.69  227.11  226.51  225.83  225.24  224.71  224.16  223.63  223.03   222.4
  221.95  221.45  220.98  220.49  220.19   219.8  219.44  219.15  218.82  218.44
  218.08  217.76  217.47  217.24  216.98  216.74  216.43  216.27  216.05  215.63
  215.45  215.23  214.92  214.68  214.46  214.05  213.87  213.66  213.48   213.3
  213.11  213.05  212.78  212.74  212.74   212.8  212.44  212.17   212.1   212.1
  213.34  213.34  213.34  211.34  211.94  214.94  217.66  219.86  220.54  223.04
  227.66  230.63  232.82  235.34  237.53  239.59  241.75  243.79  245.73  247.61
  249.68  251.78  253.96  256.24   258.6   260.8  263.13  264.74  266.06  267.58
   269.4   270.9  272.25  273.73  274.69  275.73  276.98  278.28  279.75  281.32
  282.56
                                                                                
                                                                                
                                                                                
                                                                                
                                                                                
                                                                                
                                                                                
   208.3   208.3
                                                                                
                                                                                
                                                                                
        
BR Coef=-1 , 0 , 0 ,, 0 ,,,0.8,0,,0,
WSPro=,,,, 1 ,,,, 0 ,,,, 0 ,,,,-1 ,-1 ,-1 , 0 , 0 , 0 , 0 , 0
BR U #Sta/Elev= 129
       0  242.78    9.48  241.91   18.96  241.63   28.44  240.98   37.93  239.26
   47.41  237.91   56.89  237.46   66.37  236.86   75.85  236.29   85.33  234.73
   94.81  232.79   104.3  230.97  113.78  229.58  123.26  228.81  132.74  228.88
  142.22  229.31   151.7   229.4  161.18   229.4  170.67  229.37  180.15  229.21
  189.63  229.25  199.11  228.84  208.59  225.71  218.07  222.45  227.55  223.64
  237.03   224.5  246.52  221.81     256  218.89  265.48  217.58  274.96  217.08
  284.44  216.87  293.92  216.65   303.4  216.42  312.89  216.15  322.37  216.06
  331.85  216.03  341.33  215.85  350.81  215.83  360.29  215.64  369.77  215.25
  379.26  214.91  388.74  214.33  398.22  213.93   407.7  214.02  417.18  214.03
  426.66  213.53  436.14  213.03  445.63  212.48  455.11   211.9  464.59  211.25
  474.07  211.04  483.55  210.75  493.03  210.56  502.51   210.9     512  210.76
  521.48   210.3  530.96   209.6  540.44  209.28  549.92  209.55   559.4  209.71
  568.88  210.25  578.36  210.64  587.85   210.6  597.33  210.48  606.81  210.14
  616.29  209.63  625.77  207.67  635.25  204.33  644.73  201.05  647.16  200.49
  654.22  196.86   663.7  196.32  673.18  196.22  682.66  196.26  692.14  199.09
  701.62  200.92  708.46  202.33   711.1  202.88  720.59  204.32  730.07  205.59
  739.55  206.35  749.03  206.43  758.51  206.54  767.99  206.71  777.47  206.74
  786.96  206.71  796.44  206.87  805.92   207.1   815.4  207.35  824.88  208.68
  834.36  211.95  843.84  214.42  853.32  215.27  862.81  216.36  872.29  218.67
  881.77  221.34  881.97 221.391  891.25  223.74  900.73  227.52  910.21  231.12
  919.69  233.66  929.18  235.81  938.66  238.25  948.14  240.24  957.62   242.5
   967.1  244.66  976.58  246.99  986.06  249.22  995.55  251.23 1005.03  252.98
 1014.51  255.06 1023.99  256.71 1033.47  258.53 1042.95  260.34 1052.43  262.34
 1061.92  264.48  1071.4   266.4 1080.88  268.15 1090.36  269.88 1099.84  271.31
 1109.32  273.22  1118.8  274.84 1128.29  276.87 1137.77  279.02 1147.25  280.78
 1156.73  282.61 1166.21  284.54 1175.69  286.14 1181.16  286.84
BR U #Mann= 4
       0     .06  635.25    .035  720.59     .06  881.97      .1
BR D #Sta/Elev= 134
       0  246.42    9.15  246.49   18.29  246.07   27.44  245.48   36.59  245.14
   45.73  244.41   54.88  243.69   64.02  243.42   73.17  242.35   82.32  240.98
   91.46  240.82  100.61  240.95  109.76  240.47   118.9  240.26  128.05  240.92
  133.86 241.079  137.19  241.17  146.34  241.19  155.49  240.97  164.63  240.36
  173.78   240.1  182.93  240.01  192.07  239.72  201.22  239.56  210.37  239.21
  219.51  238.86  228.66  238.51   237.8   238.3  246.95   237.9   256.1  237.08
  265.24  236.16  274.39  235.21  283.54  233.24  292.68  230.22  301.83  227.63
  310.97  225.49  320.12  223.39  329.27  221.33  338.41  218.59  347.56  215.98
  356.71  214.41  365.85  214.39     375  214.49  384.14  213.88  393.29  212.65
  402.44  210.75  411.58  209.95  420.73  210.04  429.88   210.5  439.02  211.93
  445.73 212.524  448.17  212.74  457.32  212.71  466.46  212.43  475.61  212.18
  484.75  211.67   493.9  209.64  503.05  207.26  512.19  205.31  521.34   204.4
  530.49  204.21  539.63  203.84  548.78  203.35  557.92  203.34  567.07  203.11
  576.22  202.72  585.36  202.42  594.51  202.41  603.66  202.69   612.8   203.1
  621.95  203.58   631.1  203.72  640.24  203.63  649.39  203.45  658.53  202.93
  667.68  200.99  674.68  199.65  676.83  199.24  685.97  196.92  695.12  196.78
  704.27  196.66  713.41  196.63  722.56  198.28   731.7  200.45  736.32  201.18
  740.85  201.89  745.44  202.76     750  203.49  759.14  206.34  768.29  207.88
  777.44  208.29  786.58  208.37  795.73  208.98  796.23 209.017  804.87  209.66
  814.02  210.89  823.17  213.98  832.31  217.36  841.46  219.04  850.61  219.25
  859.75   220.8   868.9  225.42  878.05  229.44  887.19  231.99  896.34   234.3
  905.48  236.48  914.63  238.69  923.78  240.84  932.92  243.02  942.07  245.05
  951.22  246.83  960.36   248.6  969.51  250.13  978.65  251.79   987.8  253.26
  996.95  254.82 1006.09  256.45 1015.24  257.98 1024.39  259.21 1033.53  260.07
 1042.68  261.02 1051.83  262.12 1060.97  262.92 1070.12  263.66 1077.06 263.804
 1079.26  263.85 1088.41  263.64 1097.56  264.83  1106.7  266.82 1115.85  268.29
    1125  269.67 1134.14  270.47 1143.29  270.72 1149.96  270.94
BR D #Mann= 7
       0     .06  133.86      .1  445.73     .06  658.53    .035     750     .06
  796.23      .1 1077.06     .06
BC Design=,, 0 ,, 0 ,,,,,,
BC Use User HTab Curves=0
BC User HTab FreeFlow(D)= 0

Type RM Length L Ch R = 1 ,58886.66,112.73,103.34,98.52
BEGIN DESCRIPTION:
Under water portion adjusted as per bridge inspection notes.
END DESCRIPTION:
XS GIS Cut Line= 2
1629168.10981798 739536.136592911628427.95753525738656.028242186
#Sta/Elev= 30
       0  246.42   64.02  243.42   82.32  240.98  133.86241.0789   256.1  237.08
  283.54  233.24  356.71  214.41  384.14  213.88  411.58  209.95  445.73 212.524
  484.75  211.67  521.34   204.4  585.36  202.42  658.53  202.93  685.97  196.92
  713.41  196.63  745.44  202.76     750  203.49  768.29  207.88  796.23209.0172
  814.02  210.89  832.31  217.36  859.75   220.8  878.05  229.44  942.07  245.05
 1015.24  257.98 1077.06263.8043 1088.41  263.64    1125  269.67 1149.96  270.94
#Mann= 7 ,-1 , 0
       0     .06       0  133.86      .1       0  445.73     .06       0
  658.53     .04       0     750     .06       0  796.23      .1       0
 1077.06     .06       0
#XS Ineff= 2 , 0
       0  605.01  205.53     804       0   208.3
Permanent Ineff=
       F       F
Bank Sta=658.53,745.44
XS Rating Curve= 0 ,0
Exp/Cntr=0.5,0.3

Type RM Length L Ch R = 1 ,58783.32,94.4,125.58,148.25
BEGIN DESCRIPTION:
left ineffective flow limit in place to restrict flow in a backwater area.
END DESCRIPTION:
XS GIS Cut Line= 2
1629267.69394329739431.1695419251628492.55264352738618.347762331
#Sta/Elev= 30
       0   269.8   29.02  267.79   106.4  265.73  135.01 263.382  193.46  257.13
  203.13  254.93   319.2  225.36  338.55  218.42  357.89  212.91  367.56  208.93
  386.91   204.3  396.58  203.89  406.26  205.61  415.93  205.84  541.67  201.93
  648.07  201.03  715.78   199.1  725.46  199.64  735.13  201.63  754.47  205.93
  773.82  207.61  793.17  211.05  812.51  211.26   851.2  220.93  860.87  226.15
  870.55  229.41  938.26  241.43 1015.64  250.65 1073.19253.8995 1123.17  255.03
#Mann= 5 ,-1 , 0
       0     .06       0  135.01      .1       0  541.67     .04       0
  735.13      .1       0 1073.19     .06       0
#XS Ineff= 2 , 0
          407.24  207.38
Permanent Ineff=
       F       F
Bank Sta=541.67,735.13
XS Rating Curve= 0 ,0
Exp/Cntr=0.3,0.1

Type RM Length L Ch R = 1 ,58657.73,27.81,29.51,31.68
BEGIN DESCRIPTION:
Upstream side of 1' concrete dam. Elevations of the dam and channel inverts are unknown.  This is an approximate study reach.
END DESCRIPTION:
XS GIS Cut Line= 4
1629325.53177817739360.9008176181628922.35472405738948.137145206
 1628883.3856446738802.2528990661628500.93378709738602.350723892
#Sta/Elev= 30
       0  277.76   39.14  273.78  107.64  264.42  166.16  253.69   195.7  249.43
  234.85   238.3  254.42  231.74  303.34  211.11  313.13  207.93  342.48  203.76
  371.84  202.09  410.98  201.92  450.12  199.54  489.26  200.46  518.62  198.41
   528.4  198.74  584.24  196.94  620.47  198.54  685.68  198.79  707.41  196.89
  721.91  199.26  743.79  203.18  775.39  203.31  806.98  205.14  870.17  215.46
  917.56  221.25  941.26  226.16  980.75  231.89 1096.69   246.4 1159.54  252.43
#Mann= 5 ,-1 , 0
       0     .06       0  166.16      .1       0   528.4     .04       0
  721.91      .1       0 1096.69     .06       0
Bank Sta=518.62,721.91
XS Rating Curve= 0 ,0
Exp/Cntr=0.3,0.1

Type RM Length L Ch R = 1 ,58628.23,235.5,223.85,153.47
BEGIN DESCRIPTION:
Downstream side of 1' concrete dam. Elevations of the dam and channel inverts are unknown.  This is an approximate study reach.
END DESCRIPTION:
XS GIS Cut Line= 4
1629339.54193825739340.886303291  1628947.257457738936.593113482
1628913.23278263738788.4857073131628504.93668993738580.334758118
#Sta/Elev= 30
       0  277.82  107.29  262.55  165.01  251.92  185.32  249.25  204.83  244.42
  263.35  225.06  302.36  209.27  312.11  206.89  360.88  201.32  409.65  201.43
  438.91  200.01  458.42  197.73  477.93  198.21  497.43  197.29  635.15  194.46
  671.06  195.39  685.43  197.87  692.61   199.5  699.79  199.92  723.15   196.6
  731.01  197.74  746.72  202.63  786.42   203.5  833.15     210  851.56   210.7
  880.29  215.19  951.01  222.57 1006.01  230.67  1068.2  238.13 1173.59  249.28
#Mann= 7 ,-1 , 0
       0     .06       0  165.01      .1       0  477.93     .04       0
  692.61      .1       0  786.42     .06       0  851.56      .1       0
  1068.2     .06       0
Bank Sta=497.43,685.43
XS Rating Curve= 0 ,0
Exp/Cntr=0.3,0.1