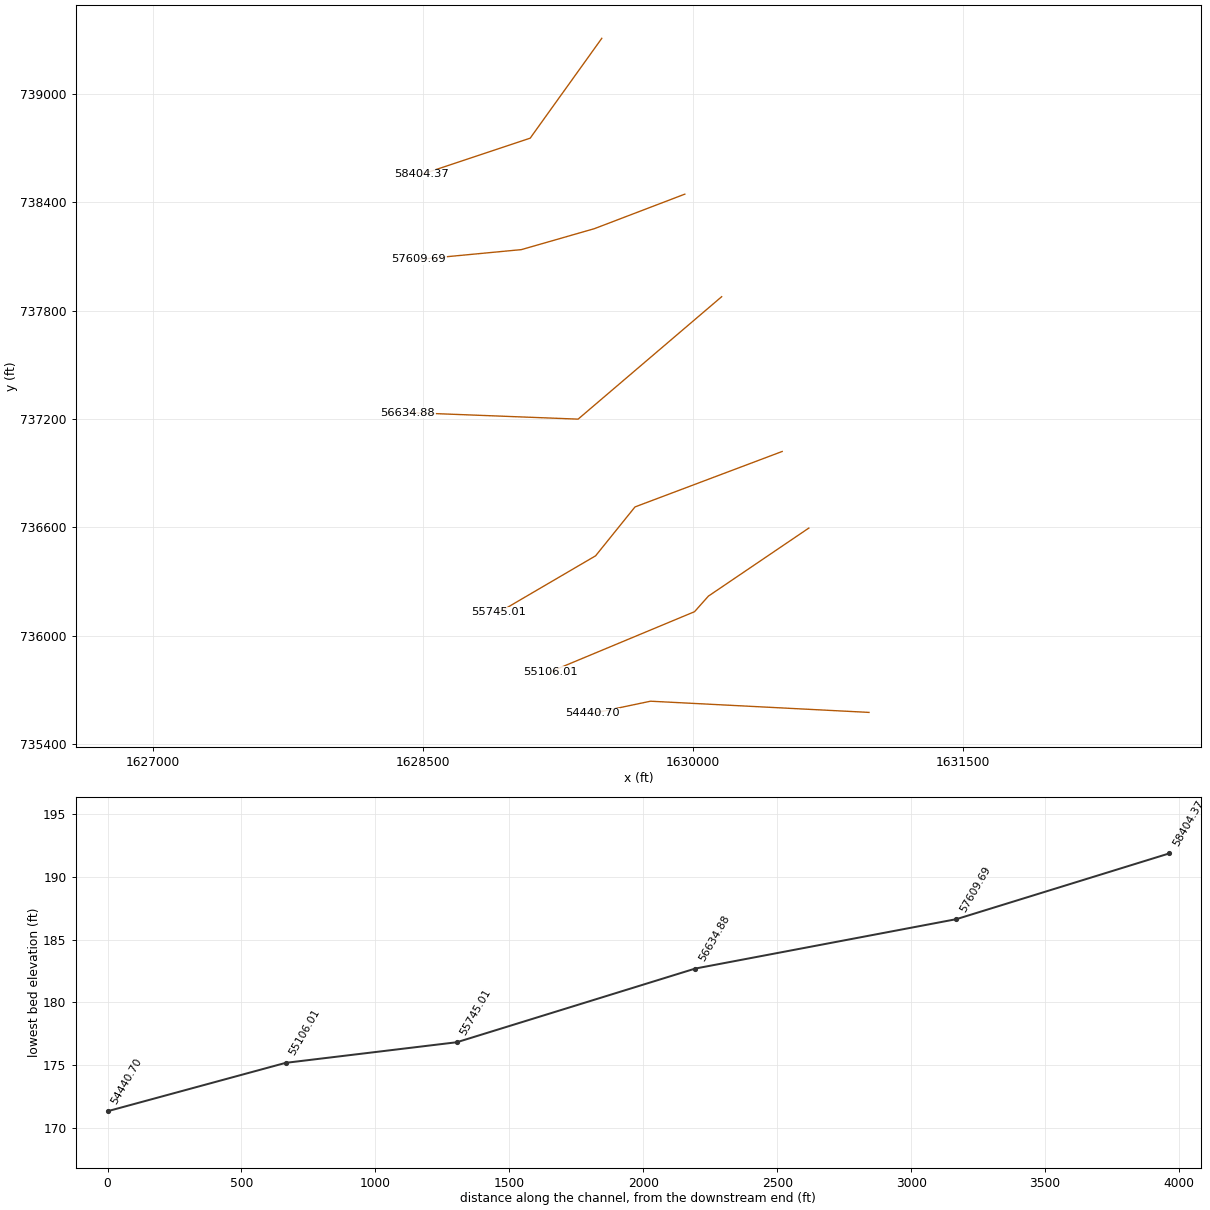
HEC-RAS study LittleElkCreek.prj: Little Elk Creek

--- LittleElkCreek.g01 (geometry) --- (continued)

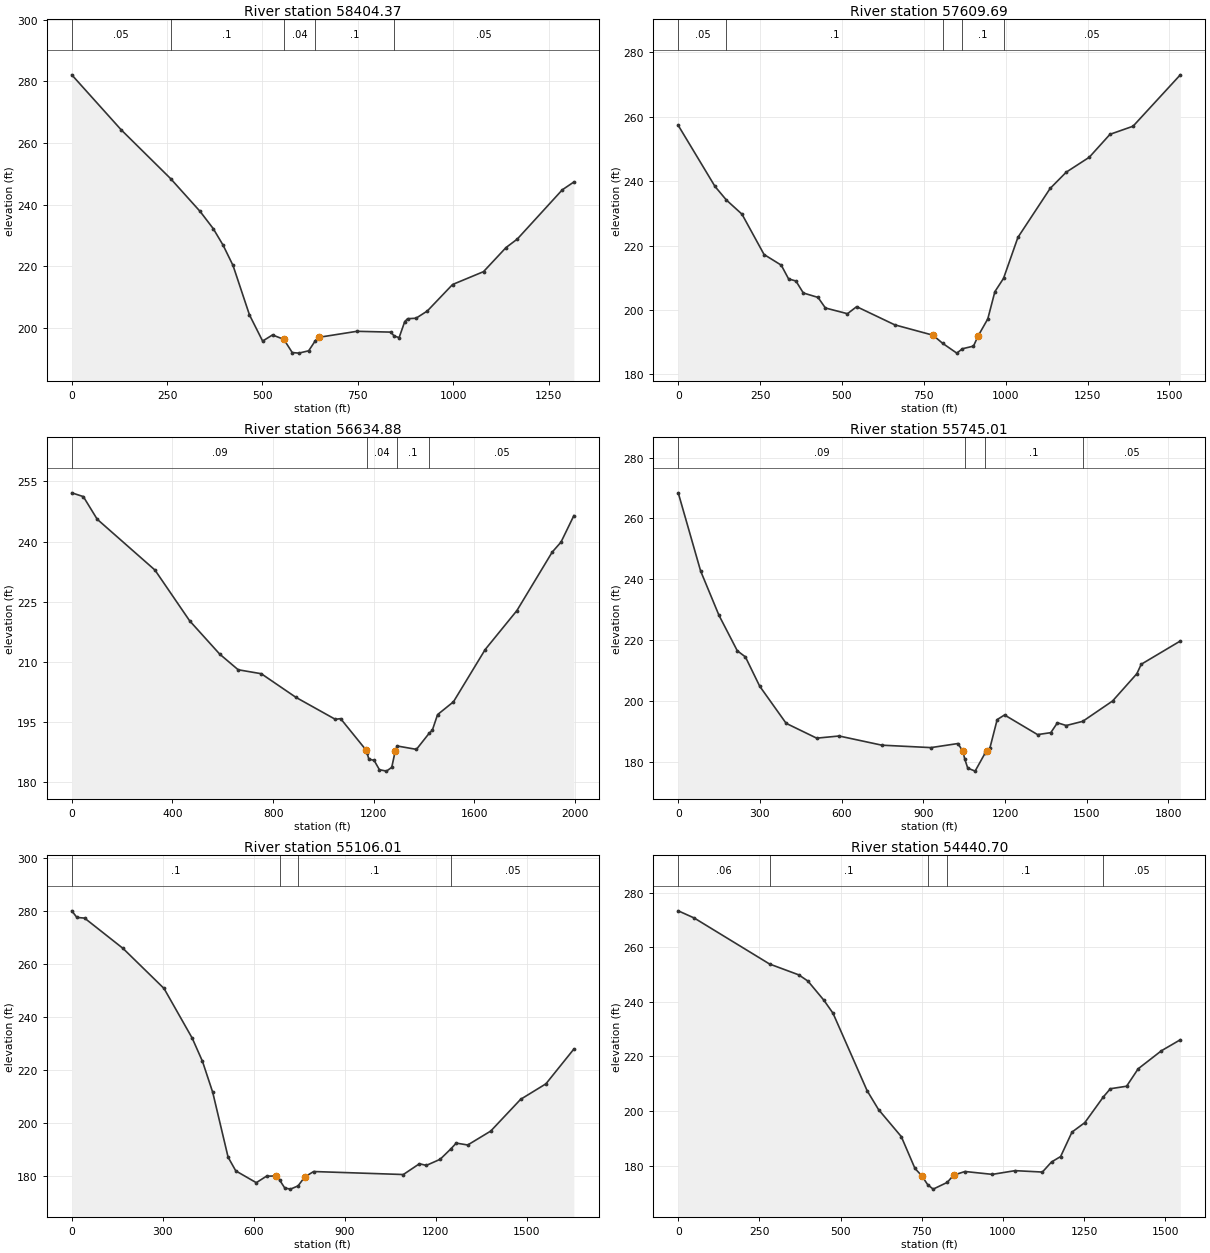
Type RM Length L Ch R = 1 ,58404.37,735.56,794.68,598.35
XS GIS Cut Line= 3
1629494.44968808739306.9417099061629096.30259869738754.212342694
1628493.56194212738554.173195079
#Sta/Elev= 30
       0  282.14   129.4  264.32  258.91 248.496  336.45  237.83  370.96  232.24
  396.84  226.85  422.72   220.3  465.86  204.27  500.37  195.77  526.25  197.76
  555.99  196.32  578.01  192.05  595.26  191.86  621.14  192.62   638.4  195.87
  647.02  196.97  747.58  198.94  836.08  198.68  845.44197.3987  858.21   196.9
  872.96   202.1  880.33  203.02  902.46  203.18  931.96  205.51  998.34  214.12
 1079.47  218.29 1138.47  226.11 1167.98  228.86 1285.98  244.84 1316.27  247.37
#Mann= 5 ,-1 , 0
       0     .05       0  258.91      .1       0  555.99     .04       0
   638.4      .1       0  845.44     .05       0
Bank Sta=555.99,647.02
XS Rating Curve= 0 ,0
Exp/Cntr=0.3,0.1

Type RM Length L Ch R = 1 ,57609.69,1006.61,974.81,950.98
XS GIS Cut Line= 4
1629955.99351211738444.3068406131629453.54272622738253.265276134
 1629047.4476326738137.2381065191628476.74029934738083.167196959
#Sta/Elev= 30
       0  257.35  112.33  238.38  147.18234.1555  194.71  229.77  262.11  217.25
  314.53  213.95     337  209.68  359.47  209.02  381.93  205.31  426.87  203.93
  449.33  200.65  516.74  198.87  544.82  201.06  661.31  195.41  777.79   192.2
  807.36  189.68  850.59  186.63  867.92  187.99  901.55  188.81  916.11  192.04
  945.23  197.25  966.92  205.72  993.33209.8452 1037.23  222.57 1135.67  237.77
 1184.89  242.83 1255.21  247.46 1318.49  254.58  1388.8  257.09 1533.15  273.05
#Mann= 5 ,-1 , 0
       0     .05       0  147.18      .1       0  807.36     .04       0
  867.92      .1       0  993.33     .05       0
Bank Sta=777.79,916.11
XS Rating Curve= 0 ,0
Exp/Cntr=0.3,0.1

Type RM Length L Ch R = 1 ,56634.88,707.42,889.87,904.16
XS GIS Cut Line= 3
1630161.00728361 737876.576396481629362.77602251737198.751194149
1628415.76184423737235.251265094
#Sta/Elev= 30
       0  252.16   45.92  251.22  101.02  245.57   330.6  232.88  468.35  220.22
  587.73  211.91   661.2     208  753.03  207.01  890.78  201.11  1047.2  195.63
 1068.21   195.8 1170.25  187.89 1173.29  187.27  1180.3  185.71 1201.31  185.38
 1222.33  183.06 1250.35   182.7 1271.36  183.64 1285.38  187.74 1292.38  188.98
 1369.44  188.13 1420.38192.1759 1432.49  192.89  1453.5  196.81 1516.55     200
 1642.64  213.05 1768.74  222.78 1908.84  237.36 1943.87  239.86 1994.92  246.46
#Mann= 4 ,-1 , 0
       0     .09       0 1173.29     .04       0 1292.38      .1       0
 1420.38     .05       0
Bank Sta=1170.25,1285.38
XS Rating Curve= 0 ,0
Exp/Cntr=0.3,0.1

Type RM Length L Ch R = 1 ,55745.01,664.67,639,581.12
XS GIS Cut Line= 4
1630497.44013944737019.7239668671629679.15111157736712.682301968
1629459.98868005736441.9522395731628923.03950958736129.195396915
#Sta/Elev= 30
       0  268.42   82.24  242.69  149.53  228.13  216.82  216.45  246.73  214.42
  299.06   204.8  396.26  192.57  508.41  187.69  590.65   188.4  747.66  185.38
  928.03  184.58  1027.1  185.92 1045.12  183.39 1052.39  180.75 1063.13  177.84
 1090.15  176.84 1126.17  182.65 1135.18   183.5 1144.18  184.33  1171.2   193.8
 1198.22  195.32 1319.53  188.86 1368.13   189.5 1392.44  192.75 1424.84  191.85
 1485.29  193.22 1594.96  199.92 1684.07  208.89 1700.27  212.01 1843.71  219.66
#Mann= 4 ,-1 , 0
       0     .09       0 1052.39     .04       0 1126.17      .1       0
 1485.29     .05       0
Bank Sta=1045.12,1135.18
XS Rating Curve= 0 ,0
Exp/Cntr=0.3,0.1

Type RM Length L Ch R = 1 ,55106.01,695.56,665.31,498.85
XS GIS Cut Line= 4
  1630645.649257736595.7199883911630087.25940044736218.920329109
1630010.08356664736132.6649854031629211.08669876735801.262875423
#Sta/Elev= 30
       0  280.04   16.89  277.55   42.22   277.3  168.89  265.88  304.01  250.79
   396.9  232.07  430.68  223.34  464.46  211.66  515.12  187.23  540.46  182.07
  608.01  177.63  641.79  180.09  673.63  180.15  685.57   178.5  701.81  175.63
  720.59   175.2  745.62  176.42  767.56  179.76  796.95  181.83  1092.5   180.7
 1145.55  184.76 1168.28  184.14 1213.75  186.43 1249.38190.3938  1266.8  192.54
 1304.69  191.83 1380.47  197.07 1478.99  209.03 1562.35  214.87 1654.37  227.96
#Mann= 4 ,-1 , 0
       0      .1       0  685.57     .04       0  745.62      .1       0
 1249.38     .05       0
Bank Sta=673.63,767.56
XS Rating Curve= 0 ,0
Exp/Cntr=0.3,0.1

Type RM Length L Ch R = 1 ,54440.70,620.23,602.07,503.21
XS GIS Cut Line= 3
1630980.20773473735575.1224255561629765.58468652735637.092989251
1629442.61420023735569.735373959
#Sta/Elev= 30
       0  273.34   49.06  270.72  281.39  253.84  371.48  249.86  399.52  247.58
  448.58  240.57  476.62  235.81  581.76   207.4   616.8  200.51  686.89   190.6
  728.95  178.94  749.97  176.25  768.27  172.97  785.02  171.35  828.26  173.81
   848.1  176.48  883.15  177.81  967.26  176.76 1037.35  178.12 1121.46  177.61
 1149.49   181.3 1177.53  183.29 1212.58  192.26 1251.96  195.71 1309.26205.1652
 1330.61  208.14 1380.67  209.06 1416.42  215.46 1487.93  222.06 1546.12  226.09
#Mann= 5 ,-1 , 0
       0     .06       0  281.39      .1       0  768.27     .04       0
  828.26      .1       0 1309.26     .05       0
Bank Sta=749.97,848.1
XS Rating Curve= 0 ,0
Exp/Cntr=0.3,0.1