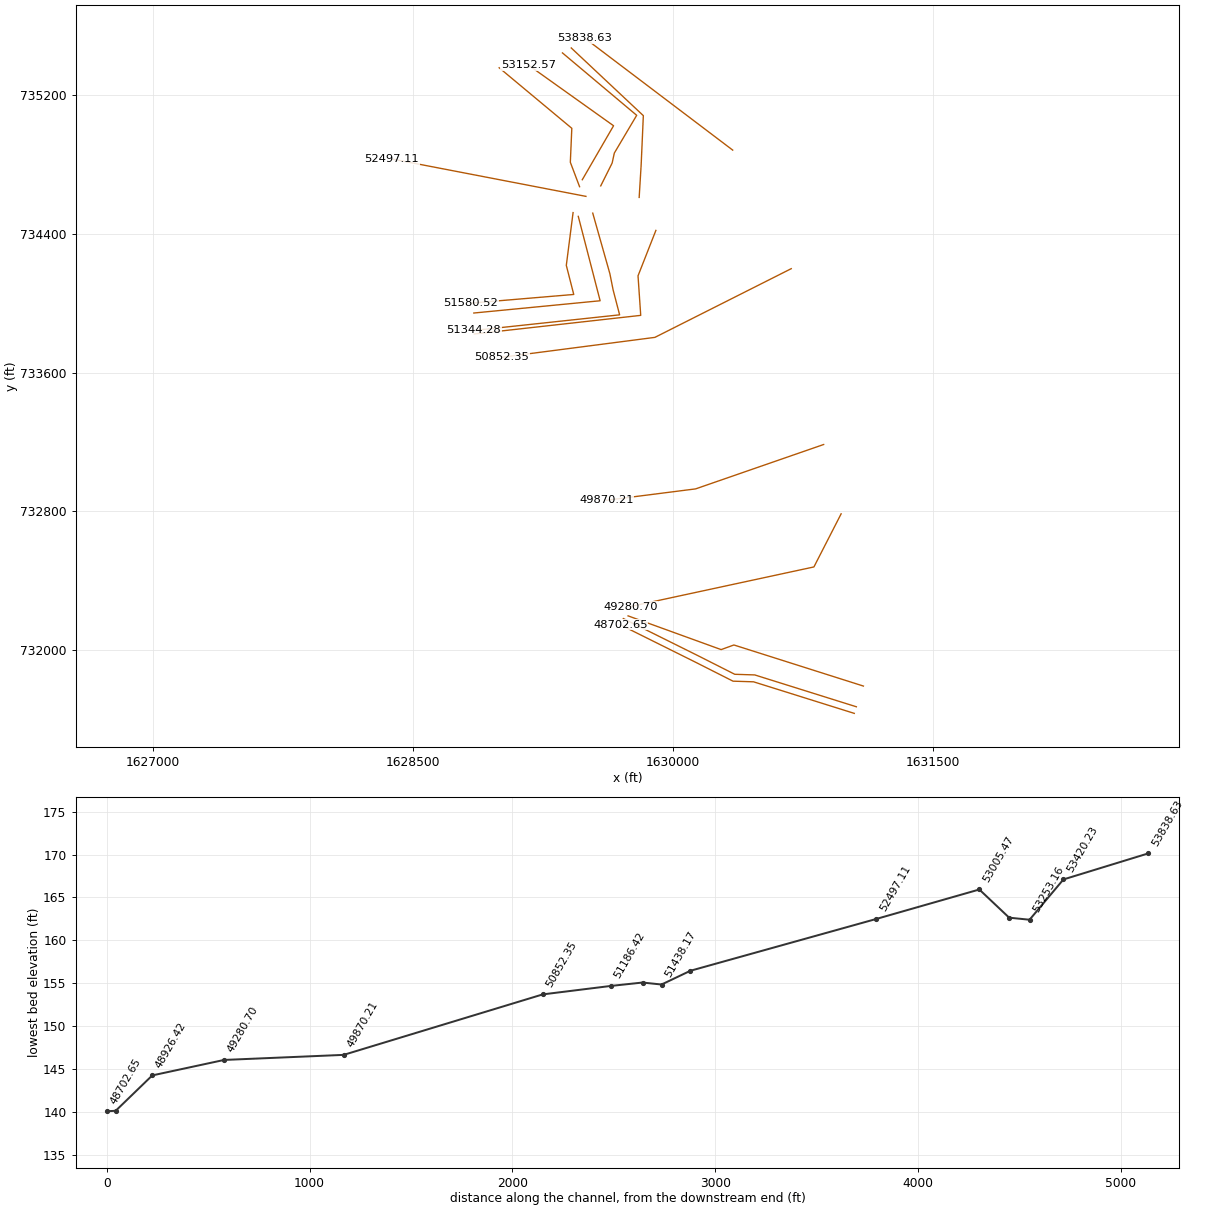
HEC-RAS study LittleElkCreek.prj: Little Elk Creek

--- LittleElkCreek.g01 (geometry) --- (continued)

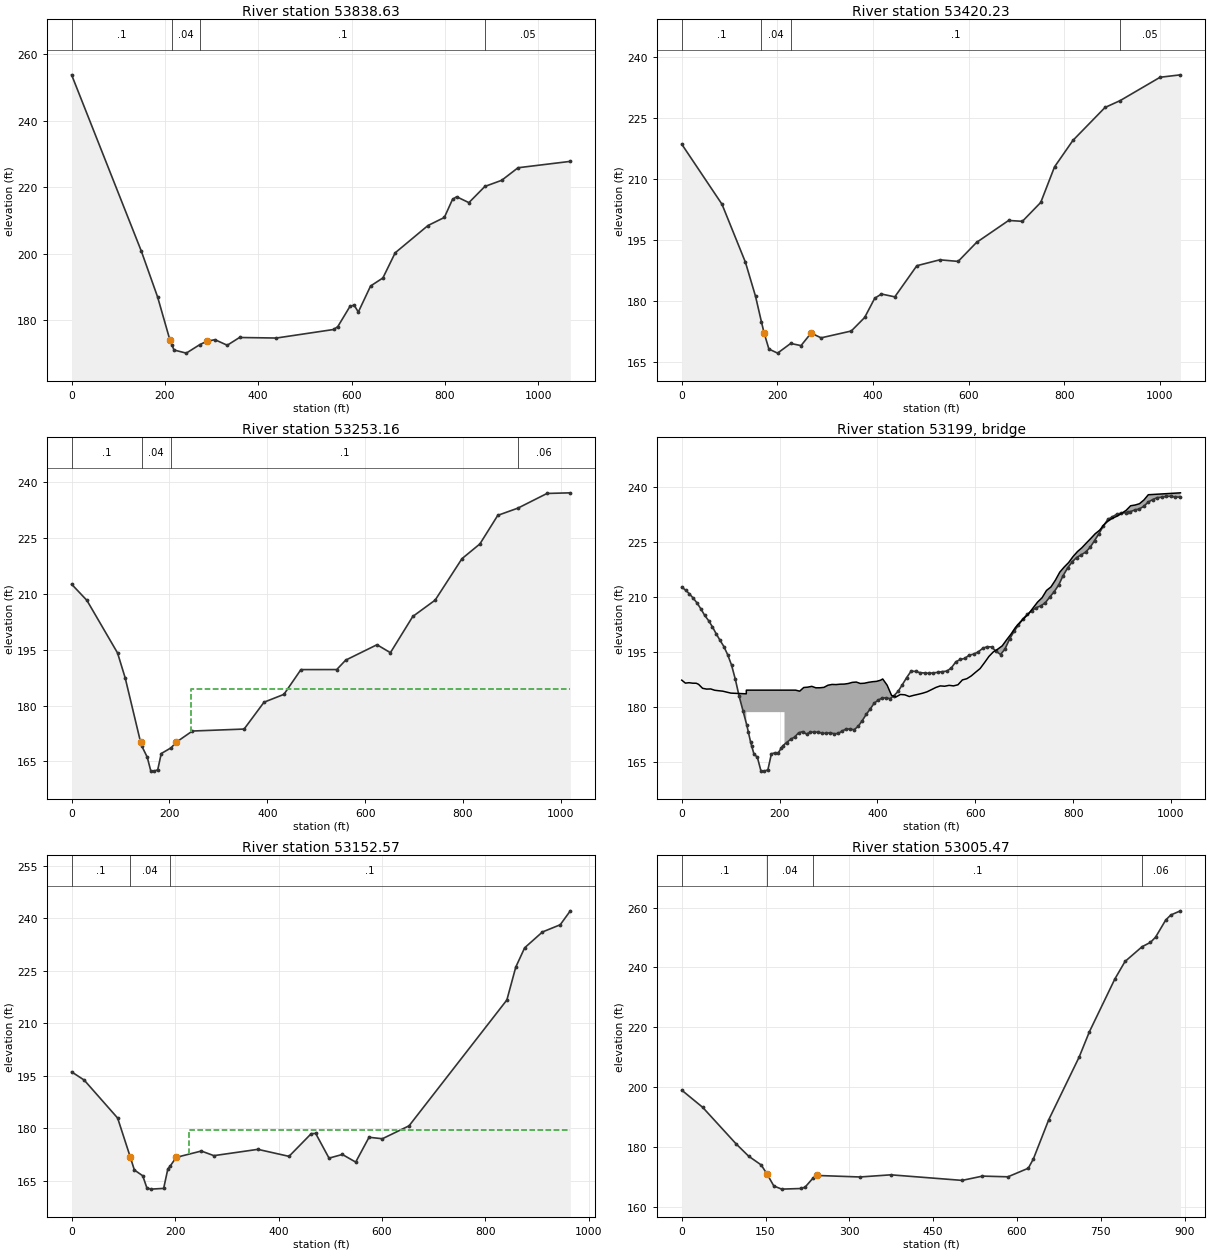
Type RM Length L Ch R = 1 ,53838.63,435.38,418.4,292.52
XS GIS Cut Line= 2
1630344.89049281734883.6649099891629492.55150451735528.877579555
#Sta/Elev= 30
       0  253.81  149.25  200.87  184.37     187  210.71  174.08  214.76  172.69
  219.49  171.07  245.82  170.13  274.73  172.68  289.72  173.69  307.28  174.17
  333.62   172.5  359.96  174.83  438.97  174.67  561.88  177.24  570.66  178.12
     597  184.26  605.78  184.52  614.56  182.48   640.9  190.32  667.24  192.73
  693.58  200.29  763.81  208.49  798.93  210.92  816.49  216.36  825.27  217.15
  851.61  215.38  885.89220.2544  921.84  222.09  956.96  225.87 1069.01  227.79
#Mann= 4 ,-1 , 0
       0      .1       0  214.76     .04       0  274.73      .1       0
  885.89     .05       0
Bank Sta=210.71,289.72
XS Rating Curve= 0 ,0
Exp/Cntr=0.3,0.1

Type RM Length L Ch R = 1 ,53420.23,168.92,167.06,158.04
BEGIN DESCRIPTION:
Section just upstream of a Chessie RR xing.  No information or pictures of the bridge, so it was not coded in this approximate study reach.
END DESCRIPTION:
XS GIS Cut Line= 4
1629804.97772053734610.6001455191629816.33431977734796.732006758
1629829.03963214735082.6015354391629412.94065152735473.289891317
#Sta/Elev= 30
       0  218.49   84.16  203.72  133.25  189.44  154.29   181.1  166.73  174.78
  172.04  172.16  182.34   168.1  200.49   167.1  227.88  169.48  249.54  168.95
  270.56  172.03  291.58  170.86  354.64  172.54  382.67  175.87  403.69  180.59
  417.71  181.64  445.73  180.94  491.83   188.6  539.84  190.05  578.25  189.66
  616.66  194.32  683.87  199.73  712.68  199.52  751.09  204.17  779.89  212.91
   818.3  219.41  885.51  227.52  917.15 229.208 1000.74  234.95  1043.4  235.55
#Mann= 4 ,-1 , 0
       0      .1       0  166.73     .04       0  227.88      .1       0
  917.15     .05       0
Bank Sta=172.04,270.56
XS Rating Curve= 0 ,0
Exp/Cntr=0.5,0.3

Type RM Length L Ch R = 1 ,53253.16,106.25,100.59,98.95
BEGIN DESCRIPTION:
Section just upstream of a Chessie RR xing.  Channel invert was lowered 3.5 feet as per bridge inspection report and RR bridge geometry.  No left ineffective flow limit because steep channel valley wall lies immediately along the channel.  Right ineffective flow limits set where flow would reasonably expand.
END DESCRIPTION:
XS GIS Cut Line= 5
1629583.09128788734677.1879548281629649.01843666734809.042252287
1629661.44015564734866.4627453831629790.62596579735084.523686767
1629362.11940193735444.702938467
#Sta/Elev= 30
       0  212.62    31.3  208.27   93.91  194.15  109.57  187.43  140.87  170.26
  142.92  169.28  154.58  166.17  161.74  162.53   168.9  162.41  176.07  162.78
  183.23  167.13  203.27  168.67   214.3  170.21  246.85  173.18  352.62  173.71
   393.3  180.92  433.98  183.03  468.77  189.68  541.92  189.69  560.21  192.22
  624.22  196.36  651.65  194.22  697.37  203.95   743.1  208.34  797.96  219.48
  834.54  223.43  871.12  231.11  912.26  233.05  971.71  236.99  1019.4  237.16
#Mann= 4 ,-1 , 0
       0      .1       0  142.92     .04       0  203.27      .1       0
  912.26     .06       0
#XS Ineff= 2 , 0
       0                   244.3       0   184.5
Permanent Ineff=
       F       F
Bank Sta=140.87,214.3
XS Rating Curve= 0 ,0
Exp/Cntr=0.5,0.3

Type RM Length L Ch R = 3 ,53199   ,,,
BEGIN DESCRIPTION:
Chessie RR Bridge - CE040108FS-2  Top of road elevation estimated from LIDAR bridge approaches. Geometry from general dimensions reported in bridge inspection, however the deck thickness reported as 10' does not seem reasonable.  From pictures it appears that the deck thickness could be between 6 and 8 ft thick.  A deck thickness of 6 feet was coded.  The underclearance dimension was measured to be approx 16'.
END DESCRIPTION:
Bridge Culvert--1,0,-1,-1, 0
Deck Dist Width WeirC Skew NumUp NumDn MinLoCord MaxHiCord MaxSubmerge Is_Ogee
53,10,2.6,0, 103, 102, , , 0.95, 0, 0,0,,
       0    7.42   14.84   22.26   29.69   34.33    42.6   50.87   59.13    67.4
   75.67   83.93    92.2  100.47   131.9     132     210   210.1  224.47  232.73
     241  249.27  257.53   265.8  274.07  282.33   290.6  298.87  307.13   315.4
  323.66  331.93   340.2  348.46  356.73     365  373.26  381.53   389.8  398.06
  406.33  410.76   419.8  428.85   437.9  446.95     456  465.05  474.09  483.14
  492.19  501.24  510.29  519.34  528.38  537.43  546.48  555.53  564.58  573.62
  582.67  591.72  600.77  609.82  618.87  627.91  636.96  646.01  655.06  664.11
  673.16   682.2  691.25   700.3  709.35   718.4  727.45  736.49  745.54  754.59
  763.64  772.69  781.74  790.78  799.83  808.88  817.93  826.98  836.02  845.07
  854.12  863.17  872.22  881.27  890.31  899.36  908.41  917.46  926.51  935.56
   944.6  953.65  1019.4
  187.23  186.42  186.53   186.4  186.38  186.09     185  184.79  184.83  184.47
  184.34  184.22  183.95  183.69   183.5   184.5   184.5   184.5   184.5   184.5
  184.22  185.22  185.32  185.54  185.14  185.15  185.26  185.85  186.06  186.02
  186.13  186.15  186.31  186.62  186.71  186.32  186.39  186.63   186.8   186.9
  187.21  187.55  185.85  183.07  182.65  183.32  183.23  182.76  183.09  183.36
  183.66  184.04  184.63  185.23  185.66  185.57  185.81  185.66  185.97  187.29
  187.62  188.38   189.4  190.39  192.01  193.71  194.95   195.7  196.59  198.25
  199.82  201.63     203  204.17   205.4  206.99  208.55  209.71   211.7  212.65
  214.49  216.69  218.09  219.31  220.95  222.31  223.36  224.64  225.88  227.17
  228.13  229.65  230.74  231.46  231.99  232.76  233.56   234.8     235  235.36
  236.37  237.81  238.33
                                                                                
                                           178.5   178.5
                                                                                
                                                                                
                                                                                
                                                                                
                                                                                
                                                                                
                                                                                
                                                                                
                        
     -13   -5.58    1.84    9.26   16.69   21.33    29.6   37.87   46.13    54.4
   62.67   70.93    79.2   87.47   95.73   111.9     112     190   190.1     228
  236.27  244.53   252.8  261.07  269.33   277.6  285.87  294.13   302.4  310.66
  318.93   327.2  335.46  343.73     352  360.26  368.53   376.8  385.06  393.33
  397.76   406.8  415.85   424.9  433.95     443  452.05  461.09  470.14  479.19
  488.24  497.29  506.34  515.38  524.43  533.48  542.53  551.58  560.62  569.67
  578.72  587.77  596.82  605.87  614.91  623.96  633.01  642.06  651.11  660.16
   669.2  678.25   687.3  696.35   705.4  714.45  723.49  732.54  741.59  750.64
  759.69  768.74  777.78  786.83  795.88  804.93  813.98  823.02  832.07  841.12
  850.17  859.22  868.27  877.31  886.36  895.41  904.46  913.51  922.56   931.6
  940.65  952.39
  187.23  186.42  186.53   186.4  186.38  186.09     185  184.79  184.83  184.47
  184.34  184.22  183.95  183.69  182.08   183.5   184.5   184.5   184.5  184.22
  185.22  185.32  185.54  185.14  185.15  185.26  185.85  186.06  186.02  186.13
  186.15  186.31  186.62  186.71  186.32  186.39  186.63   186.8   186.9  187.21
  187.55  185.85  183.07  182.65  183.32  183.23  182.76  183.09  183.36  183.66
  184.04  184.63  185.23  185.66  185.57  185.81  185.66  185.97  187.29  187.62
  188.38   189.4  190.39  192.01  193.71  194.95   195.7  196.59  198.25  199.82
  201.63     203  204.17   205.4  206.99  208.55  209.71   211.7  212.65  214.49
  216.69  218.09  219.31  220.95  222.31  223.36  224.64  225.88  227.17  228.13
  229.65  230.74  231.46  231.99  232.76  233.56   234.8     235  235.36  236.37
  237.81  238.33
                                                                                
                                                   178.5   178.5
                                                                                
                                                                                
                                                                                
                                                                                
                                                                                
                                                                                
                                                                                
                                                                                
                
BR Coef=-1 , 0 , 0 ,, 0 ,,,0.8,-1,,0,
WSPro=,,,, 1 ,,,, 0 ,,,, 0 ,,,,-1 ,-1 ,-1 , 0 , 0 , 0 , 0 , 0
BR U #Sta/Elev= 124
       0  212.62    7.83  211.78   15.65  210.78   23.48  209.59    31.3  208.27
   39.13  206.65   46.96  204.89   54.78  203.48   62.61  201.79   70.44  199.86
   78.26  198.09   86.09   196.4   93.91  194.15  101.74  191.35  109.57  187.43
  117.39  182.79  125.22  178.84  133.05   174.9  136.22  173.01  140.87  170.26
  142.92  169.28  147.42  167.14  154.58  166.17  161.74  162.53   168.9  162.41
  176.07  162.78  183.23  167.13  190.39   167.4  197.55  167.45  203.27  168.67
  206.17  169.28   214.3  170.21  222.44  171.06  230.57   171.7  238.71  172.83
  246.85  173.18  254.98  172.52  263.12  173.04  271.26  173.03  279.39  173.04
  287.53   172.7  295.66  172.74   303.8  172.88  311.94  172.58  320.07  172.69
  328.21  173.37  336.35  173.93  344.48  173.84  352.62  173.71  360.75  174.66
  368.89  176.16  377.03  177.87  385.16  179.35   393.3  180.92  401.44  181.77
  409.57  182.35  417.71  182.41  425.84  182.16  433.98  183.03  442.12  184.15
  450.25  185.85  459.62   187.9  468.77  189.68  477.91  189.61  487.05  189.27
   496.2  189.19  505.34   189.1  514.49  189.21  523.63  189.36  532.78  189.56
  541.92  189.69  551.07  190.58  560.21  192.22  569.35  192.88   578.5  193.16
  587.64  194.05  596.79  194.34  605.93  194.92  615.08   195.9  624.22  196.36
  633.36  196.28  642.51  195.09  651.65  194.22   660.8  195.75  669.94  198.41
  679.09  200.51  688.23  202.24  697.37  203.95  706.52  205.18  715.66  206.18
  724.81     207  733.95  207.49   743.1  208.34  752.24  209.89  761.39  211.37
  770.53  213.21  779.67  215.77  788.82  217.85  797.96  219.48  807.11  220.68
  816.25  221.39   825.4  222.14  834.54  223.43  843.68  225.26  852.83  227.22
  861.97  229.32  871.12  231.11  880.26  231.77  889.41  232.52  898.55  232.78
  907.69  232.92  912.26  233.05  916.84  233.18  925.98  233.65  935.13  233.91
  944.27  234.62  953.42   235.8  962.56  236.48  971.71  236.99  980.85  237.13
  989.99  237.35  999.14   237.4 1008.28  237.17  1019.4  237.16
BR U #Mann= 4
       0      .1  142.92    .035  203.27      .1  912.26     .06
BR D #Sta/Elev= 118
       0  196.14    8.09  195.23   16.18  194.56   24.27   193.8   32.36   192.4
   40.45     191   48.54   189.2   56.63  187.68   64.72  186.24    72.8   185.3
   80.89   184.4   88.98  182.95   97.07  180.14  105.16  176.48  113.25   171.9
  121.34  168.11  124.18  167.72  129.43  167.01  137.52  166.46  145.61  162.96
   153.7  162.65  161.79   162.9  169.88  162.84  177.97  162.86  186.06  168.43
  190.51  169.22  194.15  169.87  202.24  171.72  210.32  172.44  218.41  172.49
   226.5  172.39  234.59  172.55  242.68  173.14  250.77  173.53  258.86  173.14
  266.95  172.28  275.04  172.21  283.13  172.33  291.22  172.89  299.31  173.15
   307.4  173.57  315.49  173.52  323.58  173.07  331.67  172.76  339.76  173.01
  347.85  173.38  355.93  173.94  360.12  174.01  368.72  173.81  377.31  173.59
  385.91  173.57   394.5  173.55   403.1  173.09  411.69   171.8  420.29  172.01
  428.88  172.72  437.48  173.37  446.07  174.86  454.67  177.18  463.26  178.49
  471.86  178.55  480.46  176.88  489.05  173.83  497.65   171.5  506.24  171.02
  514.84  171.65  523.43  172.55  532.03  172.24  540.62  170.13  549.22  170.37
  557.81  172.51  566.41   175.4     575  177.46   583.6  177.81  592.19  177.38
  600.79  177.04  609.38     178  617.98  178.69  626.58  179.03  635.17  178.75
  643.77  179.52  652.36  180.73  660.96  182.23  669.55  184.17  678.15  186.46
  686.74  188.11  695.34  189.28  703.93  190.78  712.53  192.93  721.12  194.49
  729.72     196  738.31  197.78  746.91  199.65   755.5  201.11   764.1  202.46
  772.69  203.47  781.29   205.1  789.89  207.02  798.48  208.37  807.08  210.01
  815.67  212.08  824.27  214.38  832.86  215.98  841.46  216.67  850.05  220.41
  858.65  226.05  867.24  229.12  875.84  231.57  884.43  233.13  893.03  234.14
  901.62  235.04  910.22  236.09  918.81   236.8  927.41  237.28  936.01  237.62
   944.6  238.15   953.2  239.73  964.13  242.13
BR D #Mann= 3
       0      .1  113.25    .035  190.51      .1
BC Design=,, 0 ,, 0 ,,,,,,
BC Use User HTab Curves=0
BC User HTab FreeFlow(D)= 0

Type RM Length L Ch R = 1 ,53152.57,136.03,147.1,318.06
BEGIN DESCRIPTION:
Section just downstream of a Chessie RR xing. Channel Invert  was lowered 3.5 feet as per bridge inspection report and bridge geometry.  No left ineffective flow limit because steep channel valley wall lies immediately along the channel.
END DESCRIPTION:
XS GIS Cut Line= 3
1629476.59606995734712.6917425841629657.09114873735024.314574733
1629165.18705994735374.823720321
#Sta/Elev= 30
       0  196.14   24.27   193.8   88.98  182.95  113.25   171.9  121.34  168.11
  137.52  166.46  145.61  162.96   153.7  162.65  177.97  162.86  186.06  168.43
  190.51  169.22  202.24  171.72  250.77  173.53  275.04  172.21  360.12  174.01
  420.29  172.01  463.26  178.49  471.86  178.55  497.65   171.5  523.43  172.55
  549.22  170.37     575  177.46  600.79  177.04  652.36  180.73  841.46  216.67
  858.65  226.05  875.84  231.57  910.22  236.09   944.6  238.15  964.13  242.13
#Mann= 3 ,-1 , 0
       0      .1       0  113.25     .04       0  190.51      .1       0
#XS Ineff= 1 ,-1
  227.42  964.13 179.468
Permanent Ineff=
       F
Bank Sta=113.25,202.24
XS Rating Curve= 0 ,0
Exp/Cntr=0.5,0.3

Type RM Length L Ch R = 1 ,53005.47,341.93,508.36,571.45
XS GIS Cut Line= 4
1629460.91536669734672.5313691941629407.58570184734813.596934259
1629416.11697957735009.5459892151628996.84167083735358.942079857
#Sta/Elev= 30
       0     199   37.42  193.27   97.29  181.05  119.74  176.94  142.19  174.01
  152.65  170.98  164.82  166.98  178.84  165.93  213.87  166.14  220.88  166.62
  234.89   169.6   241.9   170.5  318.97  169.99  374.28  170.71  501.85  168.85
   538.3  170.28  583.86  170.05   620.3  172.91  629.41  176.02  656.75  189.06
  711.42   210.1  729.65  218.51  775.21  236.14  793.43     242  823.98246.9345
  838.99  248.39   848.1  250.12  866.33  255.87  875.44  257.54  892.72  258.93
#Mann= 4 ,-1 , 0
       0      .1       0  152.65     .04       0  234.89      .1       0
  823.98     .06       0
Bank Sta=152.65,241.9
XS Rating Curve= 0 ,0
Exp/Cntr=0.3,0.1

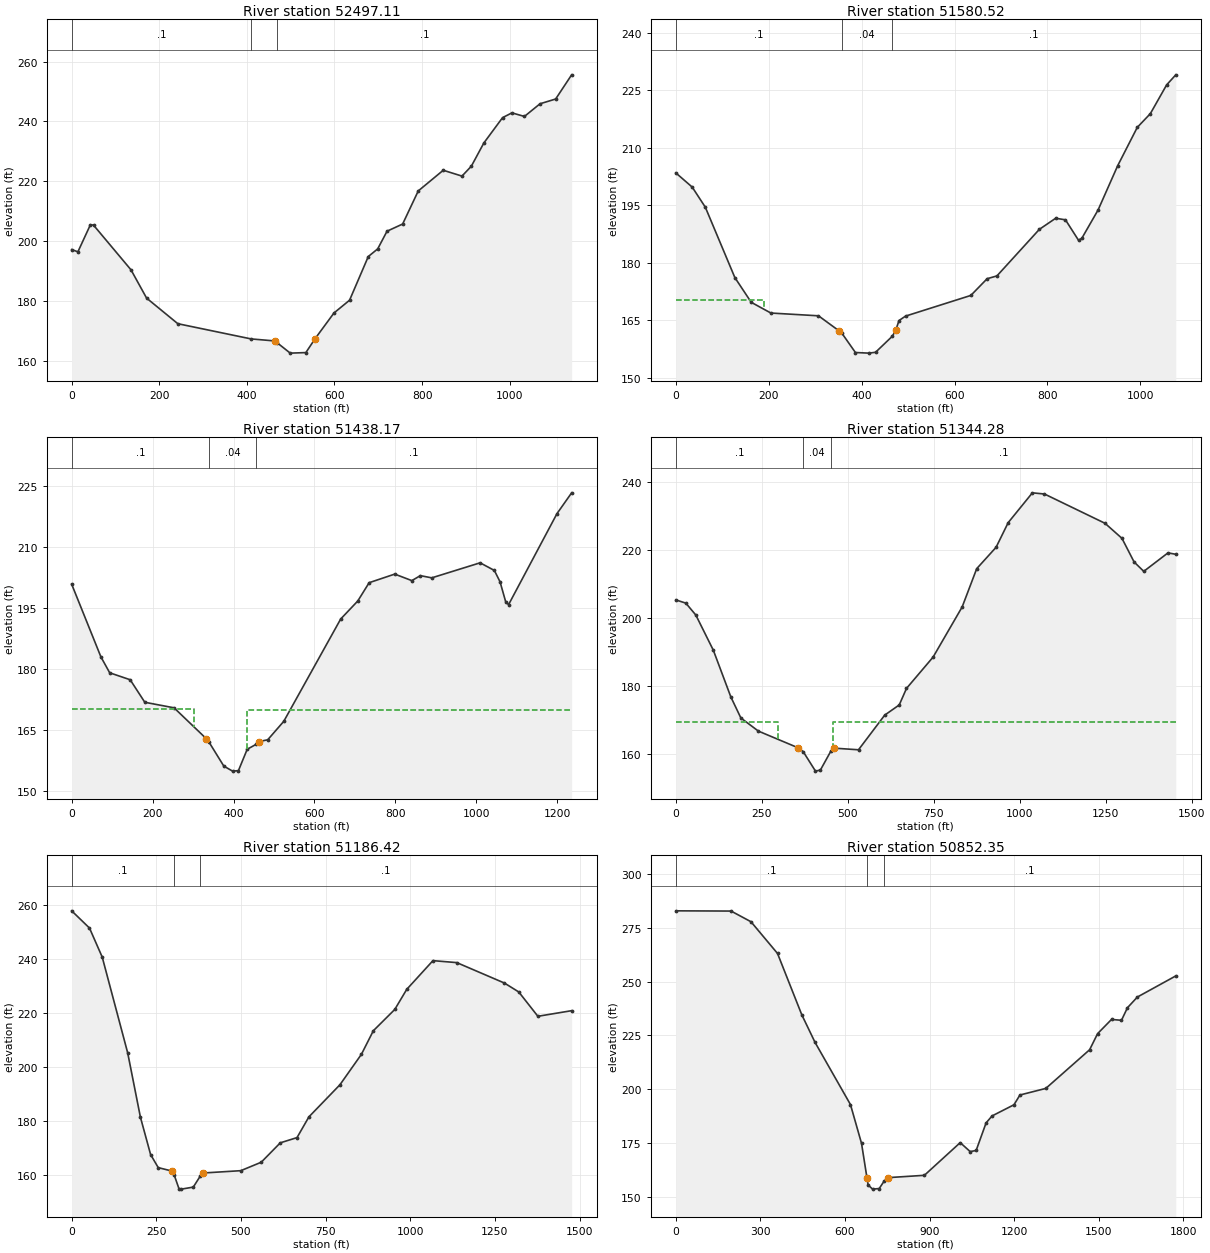
Type RM Length L Ch R = 1 ,52497.11,684.76,916.59,978.98
XS GIS Cut Line= 2
1629497.60448028734616.7231509091628376.76836729734832.689133644
#Sta/Elev= 30
       0  197.14   14.26  196.39   42.77  205.44    49.9  205.31  135.45  190.36
  171.09   180.9  242.38  172.34  409.78  167.25  463.37  166.58  469.71   165.9
  499.01   162.5  534.66  162.68  556.04  167.39  598.82  175.92  634.46   180.2
  677.23  194.81  698.62  197.35  720.01  203.28  755.65  205.68  791.29  216.75
  848.32  223.66   891.1  221.71  912.48  225.02     941  232.78  983.77  241.26
 1005.16  242.86 1033.67  241.66 1069.32   245.9 1104.96  247.49 1141.45  255.58
#Mann= 3 ,-1 , 0
       0      .1       0  409.78     .04       0  469.71      .1       0
Bank Sta=463.37,556.04
XS Rating Curve= 0 ,0
Exp/Cntr=0.3,0.1

Type RM Length L Ch R = 1 ,51580.52,150.69,142.35,142.32
XS GIS Cut Line= 4
1629423.40278636 734522.99469547 1629384.3492633734218.377215281
 1629427.3081387734050.4470659791628833.70044765734000.413624972
#Sta/Elev= 30
       0  203.46   35.29  199.75   63.52  194.51  127.03  176.18  162.32  169.72
  204.66  166.92  307.11   166.2  350.46  162.36  357.69  161.62  386.59  156.63
  415.49  156.47  429.94  156.69  466.07  160.88  473.29  162.41  480.45  164.97
   494.5  166.12  634.99  171.51  670.12  175.87  691.19   176.6  782.52  188.74
  817.64  191.63  838.72  191.22  866.81  185.89  873.84  186.39  908.96   193.8
  951.11  205.33  993.26  215.32 1021.36  218.89 1056.48   226.4 1076.16  229.02
#Mann= 3 ,-1 , 0
       0      .1       0  357.69     .04       0  466.07      .1       0
#XS Ineff= 1 ,-1
       0   188.8170.2869
Permanent Ineff=
       F
Bank Sta=350.46,473.29
XS Rating Curve= 0 ,0
Exp/Cntr=0.5,0.3

Type RM Length L Ch R = 1 ,51438.17,96.8,93.9,94.16
BEGIN DESCRIPTION:
Section just upstream of an old Chessie RR xing.   MDE contractors visited the site.  No structure was in sight.   Thus, a bridge was not coded at this location.
END DESCRIPTION:
XS GIS Cut Line= 3
1629453.47604513734501.1925046151629579.61687876734014.127289474
1628850.50036725733943.293898255
#Sta/Elev= 30
       0  200.78   72.31  182.92      94  179.02  144.62  177.31  180.77  171.78
  253.08  170.42  332.62  162.85  339.85  161.93  376.01  156.11   397.7  154.87
  412.16  154.99  433.86  160.24  455.55  161.43  462.78  162.13  484.47  162.56
  524.23   167.1  664.89  192.23  707.09  196.65  735.22  201.15  798.52  203.26
  840.72  201.66  861.81  202.88  889.95  202.34 1009.51  206.03 1044.67  204.16
 1058.74  201.37  1072.8  196.43 1079.84  195.76  1199.4   218.1 1235.68  223.22
#Mann= 3 ,-1 , 0
       0      .1       0  339.85     .04       0  455.55      .1       0
#XS Ineff= 2 ,-1
       0  302.84170.1675  434.21 1235.68169.7803
Permanent Ineff=
       F       F
Bank Sta=332.62,462.78
XS Rating Curve= 0 ,0
Exp/Cntr=0.5,0.3

Type RM Length L Ch R = 1 ,51344.28,167.77,157.85,206.07
BEGIN DESCRIPTION:
Section just downstream of a Chessie RR xing.  MDE contractors visited the site.  No structure was in sight.   Thus, a bridge was not coded at this location.
END DESCRIPTION:
XS GIS Cut Line= 5
1629536.96006222734519.9602293821629635.85395202734170.341381893
1629654.59964313734076.6129264381629692.09102528733932.895961434
1628850.50036725733842.494380549
#Sta/Elev= 30
       0   205.4    29.1  204.45    58.2  200.95  109.12  190.61  160.04  176.89
  189.14  170.72  240.06  166.86  356.46  161.92  370.48  160.82  406.17   155.1
  420.45  155.42  451.28  161.05  458.92  161.86  531.26  161.37  607.45  171.55
  649.69  174.54  670.81   179.4  748.25  188.61  832.74  203.34  874.98  214.57
   931.3  220.85   966.5  228.09  1036.9  236.85 1072.11   236.5 1248.11   227.9
  1297.4  223.48  1332.6  216.55 1360.76  213.78 1431.16  219.21 1453.88   218.8
#Mann= 3 ,-1 , 0
       0      .1       0  370.48     .04       0  451.28      .1       0
#XS Ineff= 2 ,-1
       0   297.5 169.528  456.48 1453.88169.5973
Permanent Ineff=
       F       F
Bank Sta=356.46,458.92
XS Rating Curve= 0 ,0
Exp/Cntr=0.5,0.3

Type RM Length L Ch R = 1 ,51186.42,394.38,334.07,196.14
XS GIS Cut Line= 4
1629901.41790915734420.2839297061629798.31660815734157.844254479
1629813.93801735 733929.771679611628853.86035116733822.334476992
#Sta/Elev= 30
       0  257.88   52.65  251.49   90.25  240.73  165.46  205.22  203.06  181.37
  233.14  167.52  255.71  162.67     296  161.41  303.01  159.87  317.05  154.82
  324.06   154.7  359.15  155.45   379.5  159.47  387.21  160.67  499.47  161.54
  559.88  164.67  616.23  171.87  665.53   173.8  700.75   181.5  792.32  193.39
  855.71  204.67  890.93  213.41  954.32  221.32  989.54  228.75 1067.02  239.41
 1137.46  238.68 1278.34  231.09  1320.6  227.79 1376.95  218.78 1476.64  220.86
#Mann= 3 ,-1 , 0
       0      .1       0  303.01     .04       0   379.5      .1       0
Bank Sta=296,387.21
XS Rating Curve= 0 ,0
Exp/Cntr=0.3,0.1

Type RM Length L Ch R = 1 ,50852.35,964.1,982.14,936.32
XS GIS Cut Line= 3
1630682.74902907734199.3759116981629895.72287022733802.764304116
1629011.77959561733687.935120031
#Sta/Elev= 30
       0  282.84  195.97  282.73  266.51  277.78  360.58  263.07   446.8  234.56
  493.83  221.76  619.25  192.95  658.44  174.97  678.05  158.71  681.96  155.63
  697.64  153.72  721.15  153.99   738.5  157.41  752.51  159.05  881.31  160.13
 1008.37  175.29 1043.67  171.13 1064.84  171.66 1100.14  184.46 1121.31  187.68
 1198.96  192.86 1220.14  197.39  1311.9  200.45  1467.2  218.39 1495.43  225.85
 1544.84  232.45 1580.14  232.05 1601.31  237.88 1636.61  242.85 1772.69  252.64
#Mann= 3 ,-1 , 0
       0      .1       0  678.05     .04       0   738.5      .1       0
Bank Sta=678.05,752.51
XS Rating Curve= 0 ,0
Exp/Cntr=0.3,0.1

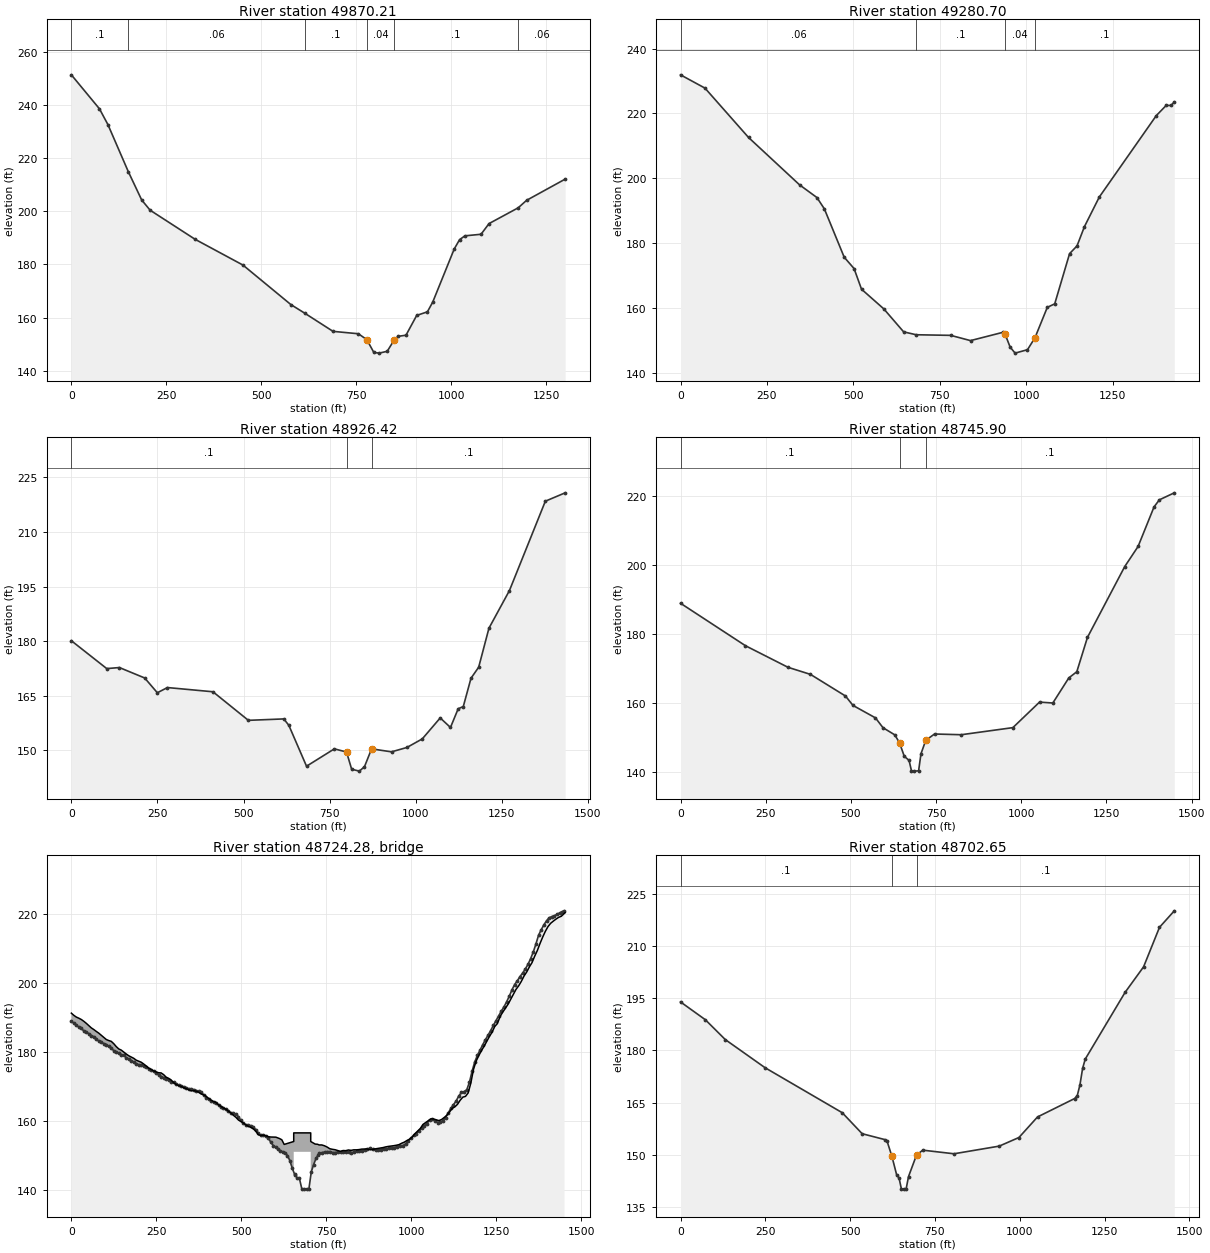
Type RM Length L Ch R = 1 ,49870.21,593.61,589.51,593.28
XS GIS Cut Line= 3
1630869.85070559733184.3575294171630130.65424229732928.158755228
1629616.88008255732862.655728325
#Sta/Elev= 30
       0  251.25   74.09  238.46   96.31  232.54  149.79214.9191  185.21  204.22
  207.44  200.38  325.97  189.44  451.92  179.76  577.86  164.94  614.77 161.664
  688.99  154.86  755.67  153.96  777.89  151.77  796.45  146.94  810.56  146.68
  831.73  147.37  849.46  151.48  859.96  152.98  881.13  153.41  909.35  160.85
  937.58   162.2  951.69   165.9 1008.15  185.81 1022.26  189.32 1036.37  190.75
 1078.71  191.34 1099.88  195.36 1176.61201.2812 1198.68  204.09 1300.27  212.06
#Mann= 6 ,-1 , 0
       0      .1       0  149.79     .06       0  614.77      .1       0
  777.89     .04       0  849.46      .1       0 1176.61     .06       0
Bank Sta=777.89,849.46
XS Rating Curve= 0 ,0
Exp/Cntr=0.3,0.1

Type RM Length L Ch R = 1 ,49280.70,377.41,354.27,314.81
XS GIS Cut Line= 3
1630970.65022331732784.0994444941630813.63899212732477.690611482
 1629754.7165838732249.283297703
#Sta/Elev= 30
       0   231.9   70.79   227.8  196.64  212.59  344.29  197.97  394.42  194.06
   415.9  190.57  473.19  175.68  501.84  172.15  523.32   165.8  587.77  159.73
  645.06  152.65  681.38151.7556  781.12  151.57   838.4  149.95   931.5  152.49
  938.66  151.85  952.98  147.95   967.3  146.09 1003.11  147.15 1024.59  150.79
 1060.39   160.2 1081.88  161.29 1124.84  176.77 1146.33  179.15 1167.81   185.1
 1210.78  194.23 1375.48  219.32 1404.12  222.47 1418.45  222.45 1427.57  223.55
#Mann= 4 ,-1 , 0
       0     .06       0  681.38      .1       0  938.66     .04       0
 1024.59      .1       0
Bank Sta=938.66,1024.59
XS Rating Curve= 0 ,0
Exp/Cntr=0.3,0.1

Type RM Length L Ch R = 1 ,48926.42,153.27,180.52,115.1
XS GIS Cut Line= 4
   1631099.33463  731790.06030641630351.80567099732027.196593821
1630277.99503846732000.4991309941629740.90490401732195.233565688
#Sta/Elev= 30
       0  180.13  102.81  172.47  139.53  172.76  212.97  169.89  249.69  165.83
  279.06  167.26  411.25   166.1  514.06  158.25  616.88  158.64  631.56  156.88
  682.97  145.64  763.75  150.41  799.13  149.54  814.02  144.81  836.35  144.29
  851.23   145.5  871.89  150.41  929.74  149.59  974.42  150.79  1019.1  153.15
 1071.22  158.91    1101  156.29 1123.34  161.43 1138.23  162.05 1160.57  169.82
 1182.91  172.86 1212.69  183.57 1272.26  193.93  1376.5  218.48 1434.04  220.78
#Mann= 3 ,-1 , 0
       0      .1       0  799.13     .04       0  871.89      .1       0
Bank Sta=799.13,871.89
XS Rating Curve= 0 ,0
Exp/Cntr=0.5,0.3

Type RM Length L Ch R = 1 ,48745.90,41.87,43.25,56.25
BEGIN DESCRIPTION:
Channel invert lowered 3' as per bridge inspection report
END DESCRIPTION:
XS GIS Cut Line= 5
1631058.53535025731670.5661966651630471.98828959731854.350942329
1630356.90003319 731857.947450341630144.74730223731965.218369499
1629713.55077425732179.599938989
#Sta/Elev= 30
       0  188.92  190.72  176.58  315.43  170.32  381.45  168.26  484.15  161.98
  506.15  159.25  572.17  155.63  594.18  152.78  628.67  150.71  642.68  148.42
  656.69  144.47  670.69   143.3   677.7   140.3   684.7  140.17  698.71  140.25
  705.71  145.21  719.72  149.11   745.5  150.95  823.94  150.74  975.36   152.8
 1053.53  160.21 1092.62  159.95 1139.52  167.24 1162.98  169.03 1194.24  179.01
 1303.69  199.58 1342.78   205.4 1389.68   216.9 1405.31  218.95 1449.09  220.98
#Mann= 3 , 0 , 0
       0      .1       0  642.68     .04       0  719.72      .1       0
Bank Sta=642.68,719.72
XS Rating Curve= 0 ,0
Exp/Cntr=0.5,0.3

Type RM Length L Ch R = 3 ,48724.28,,,
BEGIN DESCRIPTION:
Black Snake Rd- CE050407PF-4.  Top of road from Lidar.  Bridge geometry taken from Bridge Inspection Report
END DESCRIPTION:
Bridge Culvert--1,0,-1,-1, 0
Deck Dist Width WeirC Skew NumUp NumDn MinLoCord MaxHiCord MaxSubmerge Is_Ogee
15,14,2.6,0, 185, 185, , , 0.95, 0, 0,0,,
       0    7.34   14.67   22.01   29.34   36.68   44.01   51.35   58.68   66.02
   73.36   80.69   88.03   95.36   102.7  110.03  117.37   124.7  132.04  139.38
  146.71  154.05  161.38  168.72  176.05  183.39  190.72  198.06   205.4  212.73
  220.07   227.4  234.74  242.07  249.41  256.75  264.08  271.42  278.75  286.09
  293.42  300.76  308.09  315.43  322.77   330.1  337.44  344.77  352.11  359.44
  366.78  374.11  381.45  388.79  396.12  403.46  410.79  418.13  425.46   432.8
  440.13  447.47  454.81  462.14  469.48  476.81  484.15  491.48  498.82  506.15
  513.49  520.83  528.16   535.5  542.83  550.17   557.5  564.84  572.17  579.51
  586.85  594.18  601.52  611.92  618.93  625.93     654 654.001 703.999     704
  716.98  723.98  728.77  736.59  744.42  752.25  760.07   767.9  775.73  783.55
  791.38   799.2  807.03  814.86  822.68  830.51  838.34  846.16  853.99  861.81
  869.64  877.47  885.29  893.12  900.94  908.77   916.6  924.42  932.25  940.08
   947.9  955.73  963.55  971.38  979.21  987.03  994.86 1002.69 1010.51 1018.34
 1026.16 1033.99 1041.82 1049.64 1057.47  1065.3 1073.12 1080.95 1088.78  1096.6
 1104.43 1112.25 1120.08 1127.91 1135.73 1143.56 1151.39 1159.21 1167.04 1174.86
 1182.69 1190.52 1198.34 1206.17    1214 1221.82 1229.65 1237.47  1245.3 1253.13
 1260.95 1268.78 1276.61 1284.43 1292.26 1300.08 1307.91 1315.74 1323.56 1331.39
 1339.22 1347.04 1354.87  1362.7 1370.52 1378.35 1386.17    1394 1401.83 1409.65
 1417.48 1425.31 1433.13 1440.96 1452.35
  191.27  190.63  190.13   189.8  189.42   188.9  188.31  187.63  186.99  186.51
  185.96  185.46  184.85   184.2  183.62  183.31  183.08   182.4  181.56  180.88
  180.54  179.97  179.41   178.9  178.54  178.16  177.62  177.31  177.02  176.51
  175.92  175.33  174.88  174.49   174.2  173.96  173.91  173.41  172.69  172.34
  171.87  171.07  170.57  170.23  170.03  169.64  169.39  169.05  168.72  168.79
  168.63  168.34  167.82  167.54  167.16  166.54  165.98  165.59  165.31  164.67
  164.15   163.7  163.38  162.79  162.27   161.6     161  160.23   159.8  159.36
  158.81  158.39  158.12  157.64  156.96  155.95  155.76  155.83  155.64  155.39
   155.3  155.29  155.26  154.87  154.51  153.15     154   156.5   156.5     154
  153.26   153.2     153     153  152.76  152.39   151.9  151.73  151.61  151.39
  151.14  151.38  151.34  151.54  151.43  151.58  151.58  151.65  151.79   151.8
  151.84  151.65  151.65  151.85  151.98  152.11  152.23  152.43  152.57  152.67
  152.78  152.91  153.09  153.49  153.81  154.29  154.69  155.25  156.27     157
  157.76  158.94   159.5  160.08  160.58  160.54  160.32  160.07  160.38  160.97
  161.62  162.55  163.64  164.05   164.8  165.98  166.88   167.1   168.1  170.94
  174.92  177.35  178.95  180.38  181.67   183.1  184.51  185.75   187.4  188.26
   190.3  191.55  192.71  193.86  195.32  196.71  198.19  199.23  200.52  202.05
  203.22  204.69  205.94   207.8  209.45  211.48  213.34  215.01   216.4  217.36
  217.99  218.57  219.09   219.4  220.45
                                                                                
                                                                                
                                                                                
                                                                                
                                                                                
                                                                                
                                                                                
                                                                                
                                                     151     151     151     151
                                                                                
                                                                                
                                                                                
                                                                                
                                                                                
                                                                                
                                                                                
                                                                                
                                                                                
                                        
     -25  -17.66  -10.33   -2.99    4.34   11.68   19.01   26.35   33.68   41.02
   48.36   55.69   63.03   70.36    77.7   85.03   92.37    99.7  107.04  114.38
  121.71  129.05  136.38  143.72  151.05  158.39  165.72  173.06   180.4  187.73
  195.07   202.4  209.74  217.07  224.41  231.75  239.08  246.42  253.75  261.09
  268.42  275.76  283.09  290.43  297.77   305.1  312.44  319.77  327.11  334.44
  341.78  349.11  356.45  363.79  371.12  378.46  385.79  393.13  400.46   407.8
  415.13  422.47  429.81  437.14  444.48  451.81  459.15  466.48  473.82  481.15
  488.49  495.83  503.16   510.5  517.83  525.17   532.5  539.84  547.17  554.51
  561.85  569.18  576.52  586.92  593.93  600.93     629 629.001 678.999     679
  691.98  698.98  703.77  711.59  719.42  727.25  735.07   742.9  750.73  758.55
  766.38   774.2  782.03  789.86  797.68  805.51  813.34  821.16  828.99  836.81
  844.64  852.47  860.29  868.12  875.94  883.77   891.6  899.42  907.25  915.08
   922.9  930.73  938.55  946.38  954.21  962.03  969.86  977.69  985.51  993.34
 1001.16 1008.99 1016.82 1024.64 1032.47  1040.3 1048.12 1055.95 1063.78  1071.6
 1079.43 1087.25 1095.08 1102.91 1110.73 1118.56 1126.39 1134.21 1142.04 1149.86
 1157.69 1165.52 1173.34 1181.17    1189 1196.82 1204.65 1212.47  1220.3 1228.13
 1235.95 1243.78 1251.61 1259.43 1267.26 1275.08 1282.91 1290.74 1298.56 1306.39
 1314.22 1322.04 1329.87  1337.7 1345.52 1353.35 1361.17    1369 1376.83 1384.65
 1392.48 1400.31 1408.13 1415.96 1455.61
  191.27  190.63  190.13   189.8  189.42   188.9  188.31  187.63  186.99  186.51
  185.96  185.46  184.85   184.2  183.62  183.31  183.08   182.4  181.56  180.88
  180.54  179.97  179.41   178.9  178.54  178.16  177.62  177.31  177.02  176.51
  175.92  175.33  174.88  174.49   174.2  173.96  173.91  173.41  172.69  172.34
  171.87  171.07  170.57  170.23  170.03  169.64  169.39  169.05  168.72  168.79
  168.63  168.34  167.82  167.54  167.16  166.54  165.98  165.59  165.31  164.67
  164.15   163.7  163.38  162.79  162.27   161.6     161  160.23   159.8  159.36
  158.81  158.39  158.12  157.64  156.96  155.95  155.76  155.83  155.64  155.39
   155.3  155.29  155.26  154.87  154.51  153.15     154   156.5   156.5     154
  153.26   153.2     153     153  152.76  152.39   151.9  151.73  151.61  151.39
  151.14  151.38  151.34  151.54  151.43  151.58  151.58  151.65  151.79   151.8
  151.84  151.65  151.65  151.85  151.98  152.11  152.23  152.43  152.57  152.67
  152.78  152.91  153.09  153.49  153.81  154.29  154.69  155.25  156.27     157
  157.76  158.94   159.5  160.08  160.58  160.54  160.32  160.07  160.38  160.97
  161.62  162.55  163.64  164.05   164.8  165.98  166.88   167.1   168.1  170.94
  174.92  177.35  178.95  180.38  181.67   183.1  184.51  185.75   187.4  188.26
   190.3  191.55  192.71  193.86  195.32  196.71  198.19  199.23  200.52  202.05
  203.22  204.69  205.94   207.8  209.45  211.48  213.34  215.01   216.4  217.36
  217.99  218.57  219.09   219.4  220.45
                                                                                
                                                                                
                                                                                
                                                                                
                                                                                
                                                                                
                                                                                
                                                                                
                                                     151     151     151     151
                                                                                
                                                                                
                                                                                
                                                                                
                                                                                
                                                                                
                                                                                
                                                                                
                                                                                
                                        
BR Coef=-1 , 0 , 0 ,, 0 ,,,0.8,0,,0,
WSPro=,,,, 1 ,,,, 0 ,,,, 0 ,,,,-1 ,-1 ,-1 , 0 , 0 , 0 , 0 , 0
BR U #Sta/Elev= 195
       0  188.92    7.34  188.32   14.67  187.85   22.01  187.16   29.34  186.82
   36.68   186.1   44.01  185.72   51.35   185.3   58.68  184.77   66.02  184.41
   73.36   183.8   80.69  183.09   88.03  182.79   95.36  182.43   102.7  182.15
  110.03  181.59  117.37  181.08   124.7  180.37  132.04  179.91  139.38  179.62
  146.71  179.11  154.05  179.06  161.38  178.36  168.72  177.95  176.05  177.46
  183.39     177  190.72  176.58  198.06  176.29   205.4  176.21  212.73  175.93
  220.07  175.53   227.4  175.11  234.74  174.84  242.07  174.36  249.41  173.81
  256.75  173.34  264.08  172.75  271.42  172.56  278.75  172.29  286.09  171.75
  293.42  171.37  300.76  171.31  308.09  170.76  315.43  170.32  322.77  170.19
   330.1  169.88  337.44   169.6  344.77  169.33  352.11  169.22  359.44  169.08
  366.78  168.78  374.11  168.55  381.45  168.26  388.79  167.63  396.12  166.73
  403.46  166.31  410.79  165.88  418.13  165.51  425.46  165.14   432.8   164.6
  440.13  164.16  447.47  163.76  454.81  163.33  462.14  162.93  469.48  162.22
  476.81  162.22  484.15  161.98  491.48  161.18  498.82   160.1  506.15  159.25
  513.49  158.82  520.83  158.71  528.16  158.59   535.5  158.09  542.83  157.45
  550.17  156.38   557.5  155.77  564.84  155.95  572.17  155.63  579.51  154.96
  586.85  153.73  594.18  152.78  601.52  152.33  608.85   151.7  614.67  151.19
  621.67  151.03  628.67  150.71  635.68  149.92  642.68  148.42  649.68  146.24
  656.69  144.47  658.32  144.24  663.69  143.48  670.69   143.3   677.7   140.3
   684.7  140.17   691.7  140.27  698.71  140.25  705.71  145.21  712.71  147.32
  719.72  149.11  726.72  150.15  729.81  150.62  737.65  150.76   745.5  150.95
  753.34  151.03  761.19  151.07  769.03  150.74  776.87  150.79  784.72     151
  792.56  150.93  800.41  150.84  808.25  150.95  816.09  151.04  823.94  150.74
  831.78  150.88  839.63  151.18  847.47  151.23  855.31  151.38  863.16  151.59
     871  151.86  878.84     152  886.69  151.81  894.53  151.44  902.38  151.46
  910.22  151.67  918.06  151.91  925.91  151.79  933.75  151.98   941.6  151.97
  949.44  152.09  957.28  152.53  967.54  152.69  975.36   152.8  983.18  153.28
  990.99  154.15  998.81  155.04 1006.63  155.76 1014.44  156.32 1022.26  157.16
 1030.08  157.98  1037.9  158.57 1045.71  159.21 1053.53  160.21 1061.35  160.41
 1069.17  160.03 1076.98   159.5  1084.8  159.52 1092.62  159.95 1100.44  160.93
 1108.25  162.29 1116.07   163.6 1123.89  164.68 1131.71  165.76 1139.52  167.24
 1147.34  168.23 1155.16  168.49 1162.98  169.03 1170.79   171.2 1178.61  174.42
 1186.43  177.11 1194.24  179.01 1202.06  180.58 1209.88  182.08  1217.7  183.56
 1225.51  184.84 1233.33  186.23 1241.15  187.69 1248.97  189.06 1256.78  190.49
  1264.6  191.86 1272.42   193.1 1280.24  194.57 1288.05   196.2 1295.87  198.03
 1303.69  199.58 1311.51  200.63 1319.32  201.88 1327.14  202.87 1334.96  204.05
 1342.78   205.4 1350.59  207.04 1358.41  208.99 1366.23   211.3 1374.04  213.87
 1381.86  215.48 1389.68   216.9  1397.5  218.09 1405.31  218.95 1413.13  219.31
 1420.95  219.55 1428.77  219.99 1436.58  220.36  1444.4  220.72 1449.09  220.98
BR U #Mann= 3
       0      .1  642.68    .035  719.72      .1
BR D #Sta/Elev= 196
       0  193.98    7.34  193.63   14.67   193.1   22.01   192.6   29.34  191.98
   36.68  191.49   44.01  190.94   51.35   190.3   58.68  189.82   66.02  189.43
   73.36  188.84   80.69  188.06   88.03  187.29   95.36  186.56   102.7  185.94
  110.03  185.36  117.37   184.7   124.7  183.87  132.04  183.14  139.38  182.72
  146.71  182.37  154.05  181.73  161.38  181.14  168.72  180.64  176.05  180.31
  183.39  179.79  190.72   179.2  198.06  178.89   205.4  178.56  212.73  178.13
  220.07  177.48   227.4  176.79  234.74  176.14  242.07  175.59  249.41  175.04
  256.75  174.95  264.08  174.78  271.42  174.38  278.75  173.82  286.09  173.18
  293.42  172.59  300.76  172.12  308.09   171.6  315.43  171.15  322.77  170.79
   330.1  170.35  337.44  170.12  344.77   169.9  352.11  169.51  359.44  168.94
  366.78  168.49  374.11  168.29  381.45  168.05  388.79  167.64  396.12  167.01
  403.46  166.36  410.79  165.75  418.13  165.33  425.46  165.02   432.8  164.64
  440.13  164.34  447.47  163.96  454.81  163.43  462.14   162.9  469.48  162.53
  476.81   162.1  484.15  161.58  491.48  160.88  498.82  160.16  506.15  159.37
  513.49  158.37  520.83  157.57  528.16   156.8   535.5  156.06  542.83  155.87
  550.17  155.89   557.5  156.02  564.84  155.84  572.17  155.83  579.51  155.53
  586.85  155.03  594.18   154.7  601.52  154.39  609.18  153.83  616.19  152.21
  623.19  149.55  630.19  146.55   631.3  146.18   637.2  144.21   644.2  143.32
   651.2  140.15  658.21  140.12  665.21  140.23  672.21  143.75  679.22  145.38
  686.22  147.47  693.22  149.52  695.78  149.94  700.23  150.68  707.23  151.08
  714.23  151.33  721.24  151.29  727.73  151.15  735.57   151.3  743.41  151.47
  751.26  151.06   759.1  150.78  766.95  150.54  774.79  150.18  782.63   150.3
  790.48  150.36  798.32  150.29  806.17  150.29  814.01  150.79  821.85  151.29
   829.7  151.27  837.54   151.1  845.38  151.04  853.23     151  861.07  151.09
  868.92  151.15  876.76  151.19   884.6  151.34  892.45  151.59  900.29  151.54
  908.14  151.72  915.98  151.96  923.82  152.08  931.67  152.25  939.51  152.49
  947.36  152.82   955.2  153.31  963.04  153.61   974.2   153.8  982.02  154.21
  989.84   154.6  997.65  154.97 1005.47  155.67 1013.29  156.22 1021.11  157.04
 1028.92  158.41 1036.74  159.41 1044.56  160.21 1052.37  160.88 1060.19  161.27
 1068.01  161.49 1075.83  161.91 1083.64  162.09 1091.46  162.33 1099.28  162.53
  1107.1  162.98 1114.91  163.36 1122.73  163.61 1130.55  164.28 1138.37  165.05
 1146.18  165.27    1154  165.73 1161.82  166.18 1169.64  167.05 1177.45   170.1
 1185.27  174.83 1193.09  177.53 1200.91  178.38 1208.72  179.42 1216.54   180.6
 1224.36  181.92 1232.17  183.48 1239.99  184.94 1247.81  186.35 1255.63  187.47
 1263.44  188.87 1271.26  190.12 1279.08  191.55  1286.9  192.68 1294.71  194.15
 1302.53  195.44 1310.35   196.7 1318.17  197.79 1325.98  198.67  1333.8  199.77
 1341.62  200.98 1349.44  201.95 1357.25  202.85 1365.07  204.07 1372.89  205.73
  1380.7  207.82 1388.52   209.8 1396.34   211.5 1404.16  213.75 1411.97  215.44
 1419.79  216.19 1427.61  216.89 1435.43  217.72 1443.24  218.22 1451.06  219.29
 1455.61  220.18
BR D #Mann= 3
       0      .1  623.19    .035  695.78      .1
BC Design=,, 0 ,, 0 ,,,,,,
BC Use User HTab Curves=0
BC User HTab FreeFlow(D)= 0

Type RM Length L Ch R = 1 ,48702.65,91.14,99.05,101.57
BEGIN DESCRIPTION:
Channel invert lowered 3' as per bridge inspection report
END DESCRIPTION:
XS GIS Cut Line= 5
1631046.57537548731632.3960643111630465.25955239731814.541688889
1630346.77523205731818.2443238941630126.81869599 731929.46108596
1629695.74312803732143.782516703
#Sta/Elev= 30
       0  193.98   73.36  188.84  132.04  183.14  249.41  175.04  476.81   162.1
   535.5  156.06  601.52  154.39  609.18  153.83  623.19  149.55   637.2  144.21
   644.2  143.32   651.2  140.15  658.21  140.12  665.21  140.23  672.21  143.75
  695.78  149.94  714.23  151.33  806.17  150.29  939.51  152.49  997.65  154.97
 1052.37  160.88 1161.82  166.18 1169.64  167.05 1177.45   170.1 1185.27  174.83
 1193.09  177.53 1310.35   196.7 1365.07  204.07 1411.97  215.44 1455.61  220.18
#Mann= 3 , 0 , 0
       0      .1       0  623.19     .04       0  695.78      .1       0
Bank Sta=623.19,695.78
XS Rating Curve= 0 ,0
Exp/Cntr=0.5,0.3