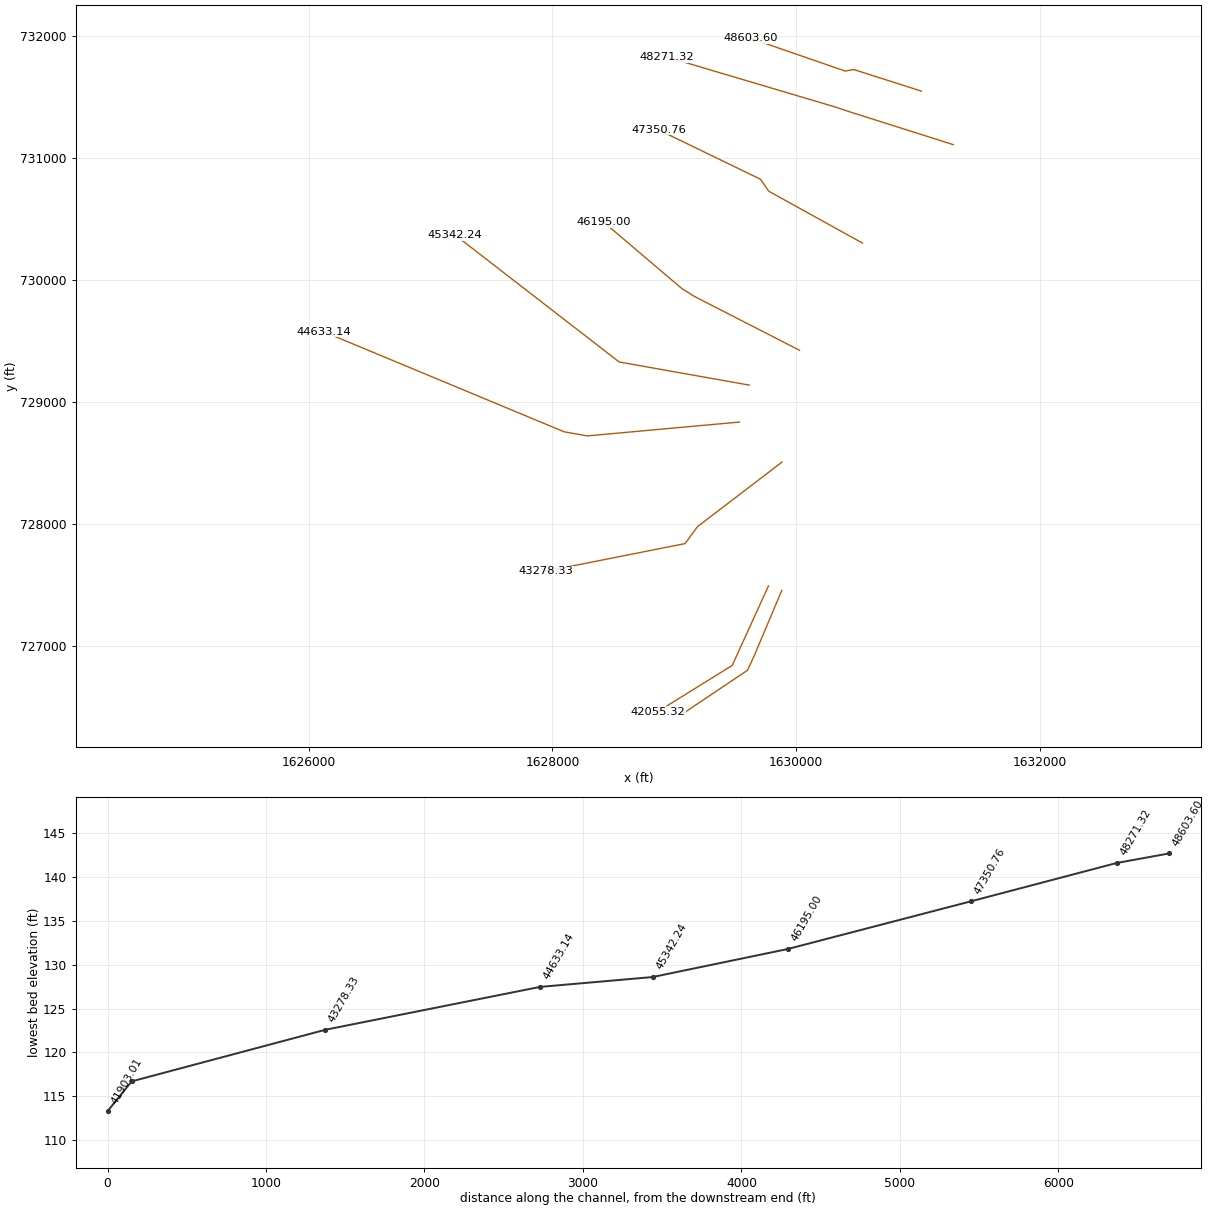
HEC-RAS study LittleElkCreek.prj: Little Elk Creek

--- LittleElkCreek.g01 (geometry) --- (continued)

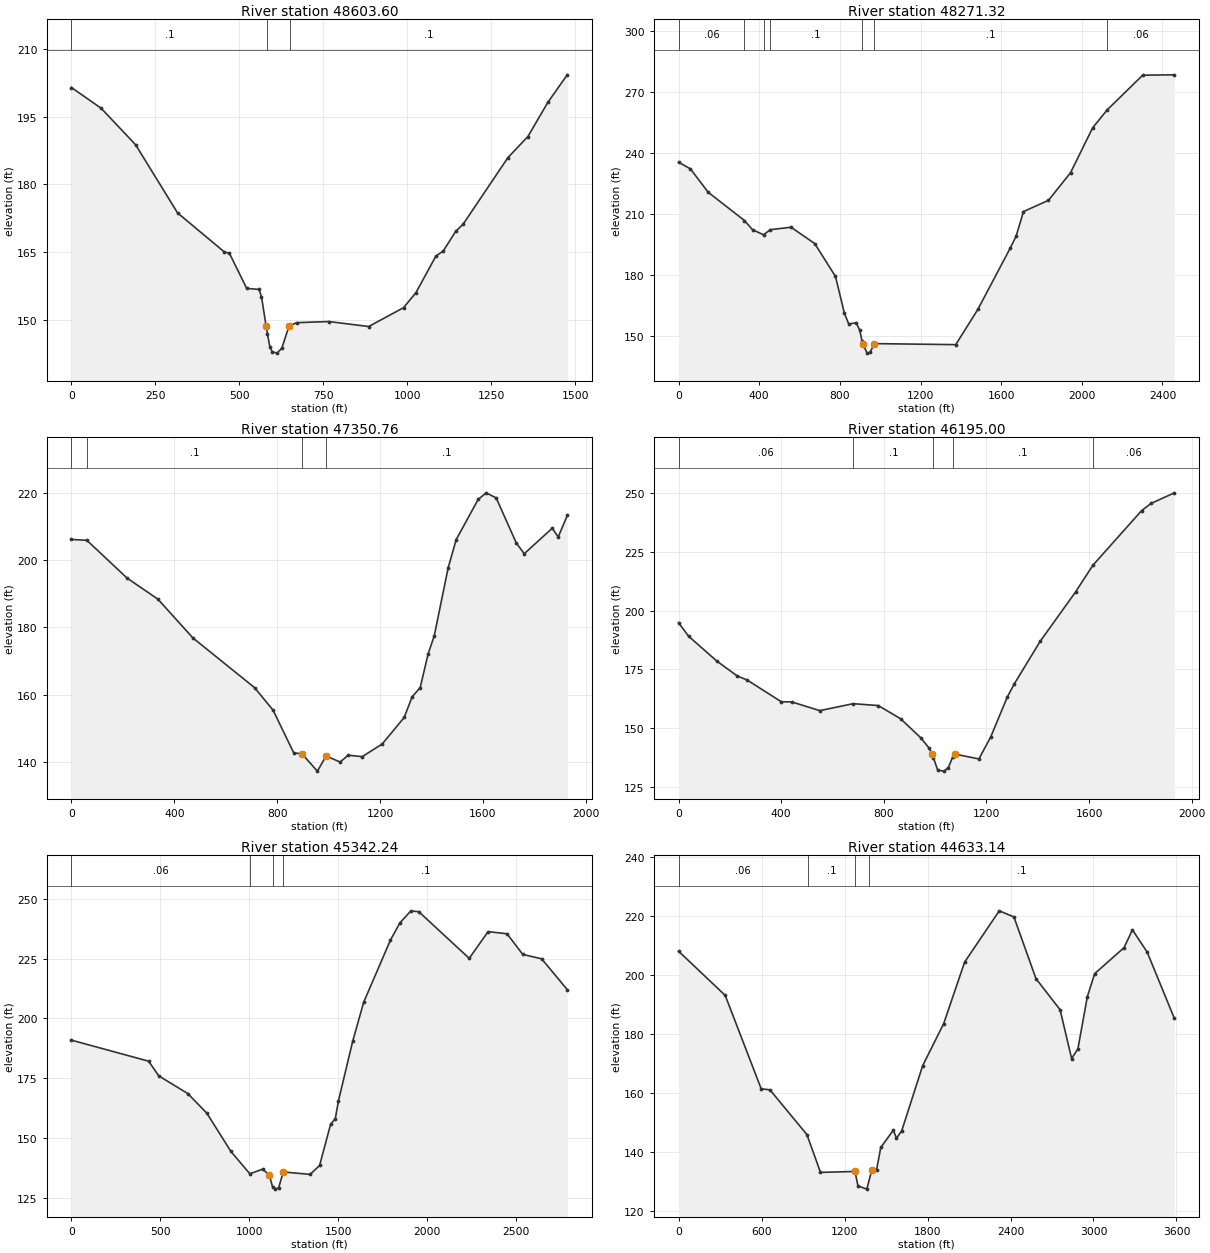
Type RM Length L Ch R = 1 ,48603.60,346.34,332.28,315.31
XS GIS Cut Line= 4
1631028.66487543731549.7831409871630472.72947319731727.242746815
1630402.05971862731714.6792348921629626.26285779731983.224302113
#Sta/Elev= 30
       0  201.45   88.18  196.88  191.05  188.78  315.96   173.7  455.58  165.04
  470.27  164.78  521.71     157  558.45  156.77  565.79  155.19  579.71  148.61
  583.57  146.94  590.68  144.09  597.79  142.98  612.01  142.67  626.23  143.75
  647.56  148.58  649.43   148.7  670.16  149.41  766.46  149.66  884.98  148.56
  988.69  152.72 1025.73  156.05 1084.99  164.13 1107.21  165.29 1144.25  169.64
 1166.47  171.23  1299.8  185.96 1359.06   190.6 1418.32  198.15 1476.31  204.26
#Mann= 3 ,-1 , 0
       0      .1       0  583.57     .04       0  649.43      .1       0
Bank Sta=579.71,647.56
XS Rating Curve= 0 ,0
Exp/Cntr=0.3,0.1

Type RM Length L Ch R = 1 ,48271.32,937.37,920.56,816.41
XS GIS Cut Line= 4
1631289.23064138731111.0256112661630439.52965136731380.237806126
1630313.33643508731422.3022115681628937.83037703731830.326944381
#Sta/Elev= 30
       0  235.41   58.74  232.16  146.86  220.66  326.81206.7598  367.15  202.23
  421.49 199.742  455.18202.2516  558.06  203.45  675.55  195.42  778.35  179.27
  822.41  161.21  844.44  155.84  881.15  156.56  898.71  152.76  910.36  147.47
  913.47  146.01   935.6  141.58  950.36   141.9  970.36  146.26 1374.82  145.75
 1484.34  163.06 1644.98  193.19 1674.18  199.04 1710.69  211.15 1834.82  216.69
 1944.34  230.29 2053.86  252.32 2125.89261.1429 2302.11  278.19  2459.1  278.36
#Mann= 7 ,-1 , 0
       0     .06       0  326.81      .1       0  421.49     .06       0
  455.18      .1       0  910.36     .04       0  970.36      .1       0
 2125.89     .06       0
Bank Sta=913.47,970.36
XS Rating Curve= 0 ,0
Exp/Cntr=0.3,0.1

Type RM Length L Ch R = 1 ,47350.76,1062.62,1155.76,1109.06
XS GIS Cut Line= 4
 1630544.3540131 730303.409394951629774.48019464730729.406241179
1629707.75779703730826.9235914951628871.16158095731232.390469238
#Sta/Elev= 30
       0  206.21   59.95205.9597     216  194.72  336.01  188.44  472.01  176.89
  712.02  162.07  784.02  155.35  864.02  142.68  896.84  142.31  956.21  137.21
  990.14  141.73 1044.71  139.91 1075.82  141.95 1130.27  141.52 1208.06  145.28
 1293.63  153.19 1324.74  159.37 1355.86  162.07 1386.97  172.21 1410.31  177.43
 1464.76  197.81 1495.88  206.18 1581.44  218.15 1612.56   220.1 1651.45  218.56
 1729.24   205.2 1760.36  201.96 1869.26  209.55  1892.6  206.97 1927.71  213.35
#Mann= 4 ,-1 , 0
       0     .06       0   59.95      .1       0  896.84     .04       0
  990.14      .1       0
Bank Sta=896.84,990.14
XS Rating Curve= 0 ,0
Exp/Cntr=0.3,0.1

Type RM Length L Ch R = 1 ,46195.00,784.77,852.76,825.35
XS GIS Cut Line= 4
1630027.29847804729424.2429529431629164.97816642729865.919210121
1629064.02359335729929.0158182831628420.43819006730475.853089049
#Sta/Elev= 30
       0  194.83   39.32  189.06  149.43   178.5  228.08  172.26   267.4  170.48
   401.1  161.21  440.43  161.21  550.53  157.47  680.41160.4257  778.61  159.63
  865.13  154.05  943.78  145.97  977.11  141.46  988.09  138.99  993.62  137.36
 1010.13  132.19 1034.89  131.78  1051.4  133.32 1067.91  137.61 1076.16  139.03
 1170.57  136.97  1216.5  146.24  1280.8  163.15 1308.36  168.81  1409.4  186.91
 1547.18  207.86 1615.13219.2606 1804.38  242.38 1841.12  245.47 1932.43  249.99
#Mann= 5 ,-1 , 0
       0     .06       0  680.41      .1       0  993.62     .04       0
 1067.91      .1       0 1615.13     .06       0
Bank Sta=988.09,1076.16
XS Rating Curve= 0 ,0
Exp/Cntr=0.3,0.1

Type RM Length L Ch R = 1 ,45342.24,660.15,709.1,772.07
XS GIS Cut Line= 3
1629615.37293883729138.3336829541628547.81457718729328.235891521
 1627202.0869548730369.536873832
#Sta/Elev= 30
       0  190.88   433.7  182.08  490.58  175.95  654.11  168.53  760.76  160.34
  895.84  144.34 1002.49     135 1073.59  136.92 1110.87  134.63 1129.94  129.57
 1146.27  128.59 1163.97  129.11 1190.12  135.77 1340.99  134.75 1394.09  138.48
 1456.05  155.67  1482.6  158.09  1500.3  165.55 1579.96  190.36 1641.92  206.75
 1792.38  232.73 1845.49  239.94 1907.44  244.96  1951.7  244.59 2234.92  225.09
 2341.13  236.26 2447.34  235.37 2535.85  226.73 2642.06  224.89 2785.86  211.99
#Mann= 4 ,-1 , 0
       0     .06       0 1002.49      .1       0 1129.94    .045       0
 1190.12      .1       0
Bank Sta=1110.87,1190.12
XS Rating Curve= 0 ,0
Exp/Cntr=0.3,0.1

Type RM Length L Ch R = 1 ,44633.14,1192.54,1354.81,1372.74
XS GIS Cut Line= 4
1629535.14493434 728835.341276721628285.83209267728721.767382026
1628096.54226811728755.4189063911626122.61454813729576.704032764
#Sta/Elev= 30
       0  207.99  337.39  193.02  597.45  161.43  660.71  161.07  927.81  145.95
 1026.21  133.13 1275.79  133.45 1297.12  128.55 1361.11  127.47 1396.66  133.85
 1432.21  134.11 1461.88  141.56 1552.86  147.41 1575.61  144.69 1613.52  147.21
 1765.15  169.27 1916.78  183.45 2068.42  204.29 2318.62  221.64 2424.76  219.56
 2583.98  198.71 2758.36  188.18 2841.76  171.66 2887.25  174.92 2955.49  192.59
 3008.56  200.39 3220.85  209.18  3281.5   215.2 3387.65  207.72  3584.7  185.23
#Mann= 4 ,-1 , 0
       0     .06       0     935      .1       0 1275.79    .045       0
 1378.48      .1       0
Bank Sta=1275.79,1396.66
XS Rating Curve= 0 ,0
Exp/Cntr=0.3,0.1

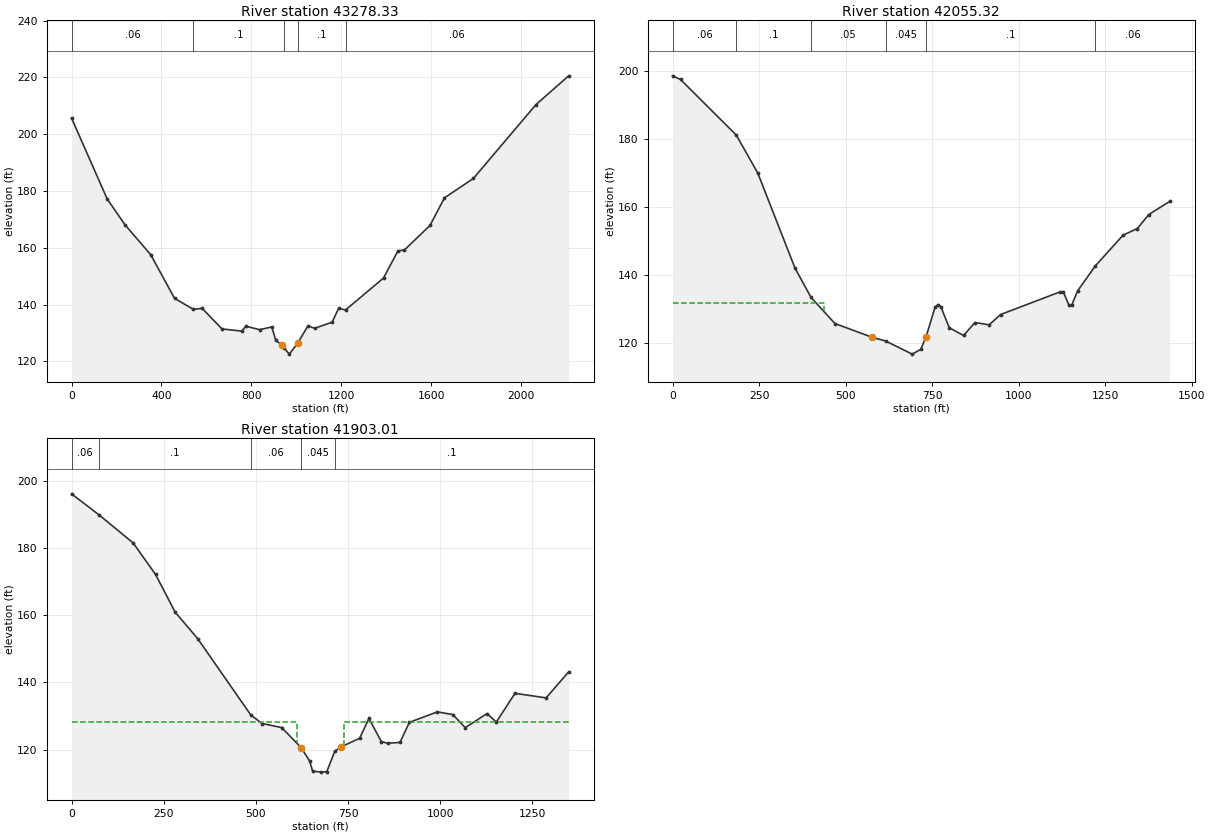
Type RM Length L Ch R = 1 ,43278.33,1145.11,1223.01,1167.51
XS GIS Cut Line= 4
1629884.27949955728507.2389142661629190.21680969727977.227405667
1629089.26223664727838.4148676991627945.61007017727611.595996141
#Sta/Elev= 30
       0  205.71  158.54  177.22  237.81  168.13   352.3  157.59     458  142.24
  541.44138.3838   581.3  138.68  669.38  131.45  757.45   130.7  775.07  132.41
  836.72  131.21   890.6  132.16  907.91   127.5  933.88  125.86  945.58  124.71
   968.5  122.59 1005.94  126.48 1052.07  132.61 1080.61  131.66 1159.11  133.84
 1187.66  138.69 1218.85138.1526 1387.48  149.38  1451.7  158.95 1480.25  159.23
 1594.43  167.92 1658.66  177.62 1787.11  184.43 2065.43  210.43 2210.86  220.57
#Mann= 5 ,-1 , 0
       0     .06       0  541.44      .1       0  945.58    .045       0
 1005.94      .1       0 1218.85     .06       0
Bank Sta=933.88,1005.94
XS Rating Curve= 0 ,0
Exp/Cntr=0.3,0.1

Type RM Length L Ch R = 1 ,42055.32,133.88,152.31,145.83
BEGIN DESCRIPTION:
Ineffective flow limits set to restrict backwater area for 100 year profiles.
END DESCRIPTION:
XS GIS Cut Line= 3
1629772.81239022727491.0344287311629475.08184281 726838.43312785
1628863.77557732726459.700563878
#Sta/Elev= 30
       0  198.62   23.08  197.54  184.01181.2016  246.21  170.03  353.93  142.01
  400.09  133.42  469.34  125.71  577.06  121.65  615.53  120.58  692.47  116.71
  717.31   118.1  732.58   121.8  758.48   130.5  766.72   131.3  774.95  130.71
  799.65  124.47  840.83   122.2  873.77     126  914.94  125.34  947.88  128.37
  1120.8  135.07 1129.04  135.07 1145.51  131.07 1153.74   131.2 1170.21  135.29
 1221.97142.7184 1301.96  151.73 1343.14  153.68 1376.08   157.8 1436.43  161.65
#Mann= 6 ,-1 , 0
       0     .06       0  184.01      .1       0  400.09     .05       0
  615.53    .045       0  732.58      .1       0 1221.97     .06       0
#XS Ineff= 2 ,-1
   -1.44  437.61 131.816  766.96 1436.43131.2453
Permanent Ineff=
       F       F
Bank Sta=577.06,732.58
XS Rating Curve= 0 ,0
Exp/Cntr=0.5,0.3

Type RM Length L Ch R = 1 ,41903.01,75.88,75.38,98.7
BEGIN DESCRIPTION:
Under water portion adjusted as per bridge inspection notes.
END DESCRIPTION:
XS GIS Cut Line= 4
1629882.11189342727454.2896481451629654.95404543726916.151633248
1629600.24263491726798.5803041461629073.37422185726445.409747198
#Sta/Elev= 30
       0  196.13   74.55189.8711  167.16  181.51  227.94  172.13  281.13  160.91
  341.91  153.07  486.28   130.3  516.67  127.77  569.86  126.58  622.72   120.6
  645.88  116.58   653.6  113.63  676.77  113.31  692.21  113.45   713.8  119.47
  730.65  120.81  781.21  123.37  806.49  129.28   840.2  122.38  857.06  121.91
  890.77  122.15  916.05  128.11  991.89  131.24 1034.03  130.44 1067.74  126.55
 1126.73  130.74 1152.01  128.21 1202.57  136.76 1286.84  135.41 1348.08  143.14
#Mann= 5 ,-1 , 0
       0     .06       0   74.55      .1       0  486.28     .06       0
  622.72    .045       0   713.8      .1       0
#XS Ineff= 2 , 0
       0     611   128.1     739       0   128.3
Permanent Ineff=
       F       F
Bank Sta=622.72,730.65
XS Rating Curve= 0 ,0
Exp/Cntr=0.5,0.3