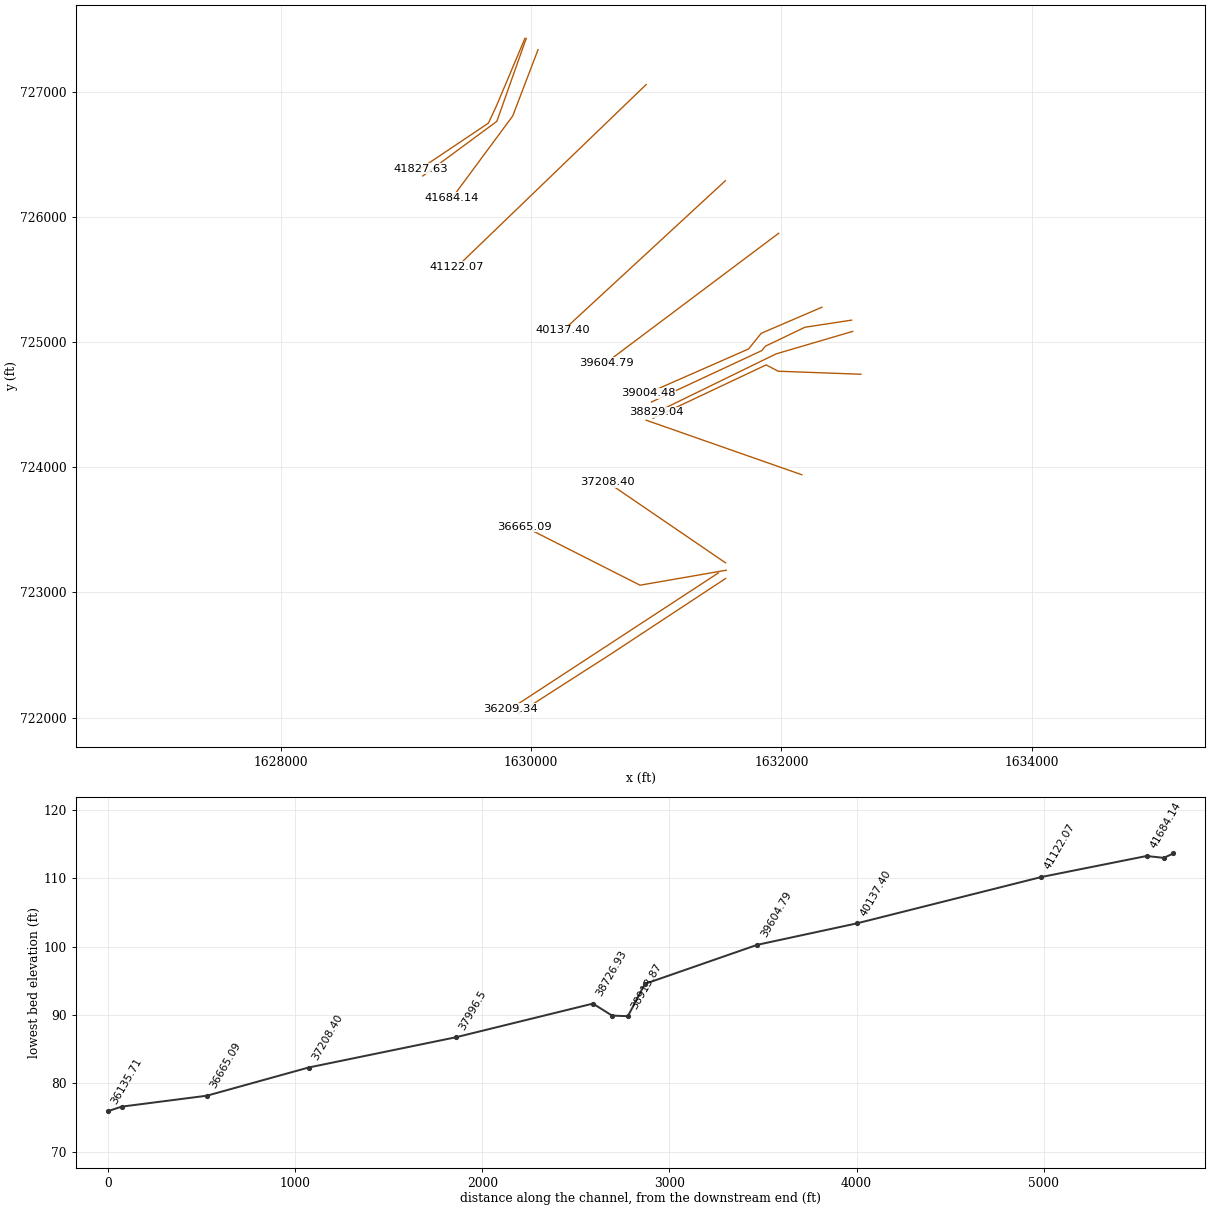
HEC-RAS study LittleElkCreek.prj: Little Elk Creek

--- LittleElkCreek.g01 (geometry) --- (continued)

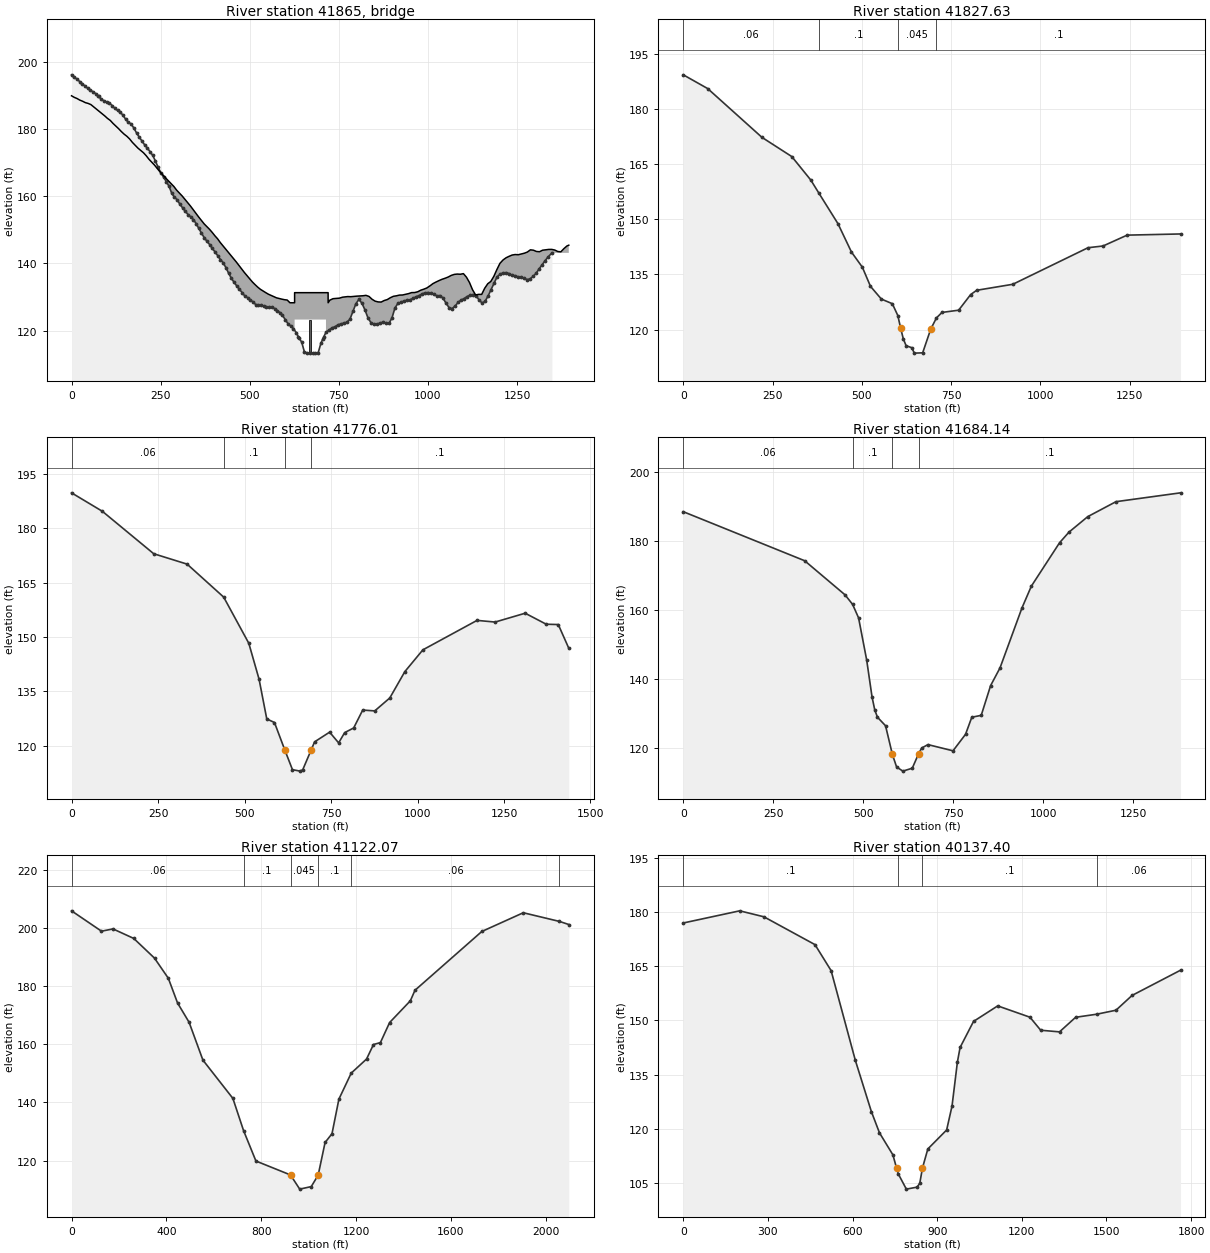
Type RM Length L Ch R = 3 ,41865   ,,,
BEGIN DESCRIPTION:
Leeds Road.  CE050307PF-1.  Top of bridge elevation extracted from lidar embankments.  Bridge geometry from pictures and bridge inspection viewer.
END DESCRIPTION:
Bridge Culvert--1,0,-1,-1, 0
Deck Dist Width WeirC Skew NumUp NumDn MinLoCord MaxHiCord MaxSubmerge Is_Ogee
20,31,2.6,0, 168, 168, , , 0.95, 0, 0,0,,
       0    7.76   15.53   23.29   31.06   38.82   46.59   54.35   62.12   69.88
   77.65   85.41   93.18  100.94  108.71  116.47  124.24     132  139.77  147.53
   155.3  163.06  170.83  178.59  186.36  194.12  201.89  209.65  217.42  225.18
  232.95  240.71  248.48  256.24     264  271.77  279.53   287.3  295.06  302.83
  310.59  318.36  326.12  333.89  341.65  349.42  357.18  364.95   372.3  379.81
  387.32  394.83  402.34  409.85  417.36  424.87  432.38  439.89   447.4  454.91
  462.42  469.93  477.44  484.95  492.46  499.97  507.48  514.99   522.5  530.01
  537.52  545.03  552.54  560.05  567.56  575.07  582.14  589.83  597.53  605.22
  612.91     620  625.99     626     714   714.1     720   720.1  724.78  733.75
  742.71  751.68  760.64  769.61  774.98  783.52  792.06  800.61  809.15   817.7
  826.24  834.79  843.33  851.88  860.42  868.96  877.51  886.05   894.6  903.14
  911.69  920.23  928.78  937.32  945.86  954.41  962.95   971.5  980.04  988.59
  997.13 1005.68 1014.22 1022.76 1031.31 1039.85  1048.4 1056.94 1065.49 1074.03
 1082.58 1091.12 1099.66 1108.21 1116.75  1125.3 1133.84 1142.39 1150.93 1159.48
 1168.02 1176.56 1185.11 1193.65  1202.2 1210.74 1219.29 1227.83 1236.38 1244.92
 1253.46 1262.01 1270.55  1279.1 1287.64 1296.19 1304.73 1313.28 1321.82 1330.36
 1338.91 1347.45    1356 1364.54 1373.09 1381.63 1390.18 1395.38
  189.89  189.42  189.07   188.6  188.27  187.85  187.62  187.27   186.6   185.9
  185.23  184.56  183.91  183.16  182.56  181.67  180.88  180.11  179.25  178.48
  177.84  177.04  176.02  175.16  174.32  173.65  172.94  172.04  170.99  170.12
  169.26  168.24  167.22  166.37  165.44   164.6  163.74  162.89   161.8  160.95
  160.06  159.05  158.01  157.07  155.96  154.84  153.77  152.75  151.76  150.94
  150.15  149.23  148.23  147.34  146.23  145.25  144.32  143.31  142.36  141.42
  140.43  139.38  138.31  137.32  136.35  135.43   134.5   133.7  132.95   132.3
   131.8  131.31  130.84   130.5  130.13  129.77  129.57  129.38  129.21  129.11
   128.3   128.3   128.3   131.3   131.3   131.3   131.3   128.3  129.07  129.51
  129.58  129.67  129.96  130.09  130.14   130.1  130.19  130.27  130.33  130.38
   130.5  130.18  129.34  128.78  128.55  128.51  128.97  129.25   129.8  130.22
  130.37  130.58  130.61   130.8  131.02  131.32  131.34  131.57  132.04  132.34
  132.71  133.32     134  134.47   134.9  135.29   135.6  135.96  136.44  136.74
  136.84  136.78  136.97  135.91  134.32  132.17  130.64  130.79  130.79  132.63
  133.96  134.64  136.17  138.19  140.03  141.02  141.68  142.12   142.5  142.65
  142.59  142.82  143.04  143.39  144.05  143.94  143.56  143.49  143.94  144.06
  144.17  144.18  143.99  143.55  143.46   144.4   145.2  145.43
                                                                                
                                                                                
                                                                                
                                                                                
                                                                                
                                                                                
                                                                                
                                                                                
                           123.3   123.3
                                                                                
                                                                                
                                                                                
                                                                                
                                                                                
                                                                                
                                                                                
                                                                
     -10   -2.24    5.53   13.29   21.06   28.82   36.59   44.35   52.12   59.88
   67.65   75.41   83.18   90.94   98.71  106.47  114.24     122  129.77  137.53
   145.3  153.06  160.83  168.59  176.36  184.12  191.89  199.65  207.42  215.18
  222.95  230.71  238.48  246.24     254  261.77  269.53   277.3  285.06  292.83
  300.59  308.36  316.12  323.89  331.65  339.42  347.18  354.95   362.3  369.81
  377.32  384.83  392.34  399.85  407.36  414.87  422.38  429.89   437.4  444.91
  452.42  459.93  467.44  474.95  482.46  489.97  497.48  504.99   512.5  520.01
  527.52  535.03  542.54  550.05  557.56  565.07  572.14  579.83  587.53  595.22
  602.91     610  615.99     616     704   704.1     710   710.1  714.78  723.75
  732.71  741.68  750.64  759.61  764.98  773.52  782.06  790.61  799.15   807.7
  816.24  824.79  833.33  841.88  850.42  858.96  867.51  876.05   884.6  893.14
  901.69  910.23  918.78  927.32  935.86  944.41  952.95   961.5  970.04  978.59
  987.13  995.68 1004.22 1012.76 1021.31 1029.85  1038.4 1046.94 1055.49 1064.03
 1072.58 1081.12 1089.66 1098.21 1106.75  1115.3 1123.84 1132.39 1140.93 1149.48
 1158.02 1166.56 1175.11 1183.65  1192.2 1200.74 1209.29 1217.83 1226.38 1234.92
 1243.46 1252.01 1260.55  1269.1 1277.64 1286.19 1294.73 1303.28 1311.82 1320.36
 1328.91 1337.45    1346 1354.54 1363.09 1371.63 1380.18 1385.38
  189.89  189.42  189.07   188.6  188.27  187.85  187.62  187.27   186.6   185.9
  185.23  184.56  183.91  183.16  182.56  181.67  180.88  180.11  179.25  178.48
  177.84  177.04  176.02  175.16  174.32  173.65  172.94  172.04  170.99  170.12
  169.26  168.24  167.22  166.37  165.44   164.6  163.74  162.89   161.8  160.95
  160.06  159.05  158.01  157.07  155.96  154.84  153.77  152.75  151.76  150.94
  150.15  149.23  148.23  147.34  146.23  145.25  144.32  143.31  142.36  141.42
  140.43  139.38  138.31  137.32  136.35  135.43   134.5   133.7  132.95   132.3
   131.8  131.31  130.84   130.5  130.13  129.77  129.57  129.38  129.21  129.11
   128.3   128.3   128.3   131.3   131.3   131.3   131.3   128.3  129.07  129.51
  129.58  129.67  129.96  130.09  130.14   130.1  130.19  130.27  130.33  130.38
   130.5  130.18  129.34  128.78  128.55  128.51  128.97  129.25   129.8  130.22
  130.37  130.58  130.61   130.8  131.02  131.32  131.34  131.57  132.04  132.34
  132.71  133.32     134  134.47   134.9  135.29   135.6  135.96  136.44  136.74
  136.84  136.78  136.97  135.91  134.32  132.17  130.64  130.79  130.79  132.63
  133.96  134.64  136.17  138.19  140.03  141.02  141.68  142.12   142.5  142.65
  142.59  142.82  143.04  143.39  144.05  143.94  143.56  143.49  143.94  144.06
  144.17  144.18  143.99  143.55  143.46   144.4   145.2  145.43
                                                                                
                                                                                
                                                                                
                                                                                
                                                                                
                                                                                
                                                                                
                                                                                
                           123.3   123.3
                                                                                
                                                                                
                                                                                
                                                                                
                                                                                
                                                                                
                                                                                
                                                                
Pier Skew, UpSta & Num, DnSta & Num=  ,670, 3 ,660, 3 , 0 , 0 , 0 ,,
       6       6       2
       0     115     130
       6       6       2
       0     115     130
BR Coef=-1 , 1 , 0 ,, 0 ,,,0.8,0,0.5,0,
WSPro=,,,, 1 ,,,, 0 ,,,, 0 ,,,,-1 ,-1 ,-1 , 0 , 0 , 0 , 0 , 0
BR U #Sta/Elev= 173
       0  196.13     7.6  195.47    15.2  194.86   22.79  194.12   30.39  193.42
   37.99  192.78   45.59  192.09   53.19  191.51   60.78  191.06   68.38  190.48
   74.55 189.871   75.98  189.73   83.58  188.88   91.18  188.38   98.78  188.05
  106.37  187.68  113.97     187  121.57  186.13  129.17  185.53  136.77  184.99
  144.36  184.12  151.96   182.9  159.56     182  167.16  181.51  174.76  180.32
  182.35  178.87  189.95  177.61  197.55  176.44  205.15   175.3  212.75  174.32
  220.34  173.27  227.94  172.13  235.54  170.44  243.14  168.58  250.74     167
  258.34  165.68  265.93  164.35  273.53  162.97  281.13  160.91  288.73   159.7
  296.33  158.95  303.92  157.64  311.52  156.56  319.12  155.55  326.72  154.56
  334.32  153.86  341.91  153.07  349.51  151.86  357.11  150.44  364.71     149
  372.31  147.68   379.9  146.59   387.5  145.63   395.1  144.47   402.7  143.42
   410.3  142.27  417.89  141.15  425.49  140.17  433.09  138.79  440.69  137.12
  448.29  135.62  455.89  134.42  463.48  133.33  471.08  132.32  478.68  131.28
  486.28   130.3  493.88  129.81  501.47  129.14  509.07  128.55  516.67  127.77
  524.27  127.53  531.87  127.49  539.46  127.32  547.06  127.08  554.66  126.97
  562.26  126.91  569.86  126.58  577.45  125.94  584.12   125.4  591.84  124.56
  599.56  123.29  607.28  122.07     615  121.32  622.72   120.6  630.44  119.43
  636.29  118.25  638.16  117.87  645.88  116.58   653.6  113.63  661.33  113.38
  669.05  113.35  676.77  113.31  684.49  113.37  692.21  113.45  699.93  116.28
  705.05   117.5  707.65  118.12   713.8  119.47  722.22  120.13  730.65  120.81
  739.08  121.14   747.5  121.72  755.93  121.98  764.36  122.27  772.79   122.5
  781.21  123.37  789.64  125.73  798.07  128.02  806.49  129.28  814.92  128.16
  823.35  126.18  831.78  123.82   840.2  122.38  848.63  121.94  857.06  121.91
  865.48  122.25  873.91   122.5  882.34  122.21  890.77  122.15  899.19  123.76
  907.62  126.76  916.05  128.11  924.48  128.42   932.9   128.8  941.33  129.05
  949.76  129.18  958.18  129.59  966.61  130.06  975.04  130.41  983.47  130.91
  991.89  131.24 1000.32  131.33 1008.75  131.14 1017.17  130.76  1025.6  130.34
 1034.03  130.44 1042.46  129.67 1050.88  128.17 1059.31  126.87 1067.74  126.55
 1076.16  127.27 1084.59  128.38 1093.02  129.08 1101.45  129.53 1109.87  130.13
  1118.3  130.55 1126.73  130.74 1135.15  130.39 1143.58  129.15 1152.01  128.21
 1160.44  128.69 1168.86   130.3 1177.29  132.21 1185.72  134.14 1194.14     136
 1202.57  136.76    1211  137.19 1219.43  137.26 1227.85  136.97 1236.28  136.44
 1244.71  136.34 1253.13     136 1261.56  135.95 1269.99  135.61 1278.42  135.16
 1286.84  135.41 1295.27  136.13  1303.7  137.04 1312.12  138.38 1320.55  139.59
 1328.98  140.83  1337.4  141.93 1348.08  143.14
BR U #Mann= 4
       0     .06   74.55      .1  622.72     .04   713.8      .1
BR D #Sta/Elev= 183
       0   189.8    7.43  189.26   14.85  188.76   22.28  188.44    29.7  187.78
   37.13  187.45   44.55  186.95   51.98  186.66    59.4  186.23   66.83  185.85
   74.25  185.56   81.68  185.14   89.11   184.7   96.53  183.91  103.96  183.05
  111.38  182.28  118.81  181.87  126.23  181.41  133.66  180.75  141.08   180.1
  148.51  179.59  155.93     179  163.36  178.64  170.78  178.14  178.21   177.4
  185.64  176.68  193.06  176.09  200.49  175.63  207.91  175.03  215.34  174.48
  222.76  174.14  230.19  173.68  237.61  172.98  245.04  172.92  252.46   172.8
  259.89  172.61  267.32   172.5  274.74  172.26  282.17  172.08  289.59  172.17
  297.02  172.02  304.44  171.63  311.87  171.24  319.29  170.94  326.72  170.45
  334.14  170.11  341.57  169.42  348.99  168.78  356.42  168.12  363.85  167.46
  371.27  166.79   378.7  166.26  386.12   165.7  393.55  164.95  400.97  164.47
   408.4  163.35  415.82  162.11  423.25  161.62  430.67  161.21   438.1  161.14
   439.8 161.003  445.53  160.54  452.95  158.52  460.38  157.24   467.8  156.74
  475.23  154.62  482.65  152.95  490.08  152.33   497.5  151.09  504.93  149.87
  512.35  148.27  519.78  145.76   527.2   143.4  534.63  140.96  542.06  138.34
  549.48  134.53  556.91  130.34  564.33  127.37  571.76  127.15  579.18  126.96
  586.61  126.38  594.03  125.02  601.46     123  608.88  120.91  616.31  118.83
  623.73  117.21  631.16  115.62  632.54  115.39  638.59  113.36  646.01  113.01
  653.44  113.02  660.86  112.96  668.29  113.34  675.71  115.36  683.14  116.64
  690.56  118.28  692.47  118.77  697.99   120.2  702.49  121.04  711.19  121.25
  719.89  121.21  728.58  121.86  737.28  123.21  745.97  123.72  754.67  122.63
  763.37  120.95  772.06  120.76  780.76  122.11  789.45  123.59  798.15  124.12
  806.85  124.59  815.54  124.88  824.24  126.11  832.94  128.58  841.63  129.82
  850.33  129.85  859.02  129.57  867.72  129.45  876.42  129.59  885.11  130.12
  893.81  130.94  902.51  131.86   911.2  132.62   919.9  133.16  928.59  134.45
  937.29  136.34  945.99  137.47  954.68  139.19  963.38  140.43  972.08  141.44
  980.77   142.6  989.47  143.51  998.16  144.48 1006.86  145.62 1015.56  146.45
 1024.25  146.75 1032.95  147.63 1041.65  148.04 1050.34  149.01 1059.04  149.58
 1067.73  149.79 1076.43  149.83 1085.13  150.29 1093.82  151.35 1102.52   151.9
 1111.21  152.05 1119.91     152 1128.61     152  1137.3  152.31    1146  152.67
  1154.7   153.3 1163.39  153.91 1172.09  154.58 1180.78  154.88 1189.48  154.79
 1198.18  154.75 1206.87  154.53 1215.57  154.08 1224.26  154.12 1232.96  154.91
 1241.66  154.82 1250.35   154.8 1259.05  155.51 1267.75  155.96 1276.44  156.27
 1285.14  156.44 1293.83  156.64 1302.53  156.74 1311.23  156.56 1319.92  156.19
 1328.62  156.05 1337.32  155.67 1346.01  155.23 1354.71  154.68  1363.4  153.95
  1372.1  153.52  1380.8  153.42 1389.49  153.51 1398.19  153.78 1406.88  153.43
 1415.58  151.54 1424.28  149.37 1437.26  146.89
BR D #Mann= 4
       0     .06   439.8      .1  616.31     .04  692.47      .1
BR D Banks=601.46,702.49
BC Design=,, 0 ,, 0 ,,,,,,
BC Use User HTab Curves=0
BC User HTab FreeFlow(D)= 0

Type RM Length L Ch R = 1 ,41827.63,45.65,51.62,47.32
BEGIN DESCRIPTION:
Under water portion adjusted as per bridge inspection notes.
END DESCRIPTION:
XS GIS Cut Line= 4
1629951.20818594727425.1228457991629723.52359597726885.736976609
1629659.40280926 726747.945498691629115.13418129726383.111225635
#Sta/Elev= 30
       0  189.25   68.38  185.51  220.34  172.25  303.92  167.03  357.11  160.65
   379.9  157.07  433.09  148.81  471.08  141.07  501.47  136.97  524.27  131.76
  554.66  128.31  585.47  127.04  600.91  123.81  608.63  120.43  616.35  117.44
  624.08  115.63  639.52   115.1  647.24  113.61   670.4  113.69     693  120.13
     709  123.18  724.45  124.67  771.16  125.28  804.87  129.53  821.72  130.69
  922.85  132.32 1133.53  142.26 1175.66  142.73 1243.08  145.68 1392.69     146
#Mann= 4 ,-1 , 0
       0     .06       0   379.9      .1       0  600.91    .045       0
     709      .1       0
#XS Ineff= 2 , 0
       0     591   124.5     729       0   124.5
Permanent Ineff=
       F       F
Bank Sta=608.63,693
XS Rating Curve= 0 ,0
Exp/Cntr=0.5,0.3

Type RM Length L Ch R = 1 ,41776.01,106.47,91.87,82.47
BEGIN DESCRIPTION:
Under water portion adjusted as per bridge inspection notes.
END DESCRIPTION:
XS GIS Cut Line= 3
1629961.11419424727424.5327224431629726.74810469726762.287258297
1629135.30109409726326.319608271
#Sta/Elev= 30
       0   189.8   89.11   184.7  237.61  172.98  334.14  170.11   439.8161.0027
  512.35  148.27  542.06  138.34  564.33  127.37  586.61  126.38  616.31  118.83
  638.59  113.36  660.86  112.96  668.29  113.34  692.47  118.77  702.49  121.04
  745.97  123.72  772.06  120.76  789.45  123.59  815.54  124.88  841.63  129.82
  876.42  129.59   919.9  133.16  963.38  140.43 1015.56  146.45 1172.09  154.58
 1224.26  154.12 1311.23  156.56  1372.1  153.52 1406.88  153.43 1437.26  146.89
#Mann= 4 ,-1 , 0
       0     .06       0   439.8      .1       0  616.31    .045       0
  692.47      .1       0
Bank Sta=616.31,692.47
XS Rating Curve= 0 ,0
Exp/Cntr=0.3,0.1

Type RM Length L Ch R = 1 ,41684.14,576.32,562.08,539.09
XS GIS Cut Line= 3
1630055.70065217 727334.548322291629853.60681371  726805.2902105
1629368.71776637 726150.06620267
#Sta/Elev= 30
       0  188.54  337.18  174.31  449.58  164.39  470.46161.6304  487.04  157.71
  509.52   145.5  524.51  134.72     532  130.99  539.49  128.88  561.97   126.4
  580.99  118.07  592.65  114.44  610.07  113.23   636.2  114.08  653.61  118.23
  662.32  119.93  679.74  120.93   749.4  119.13  784.24  123.92  801.65  128.88
  827.78  129.42   853.9  138.06  880.03   143.2  940.99   160.6  967.11  166.93
 1045.49  179.53 1071.61  182.61 1123.86  187.11 1202.24  191.45 1381.66  194.02
#Mann= 4 ,-1 , 0
       0     .06       0  470.46      .1       0  580.99    .045       0
  653.61      .1       0
Bank Sta=580.99,653.61
XS Rating Curve= 0 ,0
Exp/Cntr=0.3,0.1

Type RM Length L Ch R = 1 ,41122.07,979.77,984.67,982.15
XS GIS Cut Line= 2
1630919.06387345727056.0169264231629408.95171802725600.588498071
#Sta/Elev= 30
       0  205.82  126.38  198.82  174.99   199.6  262.49  196.33  349.99  189.56
  408.32  182.63  447.21  174.14  495.82  167.52  554.15  154.51  680.53  141.35
  725.46130.3073  777.75  119.82  923.58  115.03  962.47  110.16 1011.08  111.03
 1040.25  114.97 1069.41  126.19 1098.58  129.21 1127.74   141.1 1179.74150.0423
 1244.41  154.88 1273.57  159.87 1302.74  160.52 1341.62  167.42 1429.12   174.9
 1448.57  178.51  1730.5  198.72  1905.5  205.16 2058.09202.1728 2097.31  201.12
#Mann= 6 ,-1 , 0
       0     .06       0  725.46      .1       0  923.58    .045       0
 1040.25      .1       0 1179.74     .06       0 2058.09      .1       0
Bank Sta=923.58,1040.25
XS Rating Curve= 0 ,0
Exp/Cntr=0.3,0.1

Type RM Length L Ch R = 1 ,40137.40,521.29,532.6,512.02
XS GIS Cut Line= 2
1631551.84249461726288.0770276781630256.56043325725092.432047948
#Sta/Elev= 30
       0  176.94  200.05   180.3  285.79  178.65  466.79  170.96  523.95  163.78
  609.69  139.03  666.85  124.79  695.42  118.95  743.06  112.86  756.14  109.17
  762.11   107.6  790.69  103.39  828.79  103.94  838.32  105.01  847.85  109.23
   866.9  114.49  933.58  119.74  952.64  126.35  971.69  138.51  981.22  142.54
 1028.85  149.74 1114.58  154.03  1228.9   150.9 1267.01   147.3 1333.69  146.85
 1390.85  150.88 1465.21151.7234 1533.74  152.83  1590.9  156.92 1762.76  163.89
#Mann= 4 ,-1 , 0
       0      .1       0  762.11    .045       0  847.85      .1       0
 1465.21     .06       0
Bank Sta=756.14,847.85
XS Rating Curve= 0 ,0
Exp/Cntr=0.3,0.1

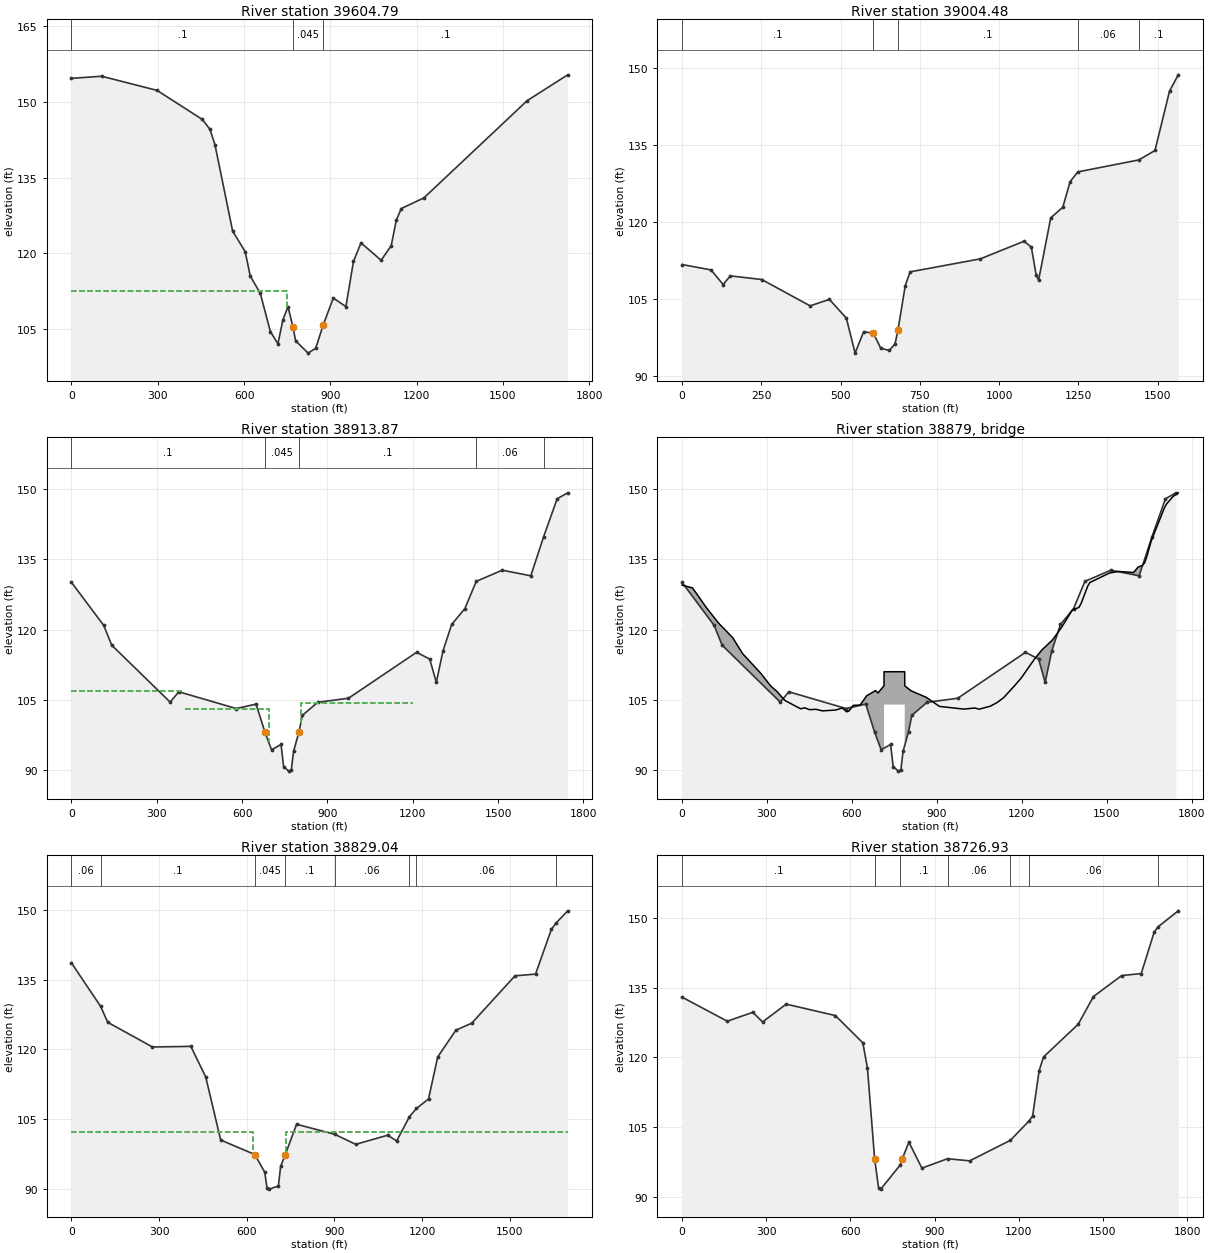
Type RM Length L Ch R = 1 ,39604.79,592.63,600.32,609.71
XS GIS Cut Line= 2
1631977.42184176725868.3710697741630597.76824529724833.123342797
#Sta/Elev= 30
       0   154.7  105.02  155.12  297.55  152.31  455.08  146.55  481.34   144.6
  498.84  141.54   560.1  124.46  603.86  120.35  621.36  115.55  656.37  112.09
  691.37  104.52  717.63   102.1  735.13  106.88  752.63  109.44  770.14  105.39
  778.89  102.71  822.64  100.25   848.9  101.21  875.15  105.84  910.16  111.17
  953.92  109.47  980.17  118.41 1006.43   122.1 1076.44  118.65 1111.45  121.54
 1128.95  126.56 1146.45   128.9 1225.22  131.02 1584.03  150.28 1724.87   155.4
#Mann= 3 ,-1 , 0
       0      .1       0  770.14    .045       0  875.15      .1       0
#XS Ineff= 1 ,-1
   -1.62  750.32112.4648
Permanent Ineff=
       F
Bank Sta=770.14,875.15
XS Rating Curve= 0 ,0
Exp/Cntr=0.3,0.1

Type RM Length L Ch R = 1 ,39004.48,101.79,90.6,82.98
XS GIS Cut Line= 4
1632322.86870646725277.7412699911631837.95401266725069.293777138
1631737.02154244724944.2252814471630934.79385905724591.729019016
#Sta/Elev= 30
       0   111.8   91.43  110.75  129.53  107.91  152.39  109.59  251.44  108.88
  403.83  103.75  464.78  105.01  518.12  101.35  545.81   94.54  572.79   98.73
  603.54   98.39  626.77   95.47  653.75   95.07  671.74   96.37  680.74   98.96
  703.83  107.67  719.12  110.37  940.85  112.91 1078.48  116.34 1101.42   115.2
 1116.71  109.77 1124.35  108.74 1162.58  120.88 1200.81  122.98 1223.75  127.95
 1247.77129.8441 1440.55132.1829 1491.36  134.02 1537.24  145.59 1564.79  148.76
#Mann= 5 ,-1 , 0
       0      .1       0  603.54    .045       0  680.74      .1       0
 1247.77     .06       0 1440.55      .1       0
Bank Sta=603.54,680.74
XS Rating Curve= 0 ,0
Exp/Cntr=0.5,0.3

Type RM Length L Ch R = 1 ,38913.87,93.24,84.84,85.88
BEGIN DESCRIPTION:
Under water portion adjusted as per bridge inspection notes.  Left ineffective flow limit set for backwater area.
END DESCRIPTION:
XS GIS Cut Line= 5
 1632559.8405931725174.6146156341632186.82929011725117.565828115
1631870.86677469724966.1671227961631842.34238094724931.060176626
1630961.77258244724520.603293747
#Sta/Elev= 30
       0  130.05   113.3  120.88  141.63  116.65  346.99  104.52  377.35  106.73
  579.16  103.16  649.02   104.1  680.07   98.13  703.36   94.37  736.73    95.5
  745.75   90.79  763.79   89.82  772.94   90.09  780.67   94.03  800.19   98.26
  811.56  101.69  865.62  104.49  973.74  105.35 1213.16  115.14  1259.5   113.7
 1282.67  108.72 1305.84  115.39 1336.73  121.08 1383.07  124.46 1422.97130.2598
 1514.36  132.64 1614.77  131.45 1660.05139.7938 1707.44  147.86 1744.48  149.13
#Mann= 5 ,-1 , 0
       0      .1       0  680.07    .045       0  800.19      .1       0
 1422.97     .06       0 1660.05      .1       0
#XS Ineff= 3 ,-1
       0  390.83 106.994     400     693  103.16     806    1200  104.29
Permanent Ineff=
       F       F       F
Bank Sta=680.07,800.19
XS Rating Curve= 0 ,0
Exp/Cntr=0.5,0.3

Type RM Length L Ch R = 3 ,38879   ,,,
BEGIN DESCRIPTION:
Childs Road.  CE050307PF-2. Bridge elevation taken from LIDAR abutment elevations.  Bridge geometry taken from Bridge Inventory and Photographs.
END DESCRIPTION:
Bridge Culvert--1,0,-1,-1, 0
Deck Dist Width WeirC Skew NumUp NumDn MinLoCord MaxHiCord MaxSubmerge Is_Ogee
22,28,2.6,0, 60, 60, , , 0.95, 0, 0,0,,
       0   37.08   86.67  129.17  178.76  214.18  277.94  313.36  334.61  362.94
  418.55  434.07  449.59  472.88  496.17  542.74  566.03  581.55  589.31  604.84
  628.91  652.44  683.81  691.66   713.4   713.5   786.5   786.6   809.3  862.41
   909.2  994.99 1033.98 1049.57 1088.57 1111.96 1135.36 1174.35 1197.74 1244.53
 1270.56  1309.2 1340.11 1378.75 1401.94 1409.66 1432.85 1440.57 1510.12 1541.04
 1595.13 1610.59 1626.04 1633.77  1641.5 1656.95 1703.32 1711.05 1734.23 1752.77
  129.46  128.86   124.6  121.35  118.27  114.84  110.68  107.95  106.84  104.89
  103.11  103.31  102.92  102.99  102.66  102.84  103.27  102.46  102.63  103.84
  103.89   105.9  106.99  106.46     108     111     111     108  106.93  105.55
  103.61  103.04  103.27  103.02  103.65  104.41  105.44     108  109.64  113.67
  115.61  117.82  120.42  124.18  124.71  125.57  129.23  130.02  132.05  132.37
  132.16  133.29  133.67  134.19  135.51  138.82  145.87  146.72  148.35  149.13
                                                                                
                                                                                
                                             104     104
                                                                                
                                                                                
                                                                                
     -40   16.67   59.17  108.76  144.18  207.94  243.36  264.61  292.94  348.55
  364.07  379.59  402.88  426.17  472.74  496.03  511.55  519.31  534.84  558.91
  582.44  643.49   643.5     716   716.1   739.3  792.41   839.2  909.39  924.99
  963.98  979.57 1018.57 1041.96 1065.36 1104.35 1127.74 1174.53 1200.56  1239.2
 1270.11  1293.3 1308.75 1324.21 1331.94 1339.66 1362.85 1370.57 1440.12 1471.04
 1525.13 1540.59 1556.04 1563.77  1571.5 1586.95 1633.32 1641.05 1664.23 1698.47
  129.46   124.6  121.35  118.27  114.84  110.68  107.95  106.84  104.89  103.11
  103.31  102.92  102.99  102.66  102.84  103.27  102.46  102.63  103.84  103.89
   105.9     108     111     111     108  106.93  105.55  103.61  103.32  103.04
  103.27  103.02  103.65  104.41  105.44     108  109.64  113.67  115.61  117.82
  120.42  122.86  124.18  124.34  124.71  125.57  129.23  130.02  132.05  132.37
  132.16  133.29  133.67  134.19  135.51  138.82  145.87  146.72  148.35  149.13
                                                                                
                                                                                
                     104     104
                                                                                
                                                                                
                                                                                
BR Coef=-1 , 0 , 0 ,, 0 ,,,0.8,0,,0,
WSPro=,,,, 1 ,,,, 0 ,,,, 0 ,,,,-1 ,-1 ,-1 , 0 , 0 , 0 , 0 , 0
BR U #Sta/Elev= 30
       0  130.05   113.3  120.88  141.63  116.65  346.99  104.52  377.35  106.73
  579.16  103.16  649.02   104.1  680.07   98.13  703.36   94.37  736.73    95.5
  745.75   90.79  763.79   89.82  772.94   90.09  780.67   94.03  800.19   98.26
  811.56  101.69  865.62  104.49  973.74  105.35 1213.16  115.14  1259.5   113.7
 1282.67  108.72 1305.84  115.39 1336.73  121.08 1383.07  124.46 1422.97  130.26
 1514.36  132.64 1614.77  131.45 1660.05 139.794 1707.44  147.86 1744.48  149.13
BR U #Mann= 5
       0      .1  680.07     .04  800.19      .1 1422.97     .06 1660.05      .1
BR D #Sta/Elev= 30
       0  138.59  100.04 129.212  124.03  125.81  277.25   120.5  408.58  120.63
  459.65  114.03  510.73  100.48  627.46   97.36  661.55   93.55  669.23   90.19
  677.02   89.91  708.17   90.58  715.96   94.82  731.54   97.27  770.48  103.87
  901.04 101.708     973   99.55 1082.05  101.51  1113.2  100.29 1156.82 105.501
 1180.77 107.263 1222.25  109.33 1253.41  118.33 1315.72  124.11 1370.24  125.63
 1518.23  135.82 1588.34  136.18 1642.86  145.85 1659.74 147.242 1698.47   149.8
BR D #Mann= 8
       0     .06  100.04      .1  627.46     .04  731.54      .1  901.04     .06
 1156.82      .1 1180.77     .06 1659.74      .1
BC Design=,, 0 ,, 0 ,,,,,,
BC Use User HTab Curves=0
BC User HTab FreeFlow(D)= 0

Type RM Length L Ch R = 1 ,38829.04,126.56,102.11,59.67
BEGIN DESCRIPTION:
Under water portion adjusted as per bridge inspection notes.
END DESCRIPTION:
XS GIS Cut Line= 3
 1632568.6173296725084.6530660841631956.43995592724904.729967028
1631003.46697307 724439.66712366
#Sta/Elev= 30
       0  138.59  100.04129.2115  124.03  125.81  277.25   120.5  408.58  120.63
  459.65  114.03  510.73  100.48  627.46   97.36  661.55   93.55  669.23   90.19
  677.02   89.91  708.17   90.58  715.96   94.82  731.54   97.27  770.48  103.87
  901.04101.7082     973   99.55 1082.05  101.51  1113.2  100.29 1156.82105.5013
 1180.77107.2625 1222.25  109.33 1253.41  118.33 1315.72  124.11 1370.24  125.63
 1518.23  135.82 1588.34  136.18 1642.86  145.85 1659.74147.2418 1698.47   149.8
#Mann= 8 ,-1 , 0
       0     .06       0  100.04      .1       0  627.46    .045       0
  731.54      .1       0  901.04     .06       0 1156.82      .1       0
 1180.77     .06       0 1659.74      .1       0
#XS Ineff= 2 , 0
       0   622.2  102.14  735.59       0  102.14
Permanent Ineff=
       F       F
Bank Sta=627.46,731.54
XS Rating Curve= 0 ,0
Exp/Cntr=0.5,0.3

Type RM Length L Ch R = 1 ,38726.93,727.5,730.43,731.27
XS GIS Cut Line= 4
1632634.44285366724742.3603410121631973.99342902724766.496366501
1631877.44932708724816.9626016171630974.03563851724390.614899337
#Sta/Elev= 30
       0  132.95  161.11  127.78  252.17  129.69  287.19  127.62  371.25  131.45
  546.36     129  644.43  123.13  660.89   117.7  686.38   98.21  687.71   97.63
  700.38      92  708.28   91.66  777.57   96.84  785.31   98.23  808.53  101.77
  854.97   96.18   946.398.20364 1025.26   97.74 1170.23102.1546 1237.62106.3719
 1249.73  107.42 1272.95  117.16 1288.43  120.08 1412.28  127.14 1466.46  133.08
 1567.09   137.6 1636.75  138.02 1683.19  146.98 1697.86148.1313 1768.79  151.52
#Mann= 7 ,-1 , 0
       0      .1       0  687.71    .045       0  777.57      .1       0
   946.3     .06       0 1170.23      .1       0 1237.62     .06       0
 1697.86      .1       0
Bank Sta=686.38,785.31
XS Rating Curve= 0 ,0
Exp/Cntr=0.3,0.1

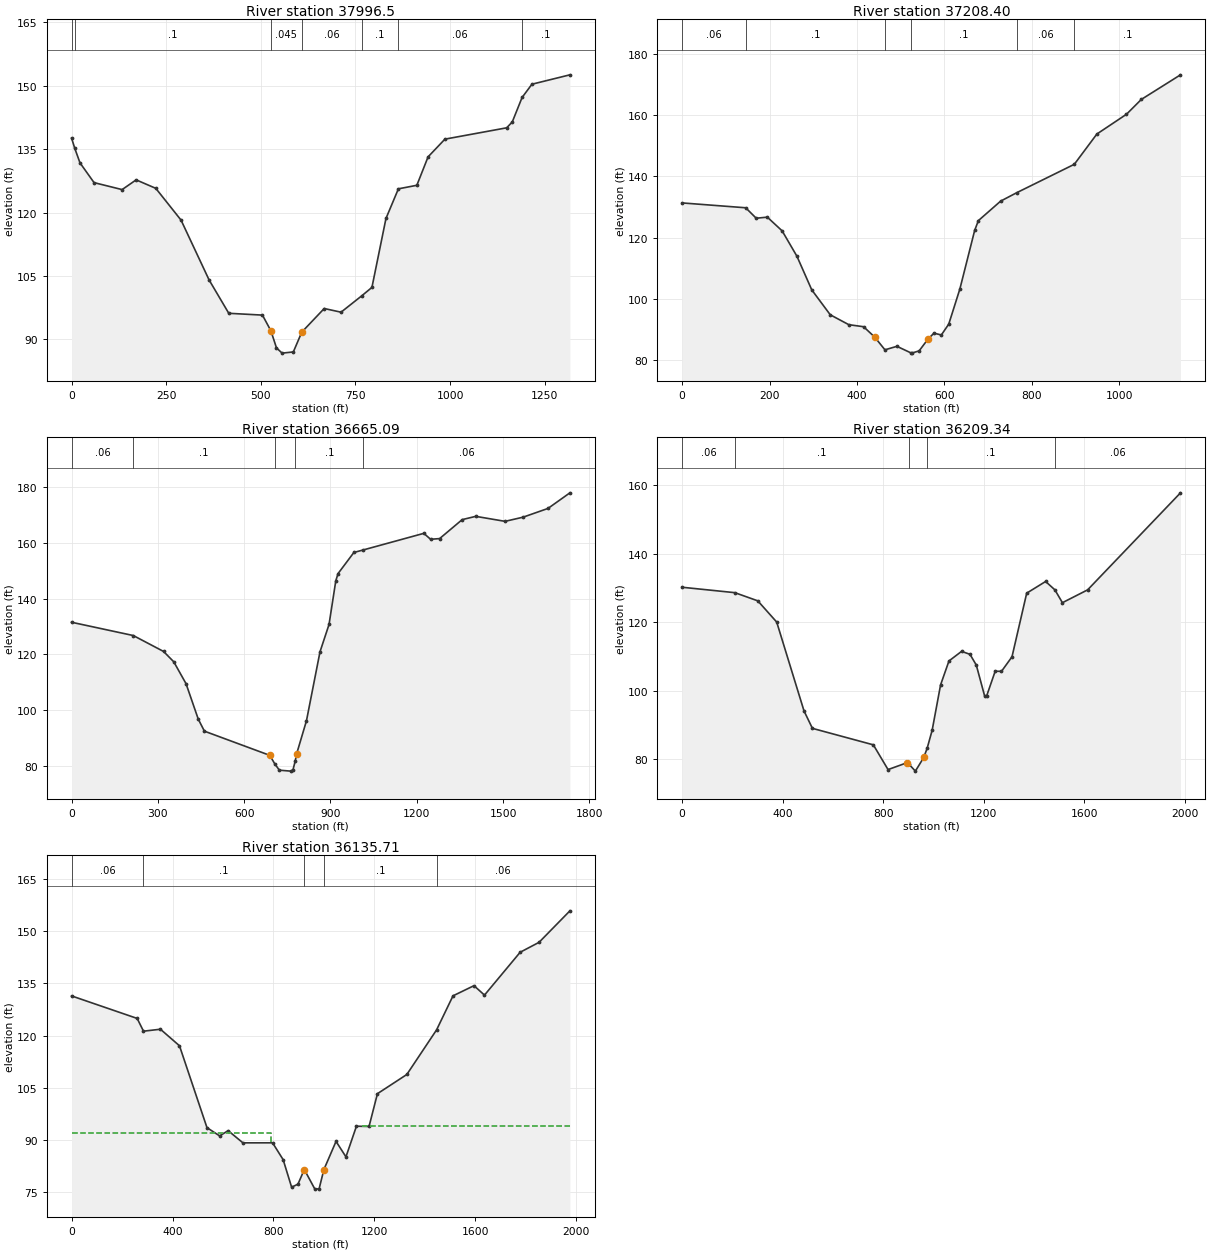
Type RM Length L Ch R = 1 ,37996.5 ,816.36,788.09,778.93
XS GIS Cut Line= 2
1632161.69902496723939.8889198151630918.96685232724375.401045397
#Sta/Elev= 30
       0  137.58    8.56135.1423   22.25  131.74   59.34  127.07  133.51  125.42
   170.6  127.72  222.52  125.72  289.28   118.2  363.45  104.04  415.37   96.17
  504.38   95.74  526.64   92.04  541.47   87.98   556.3   86.75  585.97   87.03
  608.25   91.71  667.57    97.3  712.07   96.43  766.66100.2963  793.66  102.29
  830.75  118.59  863.58125.6016  912.34  126.44  942.01  133.16  986.52  137.35
  1149.7  140.03 1164.53  141.42 1190.42147.2036 1216.45  150.34 1316.83  152.56
#Mann= 7 ,-1 , 0
       0     .06       0    8.56      .1       0  526.64    .045       0
  608.25     .06       0  766.66      .1       0  863.58     .06       0
 1190.42      .1       0
Bank Sta=526.64,608.25
XS Rating Curve= 0 ,0
Exp/Cntr=0.3,0.1

Type RM Length L Ch R = 1 ,37208.40,478.5,543.31,547.57
XS GIS Cut Line= 2
1631552.43422014723236.7606660131630610.34227321723879.891697377
#Sta/Elev= 30
       0  131.31  145.44 129.727  169.51  126.32  194.94  126.67  228.84   122.2
  262.74  113.91  296.65  102.95  339.02   94.82   381.4    91.6   415.3   90.93
  440.73   87.55  464.14    83.4  491.58   84.54  524.37   82.35  525.49   82.32
  542.44   83.06  562.86   86.93  576.34   88.82  593.29   88.25  610.24   91.79
  635.67  103.24  669.57  122.36  678.05  125.54   728.9  131.89  766.31134.6808
   897.6143.9066  949.27  153.78 1017.07  160.23 1050.97  165.06 1140.68  173.09
#Mann= 6 ,-1 , 0
       0     .06       0  145.44      .1       0  464.14    .045       0
  524.37      .1       0  766.31     .06       0   897.6      .1       0
Bank Sta=440.73,562.86
XS Rating Curve= 0 ,0
Exp/Cntr=0.3,0.1

Type RM Length L Ch R = 1 ,36665.09,367.57,455.75,492.73
XS GIS Cut Line= 3
1631559.01215494723177.2860958731630870.41281465 723057.52968888
 1629948.2884807723524.579676196
#Sta/Elev= 30
       0  131.55   214.5 126.791  319.73  121.09  355.25  117.38  397.88  109.55
  440.51   96.81  461.83   92.52  689.19   83.85  706.78   80.75  722.47   78.54
  761.71    78.2  769.55   78.58   777.4   81.76  782.66   84.46  816.63   96.25
  863.71  120.97   895.1  130.76  918.64  146.42  926.49     149  981.42  156.55
 1014.43157.4719 1224.66  163.41  1248.2  161.28 1279.59  161.53 1358.06  168.33
 1405.14   169.5 1507.14  167.71 1569.92  169.21 1656.23  172.33 1732.59  177.93
#Mann= 5 ,-1 , 0
       0     .06       0   214.5      .1       0  706.78    .045       0
   777.4      .1       0 1014.43     .06       0
Bank Sta=689.19,782.66
XS Rating Curve= 0 ,0
Exp/Cntr=0.3,0.1

Type RM Length L Ch R = 1 ,36209.34,80.81,73.64,77.41
XS GIS Cut Line= 2
1631496.32457571723155.7352710811629835.87678424722069.929371208
#Sta/Elev= 30
       0  130.17   209.7128.5928   301.1  126.21  376.37  120.03   485.1   94.14
  518.56   89.06  761.11   84.26  819.65   77.05  894.93   79.04  904.09   78.54
  928.38    76.6  961.84   80.58  975.51   83.29  995.29   88.52 1028.75  101.71
  1062.2   108.7 1112.39  111.49 1145.84  110.63 1170.93  107.51 1204.39   98.44
 1212.75   98.62 1246.21  105.71  1271.3  105.67 1313.12  109.91 1371.66  128.45
 1446.94  131.85 1483.99129.4067 1513.85  125.67 1614.21  129.41 1983.95  157.68
#Mann= 5 ,-1 , 0
       0     .06       0   209.7      .1       0  904.09    .045       0
  975.51      .1       0 1483.99     .06       0
Bank Sta=894.93,961.84
XS Rating Curve= 0 ,0
Exp/Cntr=0.5,0.3

Type RM Length L Ch R = 1 ,36135.71,274.05,263.15,262.12
XS GIS Cut Line= 3
1631553.44356793723111.0968644471630645.64523807722513.061138436
1629898.72824112722033.909848571
#Sta/Elev= 30
       0  131.38  259.86  124.92  284.92121.2589  352.06  121.82   427.5  117.07
  536.48   93.57  586.77    91.2   620.3   92.71  678.98   89.21  796.33   89.22
  838.24   84.39  871.77   76.49  896.92   77.35  922.07   81.56  963.98   75.93
  980.75   76.02  999.78   81.56 1047.81   89.63 1087.08   85.19 1128.66   93.99
 1178.56   93.91 1211.83  103.32 1328.26  108.83  1446.3121.6477 1511.22   131.4
 1594.39  134.32 1635.97  131.61 1777.35  143.91  1852.2  146.76 1974.48   155.8
#Mann= 5 ,-1 , 0
       0     .06       0  284.92      .1       0  922.07    .045       0
  999.78      .1       0  1446.3     .06       0
#XS Ineff= 2 , 0
       0  789.19      92 1149.55       0      94
Permanent Ineff=
       F       F
Bank Sta=922.07,999.78
XS Rating Curve= 0 ,0
Exp/Cntr=0.5,0.3