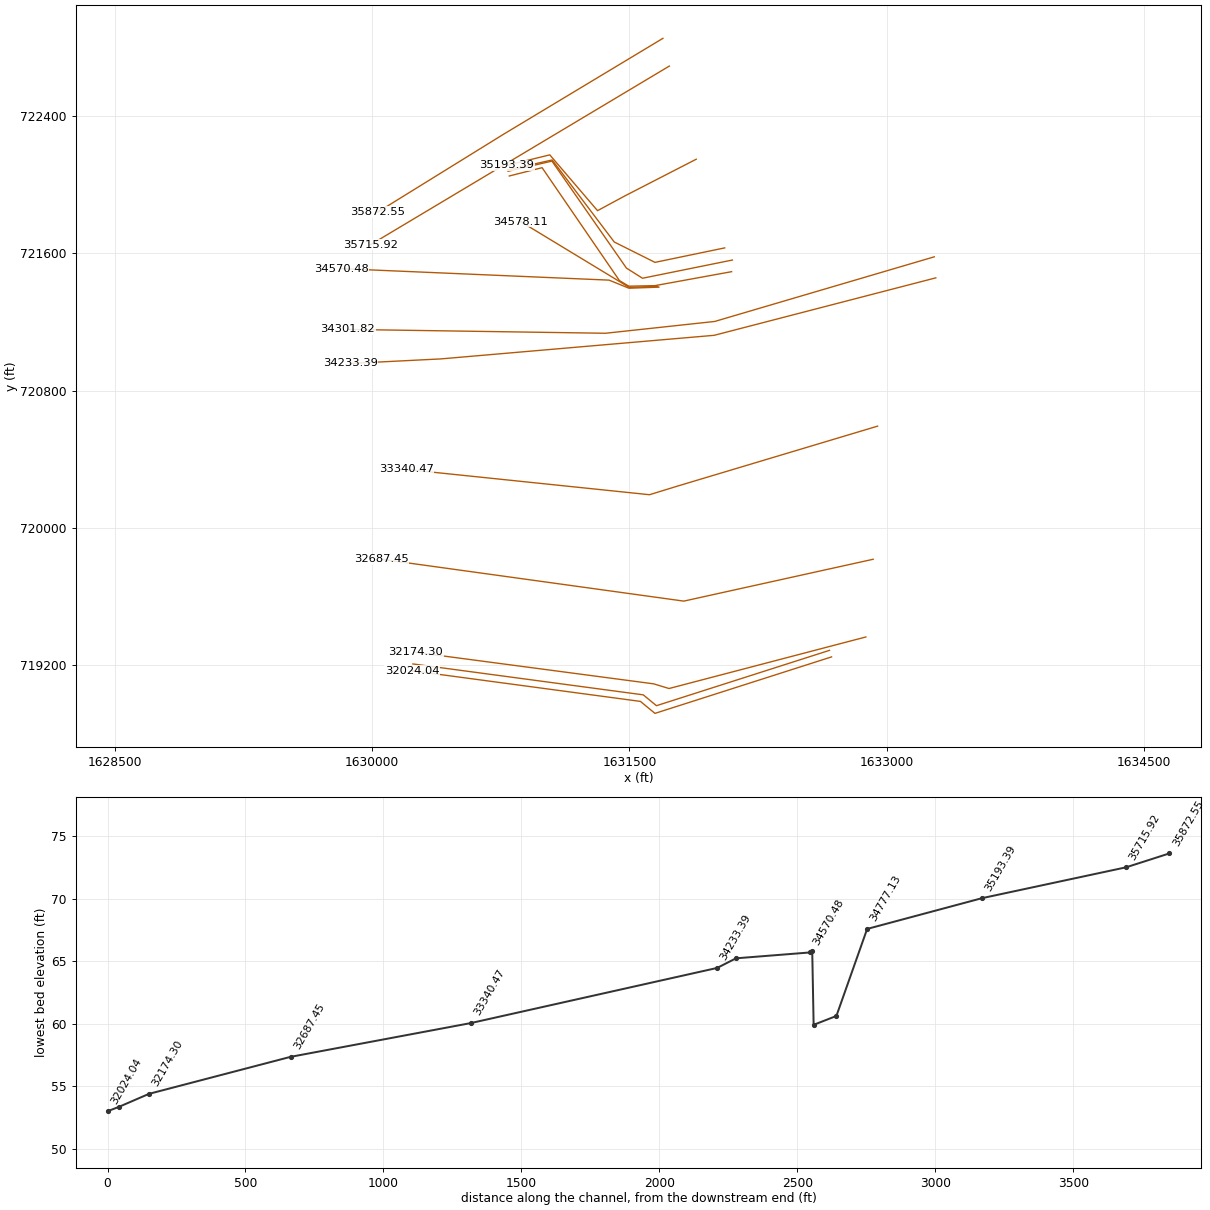
HEC-RAS study LittleElkCreek.prj: Little Elk Creek

--- LittleElkCreek.g01 (geometry) --- (continued)

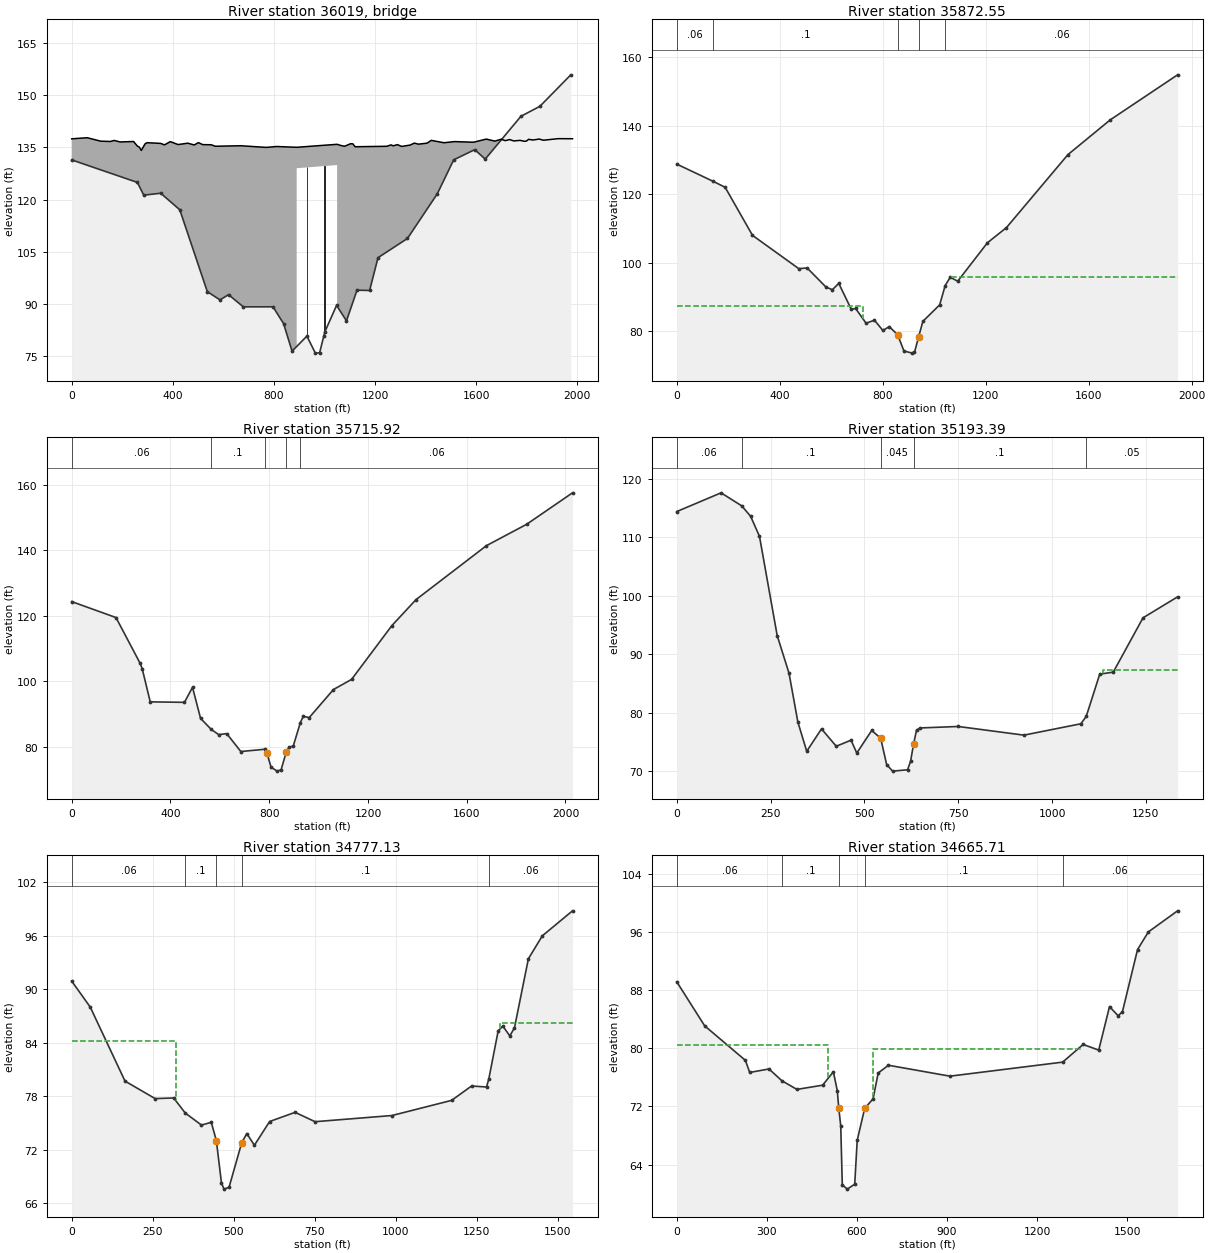
Type RM Length L Ch R = 3 ,36019   ,,,
BEGIN DESCRIPTION:
Chessie System RR.  CE050307FS-5. No survey data available for bridge geometry.  Dimensions scaled from pictures.  Top of RR bridge abutments taken from LIDAR.
END DESCRIPTION:
Bridge Culvert--1,0,-1,-1, 0
Deck Dist Width WeirC Skew NumUp NumDn MinLoCord MaxHiCord MaxSubmerge Is_Ogee
100,20,2.6,0, 60, 60, , , 0.95, 0, 0,0,,
       0   61.18  114.71  152.95  168.25  191.19  244.72  260.02  267.67  275.32
  290.61  298.26  351.79  367.09  390.03  420.62  459.56  484.68  501.43  518.17
  551.66  568.41  668.89  769.36  811.23     890    1050 1062.41 1079.16 1104.28
 1112.65 1121.02 1246.62 1263.36 1271.74 1288.48 1305.23 1338.72 1355.47 1372.21
  1405.7 1422.45 1472.69 1514.55 1589.91 1640.14 1673.64 1698.76  1715.5 1732.25
 1748.99 1774.11 1790.86 1799.23  1807.6 1824.35 1849.47 1866.21 1924.82 1981.24
  137.43  137.75  136.76  136.67  136.97  136.54  136.66  135.33  135.05   134.1
  136.03  136.32  136.12   135.7  136.63  135.79  136.18  135.67  136.35  135.77
  135.73   135.3  135.45  134.97  135.23     135  135.86  135.57  135.29  136.05
  135.97  135.16  135.29  135.69  135.42  135.77  135.25  135.64   136.2   135.9
  136.19  136.99  136.31  136.64  136.46  137.36  136.78  137.31  136.91  137.22
  136.83  136.99  136.72   136.8  137.29  137.09  137.36  137.03  137.48  137.46
                                                                                
                                                                                
                                             129   129.9
                                                                                
                                                                                
                                                                                
       0   61.18  114.71  152.95  168.25  191.19  244.72  260.02  267.67  275.32
  290.61  298.26  351.79  367.09  390.03  420.62  459.56  484.68  501.43  518.17
  551.66  568.41  668.89  769.36  811.23     825     985 1054.04 1079.16  1095.9
 1112.65 1121.02 1246.62 1263.36 1271.74 1288.48 1305.23 1338.72 1355.47 1372.21
  1405.7 1422.45 1472.69 1514.55 1589.91 1640.14 1673.64 1698.76  1715.5 1732.25
 1748.99 1774.11 1790.86 1799.23  1807.6 1824.35 1849.47 1866.21 1924.82 1981.24
  137.43  137.75  136.76  136.67  136.97  136.54  136.66  135.33  135.05   134.1
  136.03  136.32  136.12   135.7  136.63  135.79  136.18  135.67  136.35  135.77
  135.73   135.3  135.45  134.97  135.23     135   135.5  135.86  135.29  135.93
  135.97  135.16  135.29  135.69  135.42  135.77  135.25  135.64   136.2   135.9
  136.19  136.99  136.31  136.64  136.46  137.36  136.78  137.31  136.91  137.22
  136.83  136.99  136.72   136.8  137.29  137.09  137.36  137.03  137.48  137.46
                                                                                
                                                                                
                                             129   129.5
                                                                                
                                                                                
                                                                                
Pier Skew, UpSta & Num, DnSta & Num=  ,930, 2 ,870, 2 , 0 , 0 , 0 ,,
       2       2
       0     130
       2       2
       0     130
Pier Skew, UpSta & Num, DnSta & Num=  ,1000, 2 ,940, 2 , 0 , 0 , 0 ,,
       2       2
       0     130
       2       2
       0     130
BR Coef=-1 , 1 , 0 ,, 0 ,,,0.8,-1,0.5,0,
WSPro=,,,, 1 ,,,, 0 ,,,, 0 ,,,,-1 ,-1 ,-1 , 0 , 0 , 0 , 0 , 0
BR U #Sta/Elev= 30
       0  131.38  259.86  124.92  284.92 121.259  352.06  121.82   427.5  117.07
  536.48   93.57  586.77    91.2   620.3   92.71  678.98   89.21  796.33   89.22
  838.24   84.39  871.77   76.49  930.45   80.81  963.98   75.93  980.75   76.02
  997.51   80.87 1001.26   81.99 1047.81   89.63 1087.08   85.19 1128.66   93.99
 1178.56   93.91 1211.83  103.32 1328.26  108.83  1446.3 121.648 1511.22   131.4
 1594.39  134.32 1635.97  131.61 1777.35  143.91  1852.2  146.76 1974.48   155.8
BR U #Mann= 5
       0     .06  284.92      .1  930.45     .04 1001.26      .1  1446.3     .06
BR U Banks=930.45,997.51
BR D #Sta/Elev= 30
       0  128.84  140.83 123.825   187.9  122.07  294.11  108.03  473.84   98.31
  506.52    98.5  580.04   92.89  604.55   92.16  629.06   94.01  678.08   86.39
  694.42   86.69  735.27   82.37  767.94   83.25  800.62   80.24  825.13   81.37
  857.81   79.01  882.32   74.25     915   73.63  923.17   73.83  939.51   78.42
  955.85   82.91  1021.2   87.74 1042.38  93.354 1062.05   95.79 1091.21   94.64
 1206.44  105.85 1280.52   110.3 1519.23  131.61 1683.85  141.78 1945.11  154.92
BR D #Mann= 5
       0     .06  140.83      .1  857.81     .04  939.51      .1 1042.38     .06
BC Design=,, 0 ,, 0 ,,,,,,
BC Use User HTab Curves=0
BC User HTab FreeFlow(D)= 0

Type RM Length L Ch R = 1 ,35872.55,167.34,156.63,155.54
XS GIS Cut Line= 3
1631695.55973871722852.7038266961630767.63201384722294.326230124
1630034.45397863721840.761683688
#Sta/Elev= 30
       0  128.84  140.83123.8249   187.9  122.07  294.11  108.03  473.84   98.31
  506.52    98.5  580.04   92.89  604.55   92.16  629.06   94.01  678.08   86.39
  694.42   86.69  735.27   82.37  767.94   83.25  800.62   80.24  825.13   81.37
  857.81   79.01  882.32   74.25     915   73.63  923.17   73.83  939.51   78.42
  955.85   82.91  1021.2   87.74 1042.3893.35364 1062.05   95.79 1091.21   94.64
 1206.44  105.85 1280.52   110.3 1519.23  131.61 1683.85  141.78 1945.11  154.92
#Mann= 5 ,-1 , 0
       0     .06       0  140.83      .1       0  857.81    .045       0
  939.51      .1       0 1042.38     .06       0
#XS Ineff= 2 , 0
       0  724.32   87.33 1063.79       0   95.87
Permanent Ineff=
       F       F
Bank Sta=857.81,939.51
XS Rating Curve= 0 ,0
Exp/Cntr=0.5,0.3

Type RM Length L Ch R = 1 ,35715.92,539.34,522.54,86.79
XS GIS Cut Line= 2
1631732.85514002722691.0820096281629991.73017861721650.192087039
#Sta/Elev= 30
       0  124.33  179.42  119.45  277.29  105.45  285.44  103.85  318.07   93.69
  456.71   93.54  489.33   98.13  521.95   88.64  565.5685.24434  595.35   83.68
  627.97   83.98  685.06   78.51  782.93   79.21  791.09   77.94   807.4   73.75
  831.86   72.52  848.17   72.93  868.77   78.28   880.8    79.9  897.11   80.11
  926.2387.36362  937.88   89.25  962.35    88.9 1060.22   97.46 1133.62  100.55
 1296.73  116.98 1394.59  124.93 1680.04  141.43 1843.15  147.97 2028.54  157.57
#Mann= 5 ,-1 , 0
       0     .06       0  565.56      .1       0  782.93    .045       0
  868.77      .1       0  926.23     .06       0
Bank Sta=791.09,868.77
XS Rating Curve= 0 ,0
Exp/Cntr=0.3,0.1

Type RM Length L Ch R = 1 ,35193.39,453.55,416.26,695.3
XS GIS Cut Line= 5
1631889.65819623722148.2902718481631470.10758476721932.572343305
1631314.46928465721848.4435324371631036.24676773722173.656118393
1630785.80741693722112.210032329
#Sta/Elev= 30
       0  114.41  118.07  117.61  173.16  115.38  196.78   113.6  220.39  110.18
  267.62   93.21   299.1   86.79  322.71   78.43  346.33   73.44  385.68   77.27
  425.04    74.3  464.39   75.34  479.72   73.14   519.5      77  543.37   75.67
  559.29   71.17   575.2   70.05  614.99   70.28  622.95   71.71   630.9   74.62
  638.86   77.04  648.68   77.43  750.01   77.68  925.04    76.2 1076.67   78.14
 1091.08   79.39 1127.12   86.62 1163.16   86.97 1242.44   96.25 1334.53   99.83
#Mann= 5 ,-1 , 0
       0     .06       0  173.16      .1       0  543.37    .045       0
   630.9      .1       0 1091.08     .05       0
#XS Ineff= 2 , 0
                         1134.79           87.28
Permanent Ineff=
       F       F
Bank Sta=543.37,630.9
XS Rating Curve= 0 ,0
Exp/Cntr=0.3,0.1

Type RM Length L Ch R = 1 ,34777.13,119.94,111.42,108.07
XS GIS Cut Line= 5
 1632055.6279663721631.5643017441631649.36746092721547.187119856
1631411.86131933721665.9401906581631050.21178733722143.864076659
1630791.39342479722086.141995803
#Sta/Elev= 30
       0   90.91    57.2      88  164.44    79.7  257.38   77.74  314.57   77.81
  350.32   76.12  400.37   74.77  430.58   75.08  446.24   73.03  461.89   68.31
  469.71   67.59  485.37   67.79   524.5   72.79  540.15   73.82  563.63   72.51
  610.59   75.17  689.25    76.2   750.7   75.15  987.71   75.84 1172.05   77.54
  1233.5   79.15 1279.81   79.04 1286.98   79.98 1315.67   85.33 1330.01   85.87
 1351.53   84.77 1365.87   85.66  1408.9   93.42 1451.93   95.99 1544.98   98.79
#Mann= 5 ,-1 , 0
       0     .06       0  350.32      .1       0  446.24    .045       0
   524.5      .1       0 1286.98     .06       0
#XS Ineff= 2 , 0
          321.47   84.24 1322.62           86.26
Permanent Ineff=
       F       F
Bank Sta=446.24,524.5
XS Rating Curve= 0 ,0
Exp/Cntr=0.5,0.3

Type RM Length L Ch R = 1 ,34665.71,81.63,82.56,99.03
BEGIN DESCRIPTION:
Channel invert adjusted -6' as per bridge inspection notes
END DESCRIPTION:
XS GIS Cut Line= 5
1632100.35874271721560.7977694121631576.45238829721454.686646342
1631482.98432145 721513.719109641631048.84974754 722137.24950324
1630793.04240659722078.217039943
#Sta/Elev= 30
       0   89.13   92.85   83.08  228.55   78.33  242.83   76.67  307.11   77.15
  349.96   75.53  399.96   74.34  485.66   74.92  521.38   76.76  534.54   74.15
   539.3   71.77  545.91   69.34   551.1   61.23  567.66   60.63   592.5   61.31
  600.78   67.35  625.62   71.72  653.62   73.05  670.68    76.6   704.8   77.66
  909.51   76.16 1284.81   78.09 1353.05   80.52 1404.87   79.74 1440.79   85.72
 1469.53   84.46 1483.89   85.03 1534.18   93.57  1570.1   95.99  1667.4   98.89
#Mann= 5 ,-1 , 0
       0     .06       0  349.96      .1       0   539.3    .045       0
  625.62      .1       0 1284.81     .06       0
#XS Ineff= 3 ,-1
       0     504   80.44     654    1353    79.9 1353.05    1415   80.52
Permanent Ineff=
       F       F       F
Bank Sta=539.3,625.62
XS Rating Curve= 0 ,0
Exp/Cntr=0.5,0.3

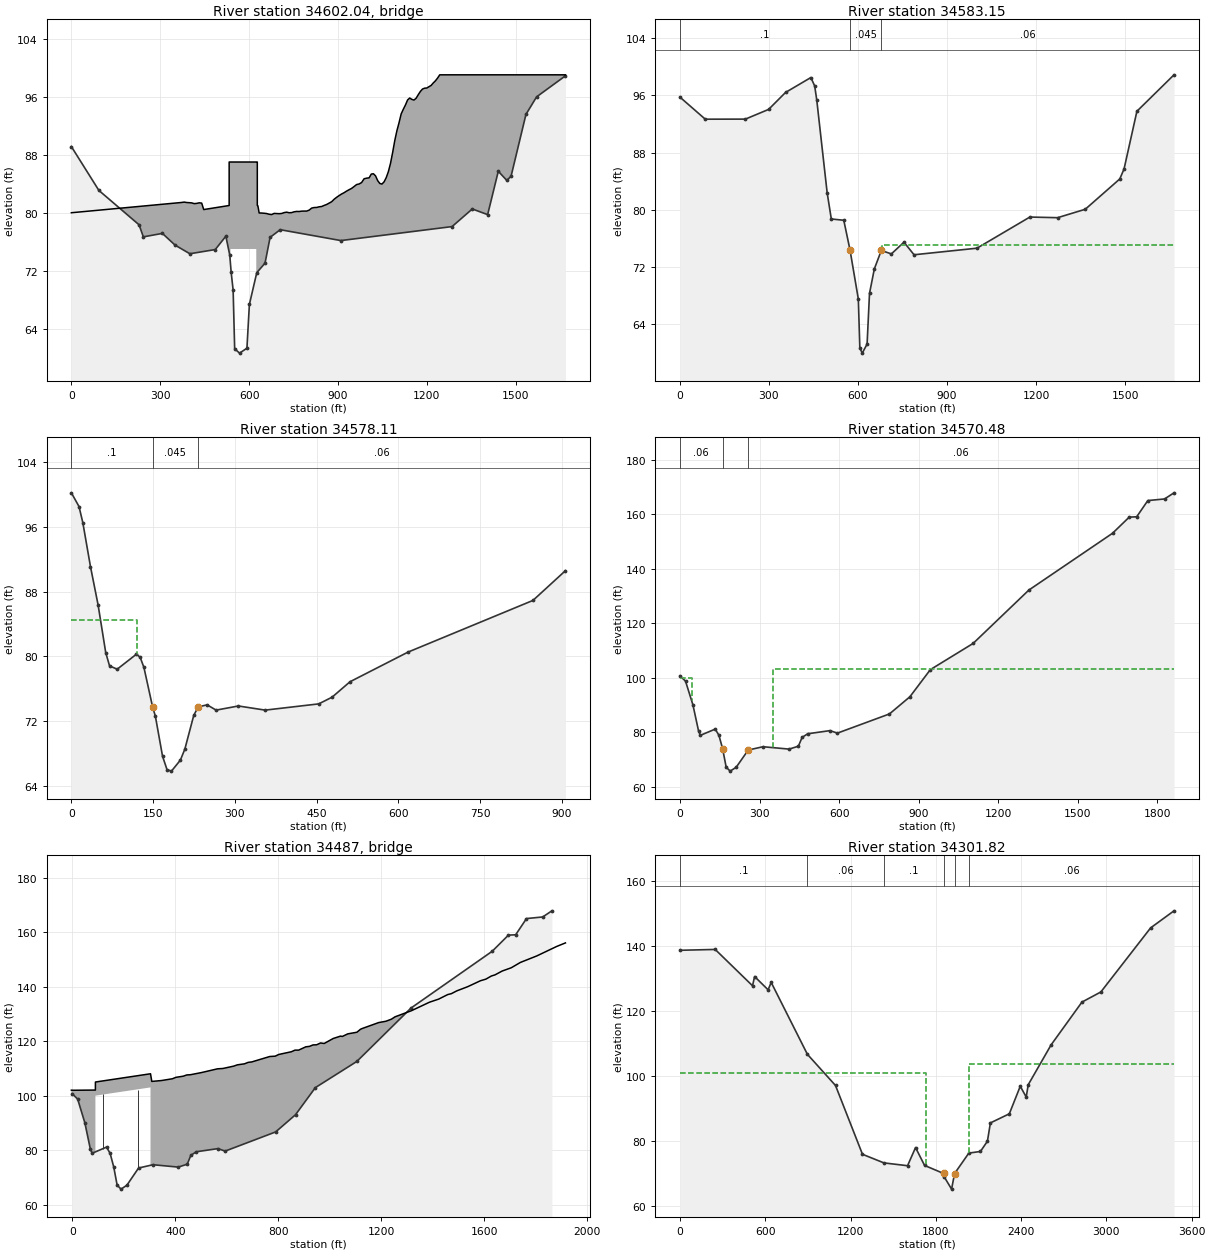
Type RM Length L Ch R = 3 ,34602.04,,,
BEGIN DESCRIPTION:
Blue Ball Rd.  CE050307FS-3. Located 80 feet upstream of I95 Bridge.  This bridge crosses under I95 bridge within the left overbank area.
END DESCRIPTION:
Bridge Culvert--1,0,-1,-1, 0
Deck Dist Width WeirC Skew NumUp NumDn MinLoCord MaxHiCord MaxSubmerge Is_Ogee
25,30,2.6,0, 97, 144, , , 0.95, 0, 0,0,,
       0  372.34  380.77  389.21  397.64  406.07   414.5  422.94  431.37   439.8
  446.67  532.49   532.5     537     624   627.5  627.51  629.49  633.76  642.19
  650.62  659.05  667.49  675.92  684.35  692.79  701.22  709.65  718.08  726.52
  734.95  743.38  751.82  760.25  768.68  777.11  785.55  793.98  802.41  810.85
  819.28  827.71  836.14  844.58  853.01  861.44  869.87  878.31  886.74  895.17
  903.61  912.04  920.47   928.9  937.34  945.77   954.2  962.64  971.07   979.5
  987.93  996.37 1004.96 1012.16 1019.37 1026.57 1033.78 1040.98 1048.19 1055.39
 1062.59  1069.8    1077 1084.21 1091.41 1098.62 1105.82 1113.02 1120.23 1127.43
 1134.64 1141.84 1149.05 1156.25 1163.45 1170.66 1177.86 1185.07 1192.27 1199.48
 1206.68 1213.89 1221.09 1228.29  1235.5 1243.12  1667.4
      80   81.42   81.47   81.41   81.39   81.36   81.26   81.29   81.37   81.33
   80.44      81      87      87      87      87      81   80.95   79.97   79.96
   79.93   79.89   79.79   79.75   79.91   79.89   79.87    79.9   80.02   80.08
      80   80.02   80.13   80.18   80.17   80.22   80.23   80.23   80.36   80.64
   80.72   80.73   80.82   80.86   81.01   81.14   81.33   81.52   81.86   82.13
   82.37   82.59   82.77   82.99   83.18   83.36   83.62   83.89   83.97   84.17
   84.69   84.77   84.82   85.34   85.38   85.09   84.43   84.04   83.96   84.27
   84.85   85.67   86.81   88.31   89.96   91.32   92.42   93.64   94.28   94.87
   95.56   95.83   95.64   95.55    95.8   96.29   96.74   97.07   97.19   97.21
   97.39   97.56    97.9   98.19   98.56   99.03   99.03
                                                                                
                              75      75
                                                                                
                                                                                
                                                                                
                                                                                
                                                                                
                                                                                
                                                                                
                                                        
       0       7   14.01   21.01   28.01   35.02   42.02   49.02   56.03   63.03
   70.03   77.04   84.04   91.04   98.05  105.05  112.05  119.06  126.06  133.06
  140.07  147.07  154.07  161.18  170.32  179.45  188.58  197.71  206.85  215.98
  220.55  228.98  237.41  245.85  254.28  262.71  271.15  279.58  288.01  296.44
  304.88  313.31  321.74  330.18  338.61  347.04  355.47  363.91  372.34  380.77
  389.21  397.64  406.07   414.5  422.94  431.37   439.8  448.23  456.67   465.1
  473.53  480.17  565.99     566   570.5   657.5     661  661.01  662.99  667.49
  675.92  684.35  692.79  701.22  709.65  718.08  726.52  734.95  743.38  751.82
  760.25  768.68  777.11  785.55  793.98  802.41  810.85  819.28  827.71  836.14
  844.58  853.01  861.44  869.87  878.31  886.74  895.17  903.61  912.04  920.47
   928.9  937.34  945.77   954.2  962.64  971.07   979.5  987.93  996.37 1004.96
 1012.16 1019.37 1026.57 1033.78 1040.98 1048.19 1055.39 1062.59  1069.8    1077
 1084.21 1091.41 1098.62 1105.82 1113.02 1120.23 1127.43 1134.64 1141.84 1149.05
 1156.25 1163.45 1170.66 1177.86 1185.07 1192.27 1199.48 1206.68 1213.89 1221.09
 1228.29  1235.5 1243.12 1664.73
   91.78   90.93   89.84   88.75   88.22   87.62   86.34   84.27   81.33   79.12
   78.05    77.7   77.69   77.68   76.68   74.22   71.55   68.64   66.63   66.23
   66.34   66.44   66.29   66.18   66.65   67.25   67.71   70.59   76.23   80.57
   81.24   81.78   82.11   82.07   82.08   81.95   81.93   81.85   81.72   81.58
   81.51   81.57    81.5   81.55   81.57   81.43   81.24   81.32   81.42   81.47
   81.41   81.39   81.36   81.26   81.29   81.37   81.33   81.22   81.19   81.18
   81.02   80.44      81      87      87      87      87      81   80.95   79.79
   79.75   79.91   79.89   79.87    79.9   80.02   80.08      80   80.02   80.13
   80.18   80.17   80.22   80.23   80.23   80.36   80.64   80.72   80.73   80.82
   80.86   81.01   81.14   81.33   81.52   81.86   82.13   82.37   82.59   82.77
   82.99   83.18   83.36   83.62   83.89   83.97   84.17   84.69   84.77   84.82
   85.34   85.38   85.09   84.43   84.04   83.96   84.27   84.85   85.67   86.81
   88.31   89.96   91.32   92.42   93.64   94.28   94.87   95.56   95.83   95.64
   95.55    95.8   96.29   96.74   97.07   97.19   97.21   97.39   97.56    97.9
   98.19   98.56   99.03   99.03
                                                                                
                                                                                
                                                                                
                                                                                
                                                                                
                                                                                
                                      75      75
                                                                                
                                                                                
                                                                                
                                                                                
                                                                                
                                                                                
                                                                                
                                
BR Coef=-1 , 0 , 0 ,, 0 ,,,0.8,0,,0,
WSPro=,,,, 1 ,,,, 0 ,,,, 0 ,,,,-1 ,-1 ,-1 , 0 , 0 , 0 , 0 , 0
BR U #Sta/Elev= 30
       0   89.13   92.85   83.08  228.55   78.33  242.83   76.67  307.11   77.15
  349.96   75.53  399.96   74.34  485.66   74.92  521.38   76.76  534.54   74.15
   539.3   71.77  545.91   69.34   551.1   61.23  567.66   60.63   592.5   61.31
  600.78   67.35  625.62   71.72  653.62   73.05  670.68    76.6   704.8   77.66
  909.51   76.16 1284.81   78.09 1353.05   80.52 1404.87   79.74 1440.79   85.72
 1469.53   84.46 1483.89   85.03 1534.18   93.57  1570.1   95.99  1667.4   98.89
BR U #Mann= 5
       0     .06  349.96      .1   539.3     .04  625.62      .1 1284.81     .06
BR D #Sta/Elev= 30
       0   95.76   85.38   92.67  220.57   92.68  298.84   94.04  355.76   96.41
  441.15    98.5  454.06   97.32  461.06   95.35  496.07   82.37  510.07    78.7
  552.08   78.52  573.09   74.36  601.09    67.5  606.24   60.62  614.38   59.92
  630.65   61.19  638.79   68.28  655.06   71.71  678.52   74.29  712.46   73.81
  754.89   75.45  788.83   73.69 1000.94   74.61 1179.12   78.97 1272.46   78.88
 1365.79   80.06 1482.01    84.3 1496.45    85.7 1539.78   93.78 1664.73   98.88
BR D #Mann= 3
       0      .1  573.09     .04  678.52     .06
BC Design=,, 0 ,, 0 ,,,,,,
BC Use User HTab Curves=0
BC User HTab FreeFlow(D)= 0

Type RM Length L Ch R = 1 ,34583.15,10.48,5.04,4.53
BEGIN DESCRIPTION:
Channel invert adjusted -6' as per bridge inspection notes
END DESCRIPTION:
XS GIS Cut Line= 6
1632095.82319088721492.966435641 1631649.1171966721411.574368224
1631496.96610124721408.4750083981631442.07801203 721440.99023518
1630991.37932213722098.9611504081630800.24844244722050.588520363
#Sta/Elev= 30
       0   95.76   85.38   92.67  220.57   92.68  298.84   94.04  355.76   96.41
  441.15    98.5  454.06   97.32  461.06   95.35  496.07   82.37  510.07    78.7
  552.08   78.52  573.09   74.36  601.09    67.5  606.24   60.62  614.38   59.92
  630.65   61.19  638.79   68.28  655.06   71.71  678.52   74.29  712.46   73.81
  754.89   75.45  788.83   73.69 1000.94   74.61 1179.12   78.97 1272.46   78.88
 1365.79   80.06 1482.01    84.3 1496.45    85.7 1539.78   93.78 1664.73   98.88
#Mann= 3 , 0 , 0
       0      .1       0  573.09    .045       0  678.52     .06       0
#XS Ineff= 2 , 0
       0     543      75     680       0      75
Permanent Ineff=
       F       F
Bank Sta=573.09,678.52
XS Rating Curve= 0 ,0
Exp/Cntr=0.5,0.3

Type RM Length L Ch R = 1 ,34578.11,5.22,7.63,14.09
XS GIS Cut Line= 3
1631665.83288671721407.2456011771631498.71176521721401.511052862
1630866.77222404721784.605759203
#Sta/Elev= 30
       0  100.19   14.01    98.5   21.01   96.51   35.02   91.09   49.03   86.35
   63.04   80.46   70.04   78.83   84.05   78.42  119.07   80.26  126.07   79.91
  133.08   78.64  149.03   73.75  154.09   72.62  167.22   67.68  175.41   66.03
  183.59   65.84  199.96    67.2  208.15   68.56  224.52   72.73  232.71   73.77
  249.08   74.02  265.45   73.37  306.38   73.88  355.49   73.37  453.72   74.14
  478.28   74.97  511.02   76.87  617.44   80.53  846.64   86.91  906.21   90.58
#Mann= 3 , 0 , 0
       0      .1       0  149.03    .045       0  232.71     .06       0
#XS Ineff= 2 , 0
          120.55   84.48
Permanent Ineff=
       F       F
Bank Sta=149.03,232.71
XS Rating Curve= 0 ,0
Exp/Cntr=0.5,0.3

Type RM Length L Ch R = 1 ,34570.48,249.52,268.66,285.3
XS GIS Cut Line= 4
1631671.83462888721402.7628680911631497.56271091721396.542815074
1631381.82043578721443.6749786591629820.26093289721510.645386681
#Sta/Elev= 30
       0  100.68   21.01   98.74   49.03      90   70.04   80.52   77.05   78.84
  133.08   81.13  147.09   78.83   161.1   73.85  174.38   67.15   189.5   65.71
  212.17   67.14  257.52   73.45  313.37   74.66  411.46   73.79  446.49   74.85
   460.5   78.08  481.52   79.41   565.6   80.57  593.62   79.65   789.8   86.69
  866.87   92.99  943.94  102.94 1105.09  112.55 1315.29  132.13 1630.58  152.96
 1693.64  158.89 1721.66  159.01  1763.7  164.96 1826.76  165.55 1862.35   167.8
#Mann= 3 , 0 , 0
       0     .06       0   161.1    .045       0  257.52     .06       0
#XS Ineff= 2 , 0
       0      45     100     350       0     103
Permanent Ineff=
       F       F
Bank Sta=161.1,257.52
XS Rating Curve= 0 ,0
Exp/Cntr=0.5,0.3

Type RM Length L Ch R = 3 ,34487   ,,,
BEGIN DESCRIPTION:
I95 Bridge, Bridge CE050307FS-4. Top of Road from LIDAR.  No survey data available.  Geometry from assumed dimensions from pictures.
END DESCRIPTION:
Bridge Culvert--1,0,-1,-1, 0
Deck Dist Width WeirC Skew NumUp NumDn MinLoCord MaxHiCord MaxSubmerge Is_Ogee
50,150,2.6,0, 60, 60, , , 0.95, 0, 0,0,,
   -3.37    3.76    89.9      90     304  308.89  346.89   388.9   402.9   430.9
   444.9   458.9   500.9   563.9   584.9   626.9   640.9   668.9   682.9   696.9
   766.9   787.9   801.9   850.9   864.9   878.9   906.9   920.9   934.9   948.9
  964.07  978.18 1013.45 1041.67 1048.72 1069.89 1105.16 1119.27 1126.32 1189.81
 1218.02 1239.19 1253.29 1316.78 1387.32  1422.6 1457.87 1471.98 1493.14 1535.46
 1584.84    1606 1627.17 1641.28 1669.49 1704.76 1740.03 1803.52 1881.12 1914.94
  102.01  101.98  102.05     105  108.03  105.22  105.55   106.2  106.73  107.14
   107.6  107.68  108.45  109.84  109.97  110.83   111.3  111.68  112.21  112.37
  114.36  114.48  115.11  116.11   116.7   116.7  117.92  118.07  118.61  118.66
  119.33  119.14  120.98  121.84  121.72  122.67  123.26  124.36  124.65  126.81
   127.3  128.05  128.92  131.15  134.29  135.41  137.08  137.41  138.44  139.97
  142.15  142.74  143.88   144.3  145.72  146.92  148.87  151.25  154.74  156.03
                             100  103.03
                                                                                
                                                                                
                                                                                
                                                                                
                                                                                
       0   51.72   88.66   96.05  118.21  155.15  177.32  206.87  325.08  428.52
   443.3  546.73  561.51  605.84  657.56   694.5  738.83  753.61  797.94  990.03
 1061.74 1125.93 1240.04 1297.09 1425.46 1475.39 1525.31 1582.36 1646.55  1773.9
    1774    1988  1988.9  2044.9  2268.9  2366.9  2387.9  2464.9  2478.9  2506.9
  2548.9 2564.07 2578.18  2606.4 2634.61 2648.72 2669.89 2705.16 2726.32 2789.81
 2832.13 2853.29 2916.78 2987.32  3022.6    3206 3269.49 3304.76 3340.03 3514.94
   119.2  118.42  117.18  117.52   116.8   116.5   115.7  115.48  112.93  111.57
  110.96  109.01  108.33  108.06  106.94  106.63  105.72  105.85  104.97  103.13
  102.98  102.18   101.5  101.84  101.42  101.89  101.61  102.12  102.05  103.01
     106  108.87   106.2   107.6  111.68  114.36  114.48   116.7   116.7  117.92
  118.66  119.33  119.14  120.73  121.68  121.72  122.67  123.26  124.65  126.81
  127.78  128.92  131.15  134.29  135.41  142.74  145.72  146.92  148.87  156.03
                                                                                
                                                                                
                                                                                
     101  103.87
                                                                                
                                                                                
Pier Skew, UpSta & Num, DnSta & Num=  ,120, 2 ,1816, 2 , 0 , 0 , 0 ,,
       2       2
       0     102
       2       2
       0     102
Pier Skew, UpSta & Num, DnSta & Num=  ,255, 2 ,1951, 2 , 0 , 0 , 0 ,,
       2       2
       0     102
       2       2
       0     102
BR Coef=-1 , 1 , 0 ,, 0 ,,,0.8,-1,0.5,0,
WSPro=,,,, 1 ,,,, 0 ,,,, 0 ,,,,-1 ,-1 ,-1 , 0 , 0 , 0 , 0 , 0
BC Design=,, 0 ,, 0 ,,,,,,
BC Use User HTab Curves=0
BC User HTab FreeFlow(D)= 0

Type RM Length L Ch R = 1 ,34301.82,70.79,68.43,67.73
XS GIS Cut Line= 4
1633276.69126165721579.489508882 1631997.2213392721202.823129848
1631360.47579367721134.0665685981629859.04085627 721156.48406288
#Sta/Elev= 30
       0   138.6   248.1  138.86  510.79   127.7  525.39  130.54  620.25  126.46
  642.14  128.72  896.76  106.65 1094.56   97.07 1284.28   75.94 1435.1673.29598
 1601.31   72.43 1657.63   78.01    1721   72.52 1854.77   70.05 1858.86   69.04
  1911.1   65.24 1932.22   70.03 2032.65 76.3119 2114.22   76.81 2163.23   79.96
 2184.23   85.58 2317.24   88.37 2394.25   96.84 2436.25   93.52 2450.26    97.3
 2611.27  109.55 2828.29  122.69 2961.31   125.8 3311.35  145.48  3475.8  150.72
#Mann= 6 ,-1 , 0
       0      .1       0  896.76     .06       0 1435.16      .1       0
 1858.86    .045       0 1932.22      .1       0 2032.65     .06       0
#XS Ineff= 2 ,-1
       0    1729     101    2033  3475.8   103.8
Permanent Ineff=
       F       F
Bank Sta=1854.77,1932.22
XS Rating Curve= 0 ,0
Exp/Cntr=0.5,0.3

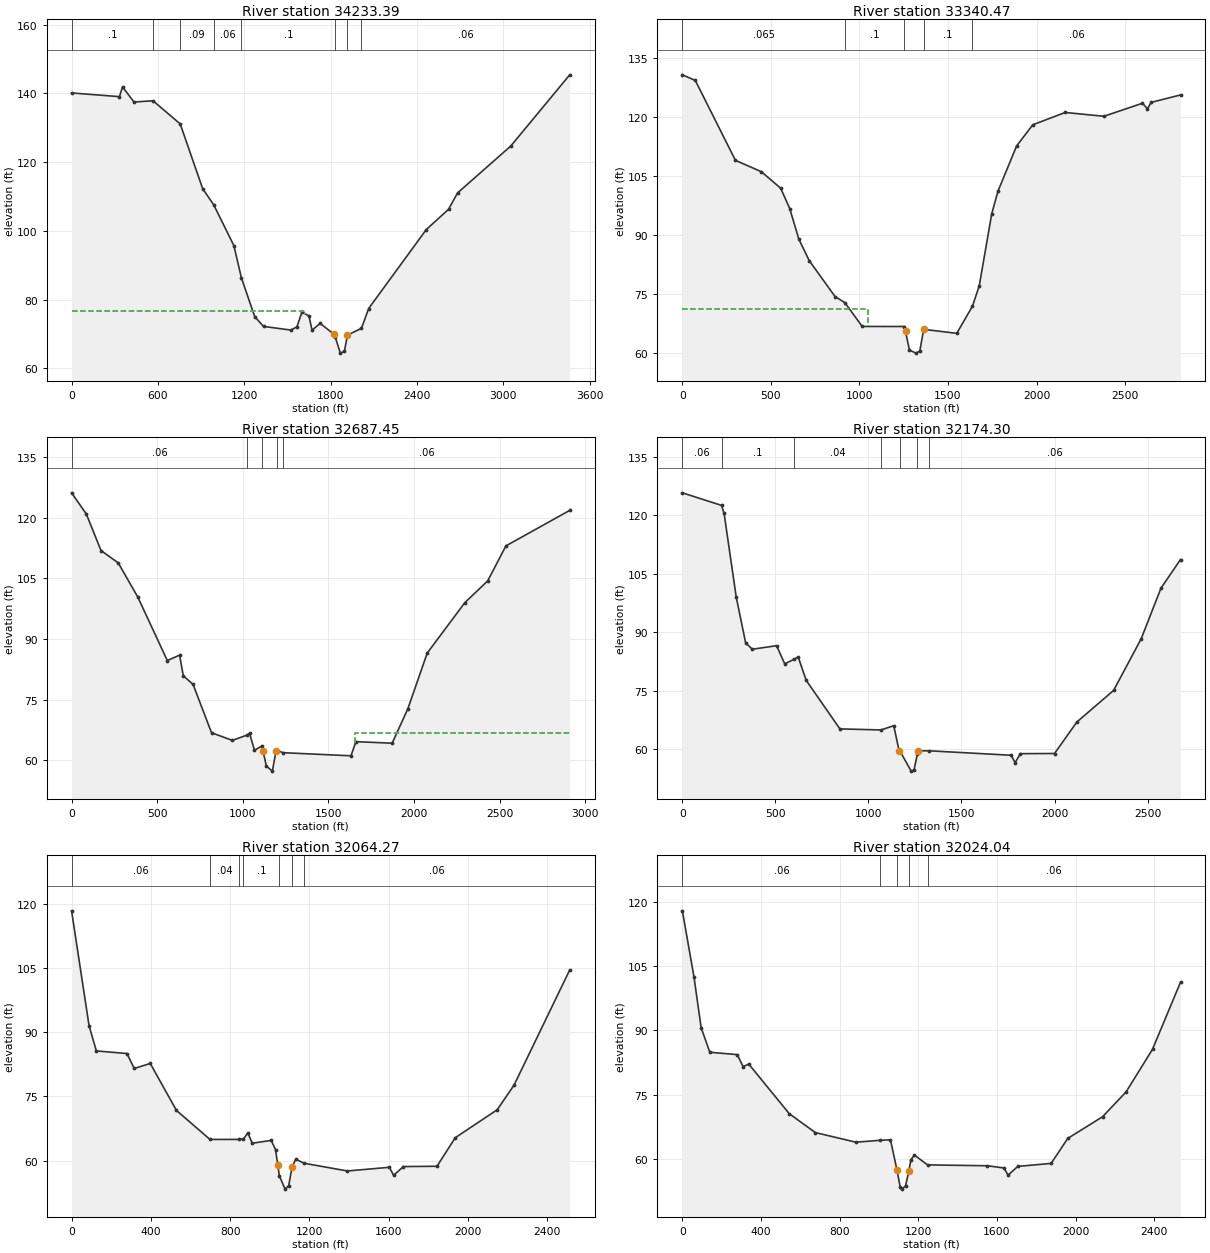
Type RM Length L Ch R = 1 ,34233.39,883.32,892.91,900.92
BEGIN DESCRIPTION:
left ineffective flow limit set to block of flow from backwater areas.
END DESCRIPTION:
XS GIS Cut Line= 4
1633285.65950878721456.9234648941631994.23192345721122.108905762
1630400.87335183720984.5957832491629872.68096413720957.971299604
#Sta/Elev= 30
       0  140.16  332.65  139.08  354.34   141.9  433.89  137.52  566.08137.8831
  755.12131.1431  911.16   112.3  987.09  107.68  1128.1   95.75 1180.2986.38592
 1272.73   75.11 1334.13   72.24 1523.83   71.18 1565.98   72.09 1601.11   76.42
  1650.3   75.28 1671.37   71.13 1727.58   73.12 1825.95    69.9 1832.97   69.11
  1868.1   64.47 1896.21   64.95 1917.28   69.71 2015.0471.68004 2064.83   77.45
 2465.32  100.41 2619.89   106.3 2683.13  111.09 3052.57  124.71 3462.27  145.43
#Mann= 8 ,-1 , 0
       0      .1       0  566.08     .06       0  755.12     .09       0
  987.09     .06       0 1180.29      .1       0 1832.97     .04       0
 1917.28      .1       0 2015.04     .06       0
#XS Ineff= 1 ,-1
  -31.53  1622.376.82667
Permanent Ineff=
       F
Bank Sta=1825.95,1917.28
XS Rating Curve= 0 ,0
Exp/Cntr=0.3,0.1

Type RM Length L Ch R = 1 ,33340.47,676.52,653.02,588.78
XS GIS Cut Line= 4
1632946.56821588720592.8210299021631781.38418509720243.686464727
1631617.33300382 720193.209178181630199.76254037720340.434597254
#Sta/Elev= 30
       0  130.61   73.07  129.19  299.61  108.93  445.76  106.06  555.37  101.86
  606.52   96.69  657.67   88.96  716.13   83.53  862.28    74.4  917.6672.86345
 1015.74   66.82 1252.99   66.81 1260.31   65.56 1282.25   60.83  1318.9   60.06
 1340.87   60.59 1362.84   66.09 1549.87   65.08 1638.1271.94705 1676.55   77.12
 1746.93   95.34 1782.11  101.09 1887.68  112.59 1979.17  117.95 2162.14  121.07
 2380.31   120.1 2598.48  123.41 2626.63  121.99 2647.74  123.63 2813.19  125.51
#Mann= 5 ,-1 , 0
       0    .065       0  917.66      .1       0 1252.99     .04       0
 1362.84      .1       0 1638.12     .06       0
#XS Ineff= 1 ,-1
       0 1049.8171.19787
Permanent Ineff=
       F
Bank Sta=1260.31,1362.84
XS Rating Curve= 0 ,0
Exp/Cntr=0.3,0.1

Type RM Length L Ch R = 1 ,32687.45,531.15,513.16,510.1
XS GIS Cut Line= 3
1632920.75956835719817.0846838651631817.16831176 719573.19711335
1630055.08061485719817.084683865
#Sta/Elev= 30
       0  126.15   86.03  120.92  172.05  111.88  272.42  108.83  387.12  100.35
  559.17   84.69  630.86   86.03  652.37   80.94  709.72   78.78  817.25   66.85
  939.12   64.96 1026.9166.29411 1039.49   66.72 1068.16    62.5 1111.18   63.58
 1118.35   62.31 1137.29   58.62 1172.62   57.36 1193.82   62.33 1200.89   62.49
 1234.6261.91869 1631.96   61.15 1660.23   64.65 1872.23   64.26  1964.1    72.8
 2077.17   86.56 2296.23   98.98  2430.5  104.41  2536.5  113.03  2909.1  121.81
#Mann= 5 ,-1 , 0
       0     .06       0 1026.91      .1       0 1111.18     .04       0
 1200.89      .1       0 1234.62     .06       0
#XS Ineff= 1 ,-1
 1658.08  2909.1   66.88
Permanent Ineff=
       F
Bank Sta=1118.35,1193.82
XS Rating Curve= 0 ,0
Exp/Cntr=0.3,0.1

Type RM Length L Ch R = 1 ,32174.30,110.43,110.03,72.72
XS GIS Cut Line= 4
 1632878.3231311719364.3074091971631731.07599939719063.837922335
1631641.32537341719091.1533302371630256.04397289719274.556783244
#Sta/Elev= 30
       0  125.77  210.69122.5431  224.32  120.47  289.44   99.03   340.1   87.29
  376.28   85.66  506.53   86.57  549.94   81.92  602.0883.12433   622.3    83.7
  665.72   77.66  846.62   65.23 1067.63   64.96 1136.07   66.05 1165.01   59.56
 1172.25   59.27 1229.84    54.4 1244.48   54.66 1263.06   58.73 1266.43    59.6
 1325.9859.61439 1766.97   58.47 1788.15   56.56 1816.39   58.88 1999.98   58.92
 2120.02   66.99 2317.73   75.11 2466.01   88.36 2571.93   101.3 2677.12  108.67
#Mann= 7 ,-1 , 0
       0     .06       0  210.69      .1       0  602.08     .04       0
 1067.63      .1       0 1172.25     .04       0 1263.06      .1       0
 1325.98     .06       0
Bank Sta=1165.01,1266.43
XS Rating Curve= 0 ,0
Exp/Cntr=0.3,0.1

Type RM Length L Ch R = 1 ,32064.27,52.9,40.24,40.8
XS GIS Cut Line= 4
1632666.26896437719286.2976501441631657.77306092718963.743561774
1631581.06357813719026.9160769581630238.58954334719207.036300749
#Sta/Elev= 30
       0  118.36   88.19   91.54  124.94   85.63  279.27   85.03  316.02   81.53
  396.86    82.7  529.15   71.73  698.18   64.96  845.17   64.96  867.22   65.09
  889.27   66.47  911.31   64.07 1006.86   64.73  1028.9    62.6 1039.84   59.03
  1048.3   56.41 1076.96   53.35 1095.09   54.17 1112.62   58.62 1131.37   60.34
 1172.32    59.4 1391.27   57.59 1603.15   58.45 1624.34   56.57 1673.78   58.62
 1843.28   58.69  1935.1   65.35 2146.98   71.89 2231.73   77.63  2512.7  104.54
#Mann= 7 ,-1 , 0
       0     .06       0  698.18     .04       0  845.17     .06       0
  867.22      .1       0  1048.3     .04       0 1112.62      .1       0
 1172.32     .06       0
Bank Sta=1039.84,1112.62
XS Rating Curve= 0 ,0
Exp/Cntr=0.5,0.3

Type RM Length L Ch R = 1 ,32024.04,40.01,40.19,40.8
XS GIS Cut Line= 4
1632678.45435265719248.198879659  1631649.182595 718918.99990885
1631564.43983705718988.7880624381630233.27039225 719167.39154534
#Sta/Elev= 30
       0   117.9   58.79  102.57   95.54   90.64  139.64   84.92  279.27   84.37
  308.67    81.6  338.07   82.14  543.85   70.59  676.14    66.2  881.92   63.96
 1006.86   64.39  1058.3   64.52 1091.44   57.48 1107.84   53.49 1116.91   53.01
 1135.04   53.77 1151.99   57.26 1162.25   59.85 1180.38   60.94 1246.92   58.66
 1550.61   58.46 1635.37   57.95 1656.56   56.28    1706   58.31  1875.5   59.01
 1960.25   64.84 2136.82   69.88 2256.89   75.69 2391.08   85.62 2533.52  101.25
#Mann= 5 ,-1 , 0
       0     .06       0 1006.86      .1       0 1091.44     .04       0
 1151.99      .1       0 1246.92     .06       0
Bank Sta=1091.44,1151.99
XS Rating Curve= 0 ,0
Exp/Cntr=0.5,0.3