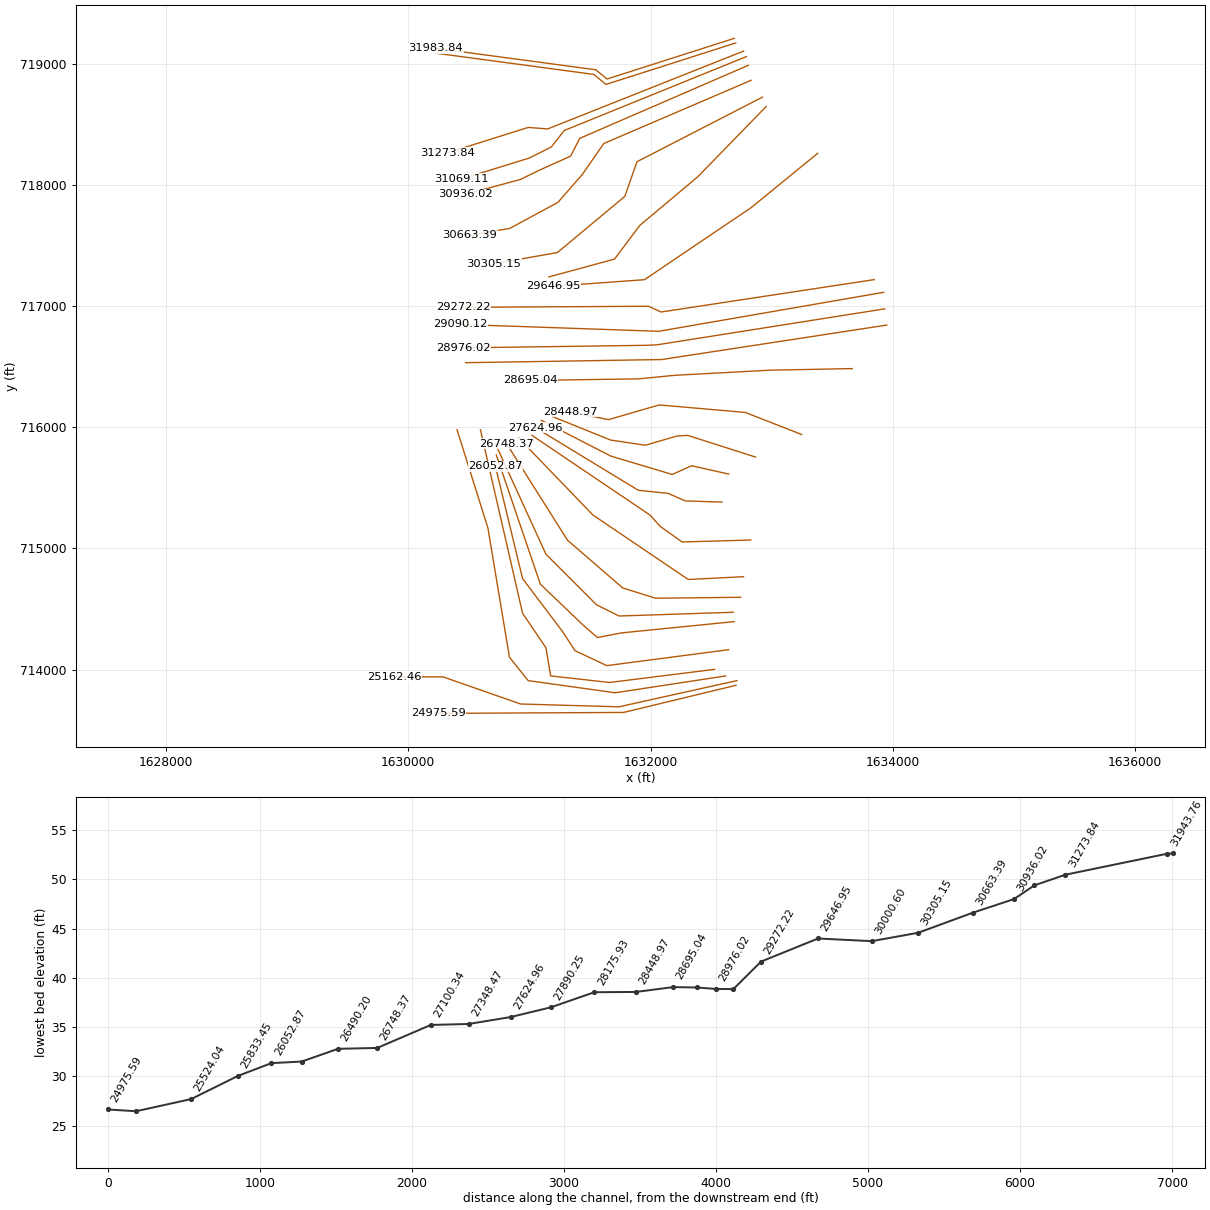
HEC-RAS study LittleElkCreek.prj: Little Elk Creek

--- LittleElkCreek.g01 (geometry) --- (continued)

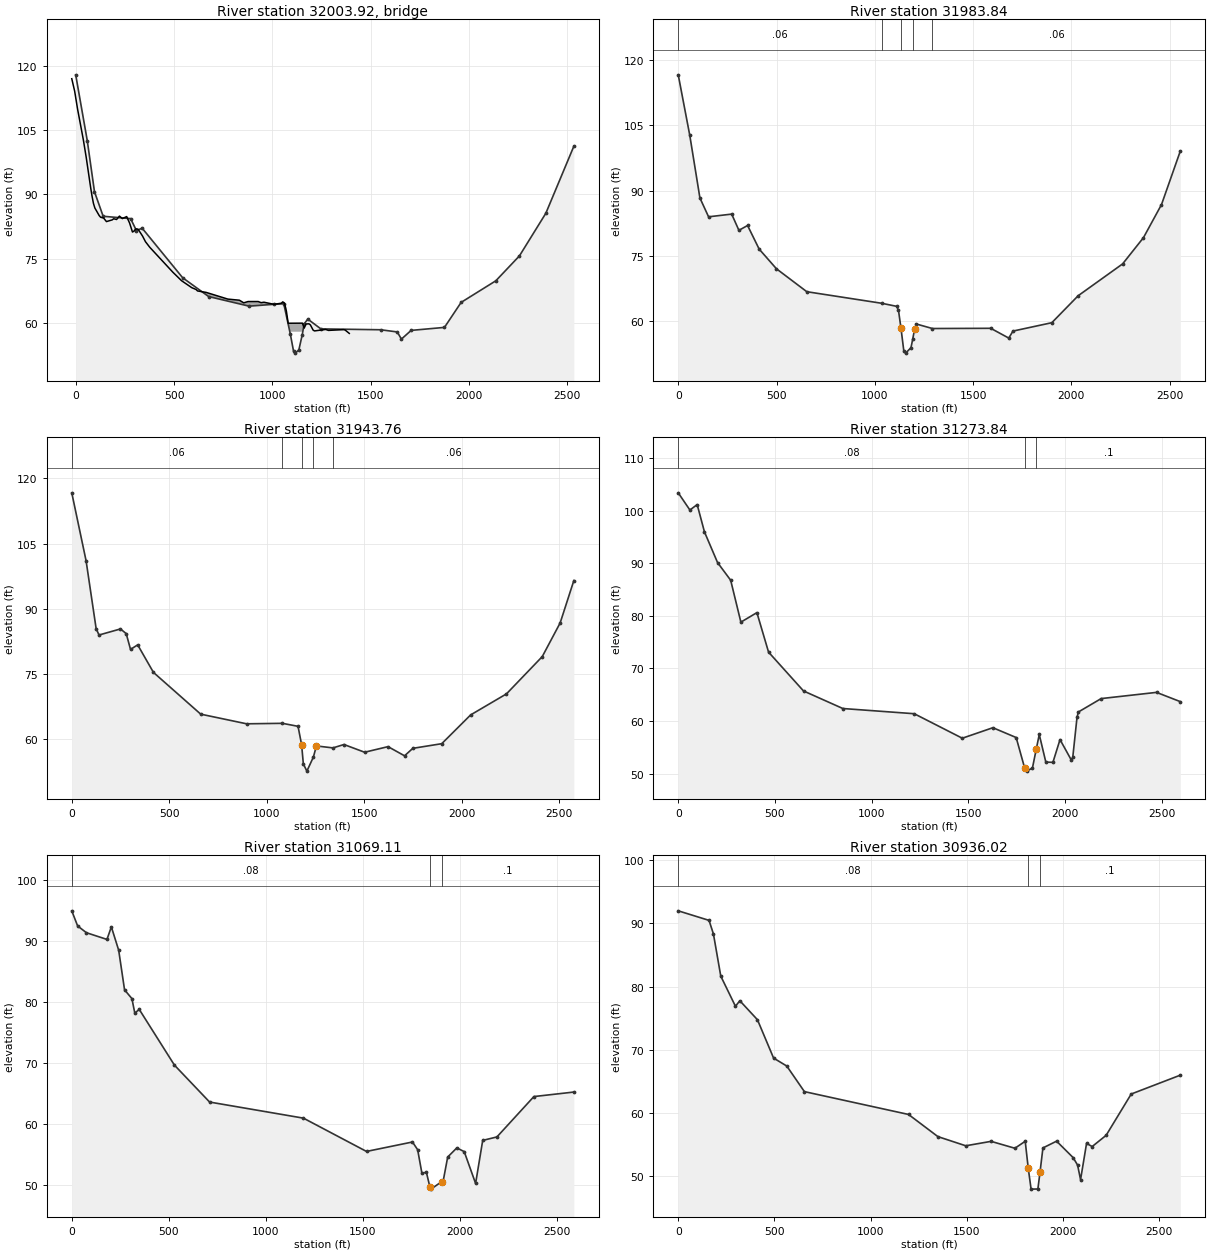
Type RM Length L Ch R = 3 ,32003.92,,,
BEGIN DESCRIPTION:
Herron Lane - CE050307FS-6.  Bridge was not surveyed.  Private property.  No Access. No photographs.  Checked aerial imagery at maps.live.com and it appears that there is a crossing, but appears to be a pedestrian bridge.
 No adjustment made to underwater portion.  Top of bridge estimated from road approach elevation on lidar.
END DESCRIPTION:
Bridge Culvert--1,0,-1,-1, 0
Deck Dist Width WeirC Skew NumUp NumDn MinLoCord MaxHiCord MaxSubmerge Is_Ogee
12,14,2.6,0, 60, 60, , , 0.95, 0, 0,0,,
     -20    -5.3     9.4   38.79   53.49   75.54   82.89   90.24   97.59  119.64
  126.99  141.69  156.38  185.78  193.13  207.83  222.53  237.23  259.27  273.97
  288.67  296.02  303.37  310.72  318.07  340.12  354.82  376.86  494.45  538.55
  589.99  612.04  619.39  663.49  773.73  832.52  854.57  876.62  928.06  942.76
  957.46  1008.9 1045.65    1053 1060.35  1067.7 1071.54 1080.61 1153.15 1162.22
 1171.29 1186.52 1193.59 1207.71 1214.78 1271.28  1285.4 1363.09 1370.16 1391.34
  116.99  114.09  109.93  102.77   98.64   91.75   89.67   87.92   86.83   85.07
   84.68   84.52   83.68   84.08   84.34   84.17   84.96   84.38   84.85   83.35
   81.25   81.44   81.88      82   81.85   80.29   78.99   77.68   71.86   69.89
   68.28   67.85   67.51   67.17   65.61   65.35   64.74   65.04   65.04   64.78
   64.88   64.39   64.65   64.96   64.75   63.61    62.8   59.98      60   58.85
   59.81   59.84   59.59   58.36   58.19   58.53   58.31   58.49    58.4   57.61
                                                                                
                                                                                
                                                                                
                                                                                
                                                              58      58
                                                                                
       0   32.35   83.79  120.54  135.24  142.59  171.99  186.69  201.38  238.13
  252.83  267.53  282.23  304.27  333.67  348.37  363.07  421.86  539.45  583.55
  664.39  818.73  877.52  899.57  973.06  1053.9    1098 1105.35 1116.54 1125.61
 1198.15 1207.22 1216.29 1231.52 1259.78 1408.09 1436.34 1471.66 1549.35 1563.47
 1676.48  1690.6 1697.67 1732.98 1888.36  1937.8  1994.3 2057.87 2177.93 2213.25
 2227.37 2234.43 2248.56 2262.69    2298 2382.75 2446.32 2488.69 2531.07 2568.92
  116.99  115.63  102.77   91.75   87.92   86.83   84.68   84.52   83.68   84.34
   84.17   84.96   84.38   84.85   81.25   81.88   81.85   77.68   71.86   69.89
   67.51   65.61   65.35   64.74   65.04   64.39   64.96   64.75    62.8   59.98
      60   58.85   59.81   59.84   58.19   58.49   57.61   57.28   58.61    58.2
   57.87   56.73   56.63   58.03   58.61   60.25   64.29   66.93   69.74   71.35
   72.77   72.98   72.53   72.99   75.69   80.51   85.89   90.55   96.07     100
                                                                                
                                                                                
                                                                              58
      58
                                                                                
                                                                                
BR Coef=-1 , 0 , 0 ,, 0 ,,,0.8,0,,0,
WSPro=,,,, 1 ,,,, 0 ,,,, 0 ,,,,-1 ,-1 ,-1 , 0 , 0 , 0 , 0 , 0
BR U #Sta/Elev= 30
       0   117.9   58.79  102.57   95.54   90.64  139.64   84.92  279.27   84.37
  308.67    81.6  338.07   82.14  543.85   70.59  676.14    66.2  881.92   63.96
 1006.86   64.39  1058.3   64.52 1091.44   57.48 1107.84   53.49 1116.91   53.01
 1135.04   53.77 1151.99   57.26 1162.25   59.85 1180.38   60.94 1246.92   58.66
 1550.61   58.46 1635.37   57.95 1656.56   56.28    1706   58.31  1875.5   59.01
 1960.25   64.84 2136.82   69.88 2256.89   75.69 2391.08   85.62 2533.52  101.25
BR U #Mann= 5
       0     .06 1006.86      .1 1091.44    .035 1151.99      .1 1246.92     .06
BR D #Sta/Elev= 30
       0  116.64   58.79   102.7  110.24   88.32  154.34   83.98  271.92    84.6
  308.67   80.87  352.77   81.98  411.56   76.56  499.75   72.02  654.09   66.75
 1036.25   64.08 1111.52   63.38 1120.58   62.45 1132.85   58.49 1147.79   53.08
 1156.86   52.62 1184.06   53.87 1192.87   55.81 1211.27   59.32 1293.26   58.28
 1455.71   57.18  1589.9   58.33 1681.71   56.08  1702.9   57.69 1900.66   59.62
 2034.85   65.83 2260.86   73.15  2366.8   79.18 2458.61   86.79 2554.33    99.1
BR D #Mann= 5
       0     .06 1036.25      .1 1132.85    .035 1192.87      .1 1293.26     .06
BC Design=,, 0 ,, 0 ,,,,,,
BC Use User HTab Curves=0
BC User HTab FreeFlow(D)= 0

Type RM Length L Ch R = 1 ,31983.84,40.05,40.08,40.8
XS GIS Cut Line= 4
1632690.63974093719210.1001091751631640.59212913 718874.25625594
1631547.81609598718950.6600479331630227.95124115719127.746789917
#Sta/Elev= 30
       0  116.64   58.79   102.7  110.24   88.32  154.34   83.98  271.92    84.6
  308.67   80.87  352.77   81.98  411.56   76.56  499.75   72.02  654.09   66.75
 1036.25   64.08 1111.52   63.38 1120.58   62.45 1132.85   58.49 1147.79   53.08
 1156.86   52.62 1184.06   53.87 1192.87   55.81  1202.2   58.06 1211.27   59.32
 1293.26   58.28  1589.9   58.33 1681.71   56.08  1702.9   57.69 1900.66   59.62
 2034.85   65.83 2260.86   73.15  2366.8   79.18 2458.61   86.79 2554.33    99.1
#Mann= 5 ,-1 , 0
       0     .06       0 1036.25      .1       0 1132.85     .04       0
 1192.87      .1       0 1293.26     .06       0
Bank Sta=1132.85,1202.2
XS Rating Curve= 0 ,0
Exp/Cntr=0.5,0.3

Type RM Length L Ch R = 1 ,31943.76,458.02,669.92,627.61
XS GIS Cut Line= 4
1632702.82512921719172.0013386911631632.00166327 718829.51260303
 1631531.1923549718912.5320334431630222.63209006719088.102034509
#Sta/Elev= 30
       0  116.69   73.49  101.03  124.94   85.43  139.64   83.94  249.88   85.34
  279.27   84.26  301.32   80.63  338.07   81.67  418.91   75.33  661.44   65.71
  896.62   63.49 1080.35    63.6 1160.53   62.91  1178.9   58.66 1187.74   54.25
 1205.87   52.59 1239.16   55.82 1254.85   58.39 1339.61   57.94 1396.11   58.72
 1502.05   56.94 1622.12   58.23 1706.87   56.12 1749.25   57.84 1897.56   58.91
 2045.88   65.54 2229.51   70.38 2413.14   78.97 2504.96   86.73 2575.14   96.48
#Mann= 5 ,-1 , 0
       0     .06       0 1080.35      .1       0  1178.9     .04       0
 1239.16      .1       0 1339.61     .06       0
Bank Sta=1178.9,1254.85
XS Rating Curve= 0 ,0
Exp/Cntr=0.3,0.1

Type RM Length L Ch R = 1 ,31273.84,111.96,204.73,247.54
XS GIS Cut Line= 4
1632767.73527783719104.921321422 1631150.4181042718462.258893982
 1630990.5733624718474.878215805 1630327.1568394718266.465061188
#Sta/Elev= 30
       0   103.4   60.26  100.13   97.92  101.16  135.58   95.97  203.37   90.13
  271.17   86.77  323.89    78.8  406.75   80.61  467.01    73.1  647.79   65.71
  851.16   62.37 1220.25   61.38 1468.82   56.72    1627   58.72 1747.34   56.85
 1791.28   51.04 1803.52   50.46  1831.6   51.08 1851.25   54.64 1866.71   57.43
 1900.66   52.18 1937.35   52.13 1974.04   56.46 2032.73   52.55 2040.07   53.12
 2062.08   60.73 2069.42   61.72 2186.82   64.26 2472.98   65.44 2596.05   63.68
#Mann= 3 , 0 , 0
       0     .08       0 1791.28     .04       0 1851.25      .1       0
Bank Sta=1791.28,1851.25
XS Rating Curve= 0 ,0
Exp/Cntr=0.3,0.1

Type RM Length L Ch R = 1 ,31069.11,199.5,133.09,126.91
XS GIS Cut Line= 5
1632790.55299111719059.2858949751631287.84359129718449.726984426
1631180.27437174718312.8207050411630997.73266591718221.549852118
1630437.06885517718048.787166253
#Sta/Elev= 30
       0   95.02   30.22   92.54   75.54   91.43   181.3   90.33  203.96   92.39
  241.73   88.55  271.94   82.06  309.71   80.63  324.82   78.24  347.48   78.86
  528.78   69.72  710.07   63.66 1193.53   61.02 1518.35   55.56 1755.16   57.11
 1781.87   55.84 1803.57   52.02 1827.05   52.12 1844.95   49.72 1850.52   49.38
 1905.4850.60152 1913.14   50.67 1936.61   54.64 1983.57   56.14  2021.8   55.53
  2080.4   50.31 2117.03   57.37 2190.27   57.94 2380.72   64.56  2586.5    65.3
#Mann= 3 , 0 , 0
       0     .08       0 1844.95     .04       0 1905.48      .1       0
Bank Sta=1844.95,1905.48
XS Rating Curve= 0 ,0
Exp/Cntr=0.3,0.1

Type RM Length L Ch R = 1 ,30936.02,199.24,272.63,315.79
XS GIS Cut Line= 6
 1632806.8513577718987.5730819551631414.97085068718384.533518046
1631339.99836437718237.8482187091631079.22449888718120.499979243
1630926.01985292718045.5274929261630469.66558835717921.659906819
#Sta/Elev= 30
       0   91.97   160.2   90.46  183.09   88.31  221.23   81.65  297.52   76.89
  320.41   77.76  411.95   74.76  495.87    68.7  564.53   67.44  656.07    63.4
 1197.71   59.79 1350.29   56.29 1495.24   54.84 1626.96   55.54 1750.72   54.45
 1804.45   55.55 1820.14   51.31 1835.01   47.99 1870.29   48.01 1881.24   50.62
 1896.57    54.5  1967.6   55.57 2053.32   52.98  2076.7    51.8 2092.29   49.49
 2123.46   55.22 2152.67   54.72  2225.2   56.49 2355.76   63.02 2611.02      66
#Mann= 3 , 0 , 0
       0     .08       0 1820.14     .04       0 1881.24      .1       0
Bank Sta=1820.14,1881.24
XS Rating Curve= 0 ,0
Exp/Cntr=0.3,0.1

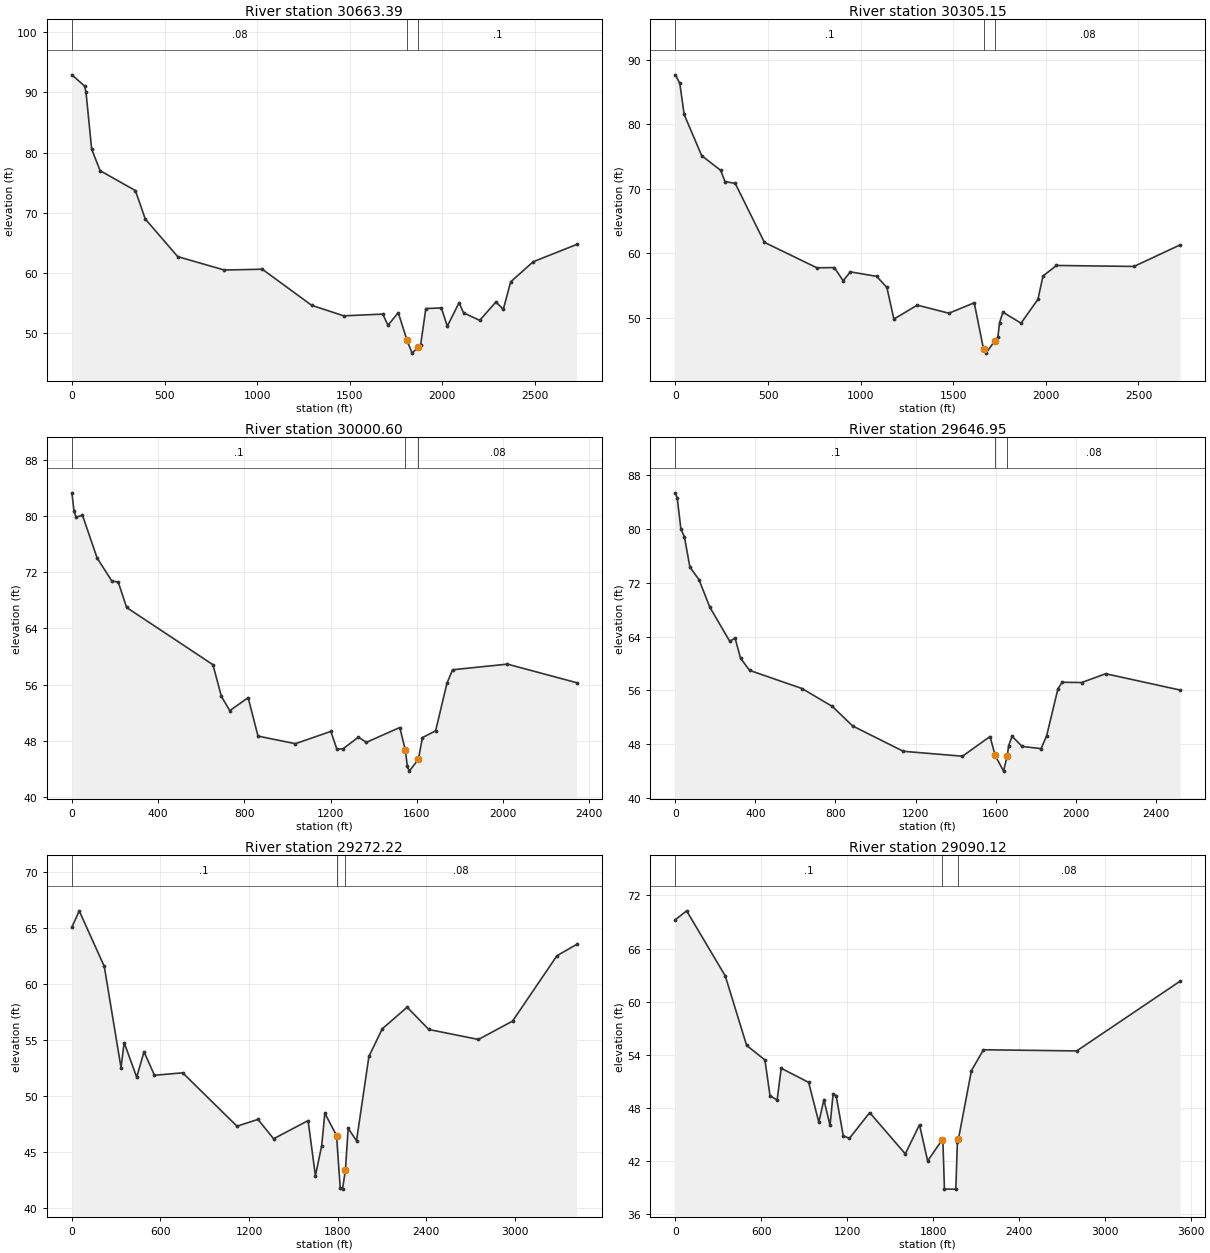
Type RM Length L Ch R = 1 ,30663.39,363.54,358.24,331.67
XS GIS Cut Line= 6
 1632829.6690709718863.7054958491631613.81092311718342.157764912
1631437.78856394 718087.90324606 1631235.6888182717856.466440469
1630838.00867334 717641.328001441630508.78166816717585.913555026
#Sta/Elev= 30
       0   92.94   68.55   91.07   76.17   90.05  106.64   80.58  152.34   76.98
  342.76   73.67  396.08   68.94  571.26   62.67  822.62   60.44 1028.27   60.57
 1294.86   54.56 1467.73   52.81  1678.7    53.1 1706.58   51.24 1762.34   53.34
 1808.64   48.82 1836.69    46.6 1869.96    47.6 1883.15   47.97 1911.03   54.02
  1995.2   54.13 2027.04   51.08 2090.71      55 2114.58   53.31 2202.13   52.06
 2289.67   55.12 2329.47   53.89 2369.26   58.47 2491.01   61.82 2725.49   64.69
#Mann= 3 , 0 , 0
       0     .08       0 1808.64     .04       0 1869.96      .1       0
Bank Sta=1808.64,1869.96
XS Rating Curve= 0 ,0
Exp/Cntr=0.3,0.1

Type RM Length L Ch R = 1 ,30305.15,274.7,304.55,323.7
XS GIS Cut Line= 6
1632923.23376802 718724.807193891631887.86493915 718191.66951336
1631787.41870946717905.7840904741631509.25991961717673.985098958
1631231.10112977717442.1861073971630705.69008234717349.466510788
#Sta/Elev= 30
       0   87.65   23.62   86.32   47.24   81.51  141.72   75.14  244.08   72.87
   267.7   71.12  322.81   70.85  480.28   61.72  763.73   57.78  858.21   57.81
  905.46   55.78  944.82   57.15 1086.55   56.45 1141.66   54.74 1179.41   49.84
 1305.54      52  1476.7   50.75 1613.38   52.36 1663.79   45.16 1677.17   44.57
 1724.83   46.51 1740.95   47.02 1750.06   49.29 1768.29    50.9 1866.12   49.21
 1957.24    52.9 1984.58   56.51 2057.47   58.14 2476.08   57.99 2725.28   61.33
#Mann= 3 , 0 , 0
       0      .1       0 1663.79     .04       0 1724.83     .08       0
Bank Sta=1663.79,1724.83
XS Rating Curve= 0 ,0
Exp/Cntr=0.3,0.1

Type RM Length L Ch R = 1 ,30000.60,404.64,353.65,326.07
XS GIS Cut Line= 5
1632954.14030021 718647.54086338 1632390.0960875718068.043384567
1631911.04483834717666.2584658861631702.42574592717388.099676043
1631161.56143235717241.293648094
#Sta/Elev= 30
       0   83.28    9.77   80.67   19.54   79.81   48.84   80.11  117.22      74
   185.6   70.73   214.9   70.61  253.98   66.98  654.48   58.85  693.56   54.35
  732.63   52.32  817.82   54.16   863.5    48.7 1037.08   47.62 1201.53   49.37
 1228.94    46.9 1256.35   46.86 1329.44   48.55 1365.98   47.81 1521.42   49.92
 1547.62   46.66 1556.42   44.39 1565.17   43.72 1607.81    45.4 1626.42   48.48
 1687.67   49.45 1740.17    56.2 1766.42   58.13 2020.97   58.93 2342.05   56.29
#Mann= 3 , 0 , 0
       0      .1       0 1547.62     .04       0 1607.81     .08       0
Bank Sta=1547.62,1607.81
XS Rating Curve= 0 ,0
Exp/Cntr=0.3,0.1

Type RM Length L Ch R = 1 ,29646.95,449.85,374.73,225.82
XS GIS Cut Line= 5
1633379.10511805718261.2092108281632830.51417139 717813.06449388
1632212.38352729717395.8263091151631949.67800356717218.113748938
1631200.19459762717164.027317554
#Sta/Elev= 30
       0   85.39    9.04   84.58   27.12   80.07   45.19    78.8   72.31   74.34
   117.5   72.49  171.74   68.39  271.16   63.32  298.28   63.76   325.4   60.79
  370.59   58.98  632.71   56.28  784.38   53.61  885.72   50.71 1139.09   46.94
 1434.68   46.21 1572.45   49.14 1597.9146.33456 1640.06   43.99  1658.2   46.28
 1665.42   47.76 1682.32   49.18 1733.03   47.66 1827.45   47.34 1855.52   49.27
 1911.67   56.23 1932.72   57.21 2030.98   57.17 2150.29   58.48 2522.74   56.05
#Mann= 3 , 0 , 0
       0      .1       0 1597.91     .04       0  1658.2     .08       0
Bank Sta=1597.91,1658.2
XS Rating Curve= 0 ,0
Exp/Cntr=0.3,0.1

Type RM Length L Ch R = 1 ,29272.22,201.31,182.1,206.29
XS GIS Cut Line= 4
1633845.97957422717218.7674465331632086.83434677716951.446359649
1631983.35521512716998.8742942811630457.03803258716990.251033783
#Sta/Elev= 30
       0   65.05   49.56   66.51  219.49   61.54  332.78    52.5  354.02   54.74
  438.98   51.65  488.54   53.92  559.35   51.82  750.52   52.04  1118.7   47.27
  1260.3   47.88 1366.51   46.15 1600.16   47.77 1649.72   42.84  1692.2   45.53
 1713.45   48.43 1792.84   46.44 1817.84   41.74 1833.24   41.65 1853.02   43.37
 1871.74   47.08 1928.17   45.97 2012.17   53.51 2103.17   55.98 2271.17    57.9
 2418.17   55.91 2754.17   55.02 2985.17   56.66 3286.17    62.5 3419.49   63.51
#Mann= 3 , 0 , 0
       0      .1       0 1792.84     .04       0 1853.02     .08       0
Bank Sta=1792.84,1853.02
XS Rating Curve= 0 ,0
Exp/Cntr=0.5,0.3

Type RM Length L Ch R = 1 ,29090.12,116.34,114.1,120.2
XS GIS Cut Line= 3
1633924.56564336 717114.094699861632066.67490384 716792.22436665
1630427.38335995716848.975708023
#Sta/Elev= 30
       0   69.26   78.15   70.25  348.11   62.91   497.3   55.07  625.18   53.43
   660.7   49.39  710.43   48.91  738.84   52.49  930.66    50.9  1001.7    46.4
 1037.22   48.95 1079.85   46.05 1101.16   49.55 1122.47    49.4  1172.2   44.89
 1214.83   44.58 1356.91   47.49 1605.56   42.84 1705.02   46.12 1761.86   42.04
 1861.32   44.38 1868.42   44.28 1879.16   38.86 1958.72   38.86 1969.61   44.21
 1976.62   44.49 2067.67   52.23 2151.72   54.58 2803.11   54.45 3525.83   62.32
#Mann= 3 , 0 , 0
       0      .1       0 1861.32     .04       0 1976.62     .08       0
Bank Sta=1861.32,1976.62
XS Rating Curve= 0 ,0
Exp/Cntr=0.5,0.3

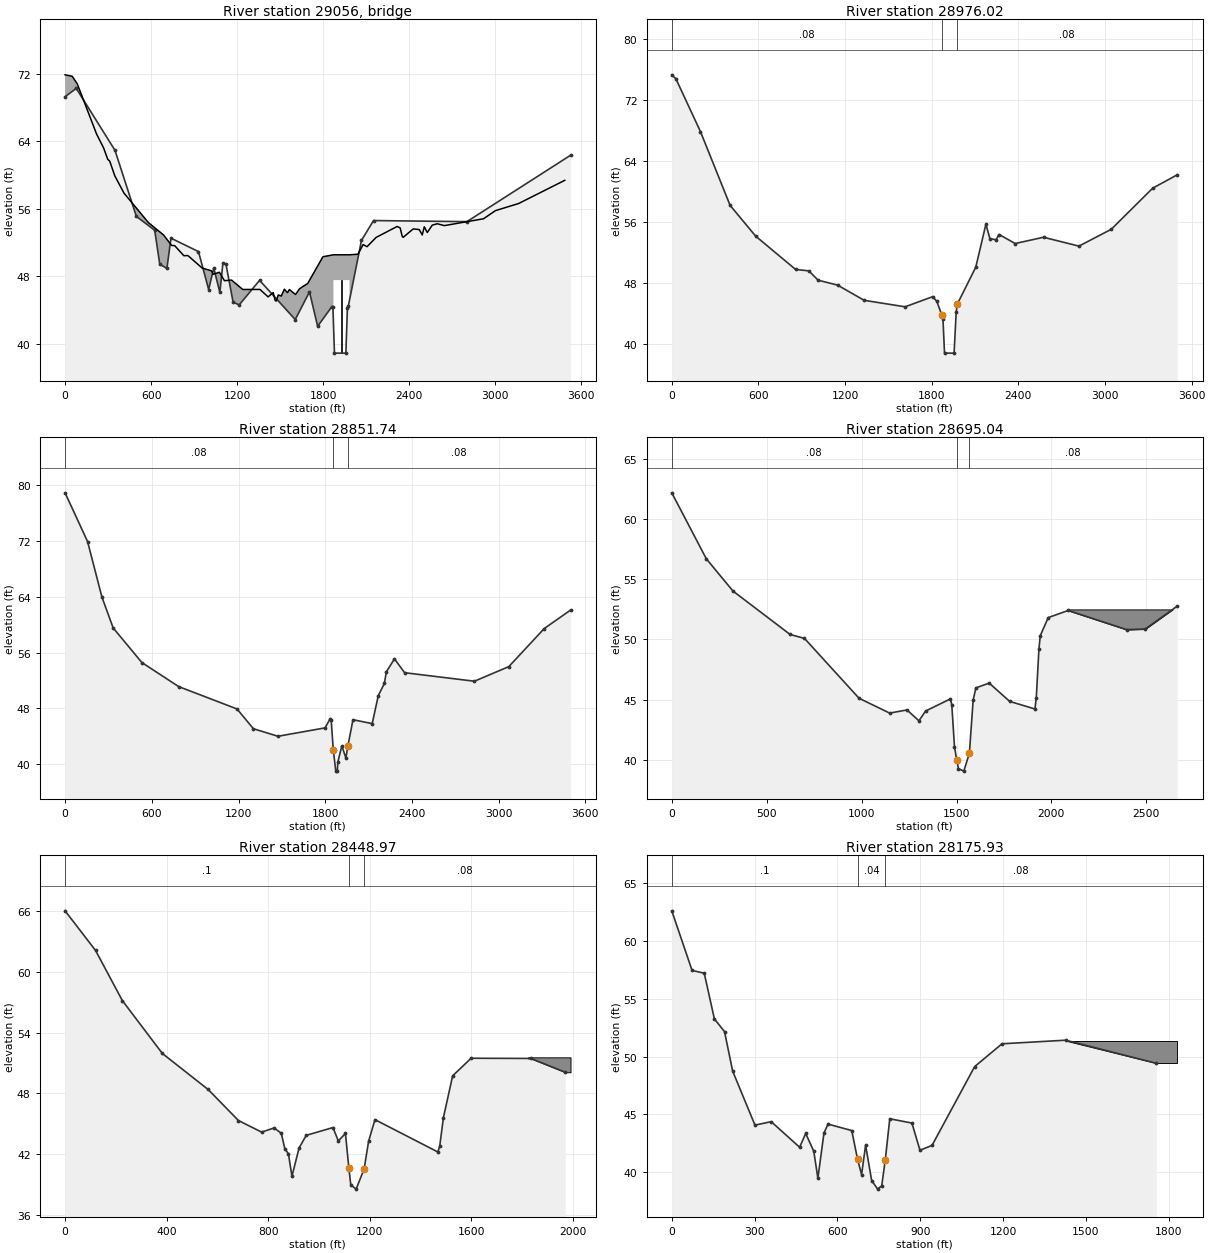
Type RM Length L Ch R = 3 ,29056   ,,,
Node Photo=IMG_1325.JPG
BEGIN DESCRIPTION:
Zeitler Road.  Bridge No CE050307PF-4.  Top of Road from Lidar.  Bridge Geometry from HEC2 model section 227.2.
 Pier was coded as 4ft at the base and 2 ft at the bridge deck to more realistically reflect the pier geometry.   Dimensions of the pier was estimated from photographs.  Bridge Inspection report supports the geometry coded in the HEC2 model.
END DESCRIPTION:
Bridge Culvert--1,0,-1,-1, 0
Deck Dist Width WeirC Skew NumUp NumDn MinLoCord MaxHiCord MaxSubmerge Is_Ogee
35,24,2.6,0, 60, 60, , , 0.95, 0, 0,0,,
       0   49.57   84.98  219.53   269.1  297.43  311.59     347  410.74   580.7
  686.92  743.58  764.82  828.56  856.88  956.03 1019.76 1033.92 1076.41 1111.82
 1161.39 1239.29 1359.68 1416.33 1451.74 1465.91 1472.99 1487.15  1508.4 1529.64
 1550.89 1565.05 1607.54 1635.87 1692.52 1798.74  1871.9    1872 1984.39  1984.5
 2043.58 2078.58 2106.59 2169.59 2316.61 2337.62 2351.62 2358.62 2428.63 2470.64
 2491.64 2505.64 2526.64 2561.65 2596.65 2645.66  2918.7 3002.71 3163.73 3485.78
   71.86   71.69    70.8   64.85   63.18   61.85   61.62   59.88   57.84   54.35
   52.87   51.63    51.6   50.41   50.43   48.95   48.63   48.21   48.45   47.45
   47.52   46.41   46.41   45.53   46.05    45.1   45.03   45.76   45.63   46.44
   46.03    46.4   45.81    46.5   47.12   50.29   50.52   50.52   50.52   50.52
   50.59   51.73   51.48   52.58   53.88   53.71   52.71   52.59   53.59   53.51
   52.87   53.84   53.16   54.04    54.2   53.98   54.79   55.76    56.6   59.35
                                                                                
                                                                                
                                                                                
                                                           47.52   47.52
                                                                                
                                                                                
       0   49.57   84.98  219.53   269.1  297.43  311.59     347  410.74   580.7
  686.92  743.58  764.82  828.56  856.88  956.03 1019.76 1033.92 1076.41 1111.82
 1161.39 1239.29 1359.68 1416.33 1451.74 1465.91 1472.99 1487.15  1508.4 1529.64
 1550.89 1565.05 1607.54 1635.87 1692.52 1798.74  1871.9    1872 1984.39  1984.5
 2043.58 2078.58 2106.59 2169.59 2316.61 2337.62 2351.62 2358.62 2428.63 2470.64
 2491.64 2505.64 2526.64 2561.65 2596.65 2645.66  2918.7 3002.71 3163.73 3485.78
   71.86   71.69    70.8   64.85   63.18   61.85   61.62   59.88   57.84   54.35
   52.87   51.63    51.6   50.41   50.43   48.95   48.63   48.21   48.45   47.45
   47.52   46.41   46.41   45.53   46.05    45.1   45.03   45.76   45.63   46.44
   46.03    46.4   45.81    46.5   47.12   50.29   50.52   50.52   50.52   50.52
   50.59   51.73   51.48   52.58   53.88   53.71   52.71   52.59   53.59   53.51
   52.87   53.84   53.16   54.04    54.2   53.98   54.79   55.76    56.6   59.35
                                                                                
                                                                                
                                                                                
                                                           47.52   47.52
                                                                                
                                                                                
Pier Skew, UpSta & Num, DnSta & Num=  ,1928.3, 2 ,1928.3, 2 , 0 , 0 , 0 ,,
       4       2
      35      49
       4       2
      35      49
BR Coef=-1 , 1 , 0 ,, 0 ,,,0.8,0,2,0,
WSPro=,,,, 1 ,,,, 0 ,,,, 0 ,,,,-1 ,-1 ,-1 , 0 , 0 , 0 , 0 , 0
BC Design=,, 0 ,, 0 ,,,,,,
BC Use User HTab Curves=0
BC User HTab FreeFlow(D)= 0

Type RM Length L Ch R = 1 ,28976.02,137.48,124.28,120.58
XS GIS Cut Line= 4
1633932.84935765716977.4578533321632056.13646509716681.029909149
 1631969.8794594716676.6716213381630456.01950839 716655.68170549
#Sta/Elev= 30
       0   75.28   28.35   74.77  198.43   67.86  403.95    58.2  581.12   54.17
   857.5   49.82  949.63   49.63 1013.41   48.41 1148.06   47.77 1332.32   45.78
 1615.79   44.93 1807.13   46.26 1835.48   45.64 1870.91    43.8    1878   43.37
 1888.79   38.87 1955.04   38.87  1969.5    44.2 1977.08   45.27 2105.36   50.12
 2175.37   55.73 2203.37   53.83 2245.38   53.71 2266.38   54.39 2378.39   53.21
 2574.41   54.03 2819.44   52.87 3043.46   55.07 3330.49   60.45 3500.37    62.2
#Mann= 3 , 0 , 0
       0     .08       0 1870.91     .04       0 1977.08     .08       0
Bank Sta=1870.91,1977.08
XS Rating Curve= 0 ,0
Exp/Cntr=0.5,0.3

Type RM Length L Ch R = 1 ,28851.74,165.43,156.7,148.67
XS GIS Cut Line= 3
1633949.45870593716843.6555976871632091.14597704716559.087986007
1630474.28455548716533.218204498
#Sta/Elev= 30
       0   78.86   155.8   71.88  254.94   63.94  332.84   59.52  531.12   54.57
  786.06   51.12 1189.71   47.92 1303.01   45.09 1472.97   44.01 1798.72   45.21
 1834.13   46.53 1841.21   46.35 1855.37   42.11 1873.15   39.03 1883.82   39.02
 1886.97    40.3 1914.97   42.64 1942.98   40.89 1956.98   42.65 1991.98   46.38
    2125   45.82 2167.01   49.82 2209.01   51.57 2223.01   53.23 2279.02    55.1
 2349.03   53.11  2832.1   51.89 3070.13   53.98 3315.17   59.43 3497.05   62.07
#Mann= 3 , 0 , 0
       0     .08       0 1855.37     .04       0 1956.98     .08       0
Bank Sta=1855.37,1956.98
XS Rating Curve= 0 ,0
Exp/Cntr=0.3,0.1

Type RM Length L Ch R = 1 ,28695.04,268.5,246.07,243.92
XS GIS Cut Line= 5
1633665.03852582716484.4017007351632987.02647562716471.363007471
1632198.18553256716428.9872543361631901.55526057716399.650194451
1631005.14509797716386.611501172
#Sta/Elev= 30
       0   62.17  182.03   56.69  322.06   54.02  623.11   50.41  699.17   50.08
  986.58   45.11 1147.81   43.88 1238.94   44.14 1302.04   43.24 1337.09   44.05
 1468.12   45.06 1475.15   44.55 1489.22    41.1 1500.96   39.98 1510.32   39.26
 1538.46   39.06  1567.8   40.55  1587.7   44.95 1601.77   45.97 1672.11   46.37
  1780.2   44.85 1913.21   44.22 1920.21   45.15 1934.21   49.21 1941.21   50.31
 1983.22   51.81 2088.23    52.4 2396.26   50.81 2494.27   50.86  2662.7   52.76
#Mann= 3 , 0 , 0
       0     .08       0 1500.96     .04       0  1567.8     .08       0
#Block Obstruct= 1 ,-1
 2082.24 2649.67   52.49
Bank Sta=1500.96,1567.8
XS Rating Curve= 0 ,0
Exp/Cntr=0.3,0.1

Type RM Length L Ch R = 1 ,28448.97,250.85,273.03,301.25
XS GIS Cut Line= 5
1633247.80034105715940.0362565521632781.66705658716122.577962384
1632071.05827312716184.5117554371631652.62324417716063.113938406
1631337.51104781716126.863829151
#Sta/Elev= 30
       0      66  120.28   62.09  225.53   57.16   383.4   51.94  563.84   48.39
  683.29   45.33  774.64   44.19  823.82    44.6  851.93   44.08  865.98   42.56
  880.03   42.06  894.09   39.84  922.19   42.63   950.3   43.87  1055.7   44.64
 1076.78   43.32 1104.88   44.06  1118.4   40.63 1125.96   38.99 1147.04   38.57
 1178.52   40.57 1196.23    43.3 1221.19   45.42 1469.01   42.23  1476.3   42.79
 1490.87   45.61 1527.32   49.74  1600.2   51.47 1835.28   51.45 1971.09   50.09
#Mann= 3 , 0 , 0
       0      .1       0  1118.4     .04       0 1178.52     .08       0
#Block Obstruct= 1 ,-1
 1824.01 1991.78   51.56
Bank Sta=1118.4,1178.52
XS Rating Curve= 0 ,0
Exp/Cntr=0.3,0.1

Type RM Length L Ch R = 1 ,28175.93,253.51,285.69,199.17
XS GIS Cut Line= 6
1632866.41856278715754.2348774081632305.75475204715933.516909912
1632214.48389916715926.9975632731631956.96970697 715852.02507697
1631670.80539283715894.4197901791631190.70501986716088.230663896
#Sta/Elev= 30
       0   62.59   73.49   57.44  117.59    57.2  154.33   53.25  191.08   52.15
  220.48   48.74  301.32   44.07  360.11   44.37     463   42.16  485.05   43.35
  514.44    41.8  529.14   39.48  551.19   43.39  565.89   44.16  651.79    43.6
  672.84   41.12  687.42    39.8  702.01   42.34  723.88   39.28  745.75   38.54
  760.33   38.83  773.24   41.06  789.49   44.62  869.69   44.25  898.85    41.9
   942.6   42.32 1096.95   49.13 1196.02    51.1 1426.35   51.41 1755.37   49.41
#Mann= 3 , 0 , 0
       0      .1       0  672.84     .04       0  773.24     .08       0
#Block Obstruct= 1 ,-1
 1427.63 1830.59   51.38
Bank Sta=672.84,773.24
XS Rating Curve= 0 ,0
Exp/Cntr=0.3,0.1

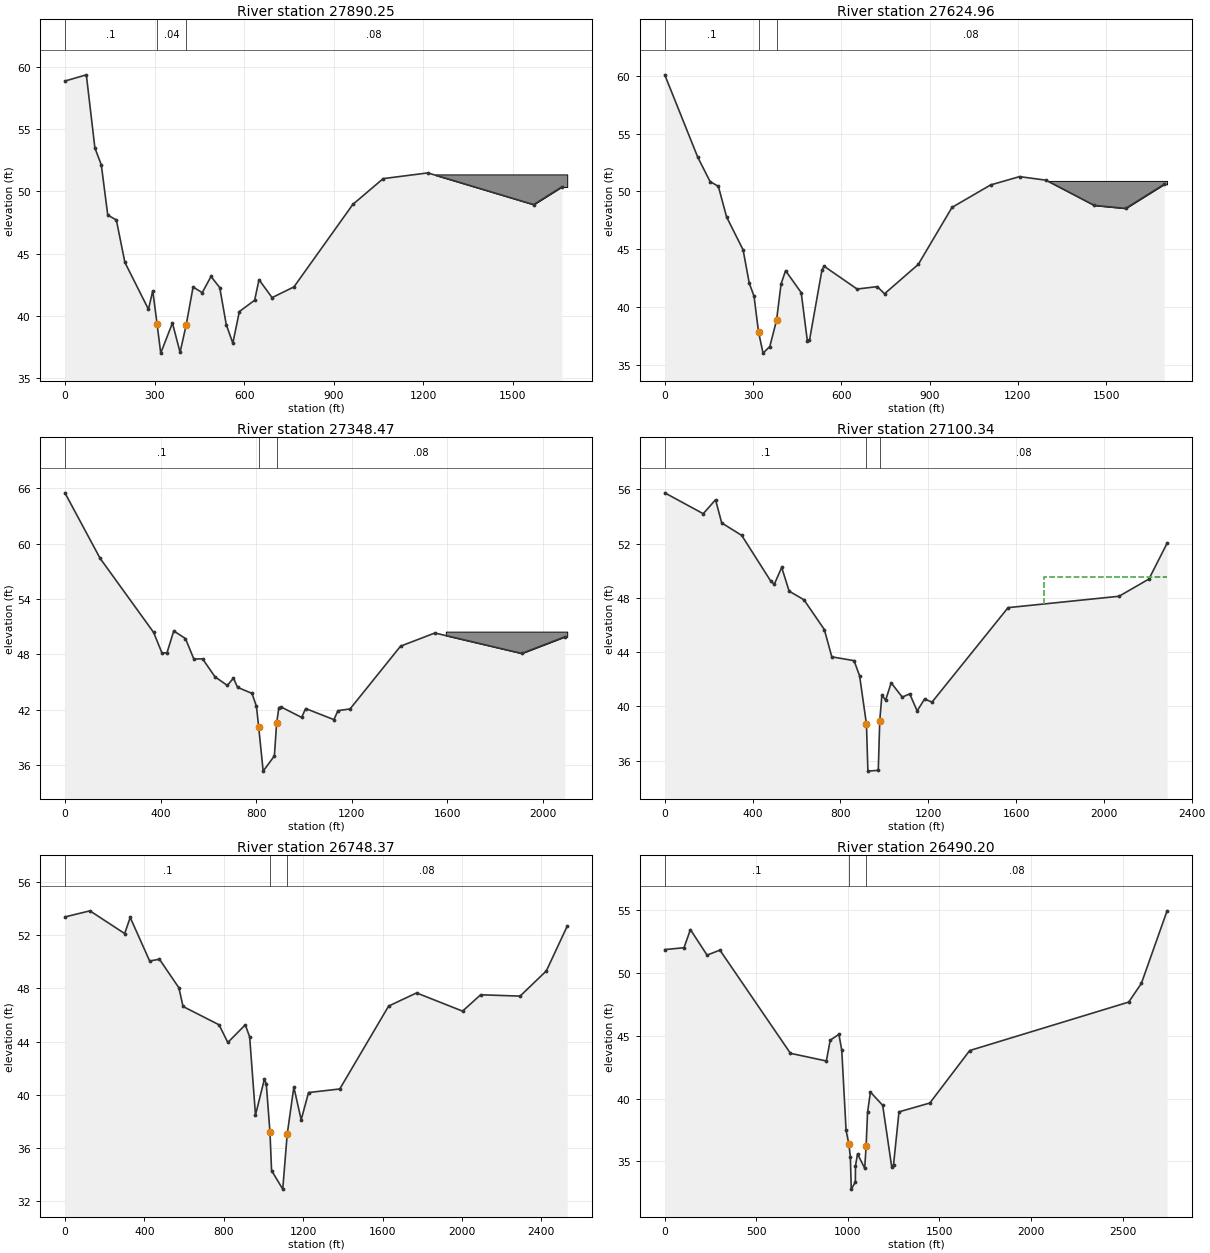
Type RM Length L Ch R = 1 ,27890.25,297.13,265.29,197.45
XS GIS Cut Line= 5
1632644.76077715 715614.068924711632338.35148524715682.522064388
1632178.62749261715610.8092513981631671.64934392715762.319962502
1631097.98542325716057.324131712
#Sta/Elev= 30
       0   58.87   71.73   59.37  100.42   53.49  121.93   52.13  143.45    48.1
  172.14   47.71  200.83    44.3  279.73   40.53  294.07   42.02  308.42   39.38
  320.78   37.01     360   39.43  385.55   37.07  406.04   39.28  429.06   42.32
  459.75   41.87  489.05   43.17  518.27   42.28  540.19    39.3  562.11   37.81
  584.02   40.35  635.16   41.26  649.78   42.91  693.61   41.47  766.67   42.33
  963.93   48.96 1065.41   51.03 1214.96   51.49 1569.17   48.94 1663.25   50.36
#Mann= 3 , 0 , 0
       0      .1       0  308.42     .04       0  406.04     .08       0
#Block Obstruct= 1 ,-1
 1240.46 1681.58   51.37
Bank Sta=308.42,406.04
XS Rating Curve= 0 ,0
Exp/Cntr=0.3,0.1

Type RM Length L Ch R = 1 ,27624.96,297.64,276.49,135.93
XS GIS Cut Line= 5
1632589.34633075715382.6321190891632286.19671215715392.411139071
1632146.03075942715454.3449321091631898.29558726715480.422318652
1631051.62562494715995.511067301
#Sta/Elev= 30
       0   60.08  112.06   52.96  154.08   50.85  182.09   50.44  210.11   47.79
  266.14   44.95  287.15   42.06  303.31   40.94  318.61   37.85  333.92   36.02
  356.88   36.59  379.84   38.86  395.14      42  410.45   43.15  463.59   41.25
   484.7   37.03  491.74   37.13  533.97   43.19  541.01   43.54  653.63   41.56
  722.04   41.77  746.62   41.15  861.33   43.69  976.04   48.62 1107.14   50.56
 1205.46   51.28 1295.59   50.97 1459.46   48.79 1565.98   48.53 1696.69   50.61
#Mann= 3 , 0 , 0
       0      .1       0  318.61     .04       0  379.84     .08       0
#Block Obstruct= 1 ,-1
 1221.22 1706.74   50.91
Bank Sta=318.61,379.84
XS Rating Curve= 0 ,0
Exp/Cntr=0.3,0.1

Type RM Length L Ch R = 1 ,27348.47,232.96,248.13,263.67
XS GIS Cut Line= 5
1632827.30248299715069.7034805271632260.11932558715053.405113935
1632077.57761973715183.7920466811631996.08578677715275.062899604
1631020.71909274715933.698002875
#Sta/Elev= 30
       0   65.52  147.06   58.42  371.15   50.37  406.17   48.13  427.18   48.17
  455.19   50.53  504.21   49.71  539.22   47.49  576.02    47.5  627.63   45.56
  679.25   44.62  705.05   45.41  722.26   44.41  782.47   43.76  801.13   42.35
  810.69   40.08  829.28   35.32   876.2   36.97  885.58   40.51  894.97   42.22
  904.35   42.28  990.12   41.15 1007.01   42.11 1125.26   40.91 1142.16   41.88
 1192.84   42.07    1404   48.88 1547.59   50.31 1910.79   48.09 2091.02   49.89
#Mann= 3 , 0 , 0
       0      .1       0  810.69     .04       0  885.58     .08       0
#Block Obstruct= 1 ,-1
 1593.34 2101.15   50.46
Bank Sta=810.69,885.58
XS Rating Curve= 0 ,0
Exp/Cntr=0.3,0.1

Type RM Length L Ch R = 1 ,27100.34,354.77,351.97,321.72
XS GIS Cut Line= 4
 1632766.9381623714766.9764121471632311.06681226714743.796512991
1631522.95024103715276.9341935221630912.54623002715910.518103719
#Sta/Elev= 30
       0   55.75  175.23   54.21   231.3   55.24  259.33   53.53  350.45   52.61
  481.81   49.26  498.72      49  532.52   50.25  566.33    48.5  633.94   47.86
   726.9   45.66   760.7   43.65  862.12   43.37  887.47   42.24  918.53   38.69
  925.16   35.22  972.45   35.28  979.16   38.94  988.89   40.84 1005.79   40.45
 1031.14   41.73 1081.85   40.68 1115.66   40.92 1149.46   39.66 1183.26   40.54
 1217.07   40.31 1563.49   47.28 2068.93   48.12 2205.01   49.39 2287.75   52.03
#Mann= 3 , 0 , 0
       0      .1       0  918.53     .04       0  979.16     .08       0
#XS Ineff= 2 , 0
                         1726.97           49.52
Permanent Ineff=
       F       F
Bank Sta=918.53,979.16
XS Rating Curve= 0 ,0
Exp/Cntr=0.3,0.1

Type RM Length L Ch R = 1 ,26748.37,225.39,258.17,228.07
XS GIS Cut Line= 5
1632743.75826313714596.9904850421632040.63465549714589.263851985
1631770.20249867714674.2568155531631314.33114868715068.315101162
1630812.10000032715864.158305436
#Sta/Elev= 30
       0   53.38  126.01   53.84  301.02   52.13  329.02   53.34  427.03   50.06
  476.03    50.2  574.03   48.05  595.04   46.64  776.54   45.26  820.57   43.93
  908.62   45.26  930.63   44.35  959.98   38.47 1005.15   41.18  1014.4    40.8
  1032.9    37.2 1041.01   34.29 1097.31   32.89 1119.65   37.01 1153.19   40.57
  1190.2   38.11 1227.21   40.16 1384.51   40.43  1630.6   46.67 1771.32   47.66
 2003.08   46.29 2094.14   47.52 2292.79   47.42 2425.23   49.32 2530.28   52.69
#Mann= 3 , 0 , 0
       0      .1       0  1032.9     .04       0 1119.65     .08       0
Bank Sta=1032.9,1119.65
XS Rating Curve= 0 ,0
Exp/Cntr=0.3,0.1

Type RM Length L Ch R = 1 ,26490.20,245.48,238.43,203.4
XS GIS Cut Line= 5
1632681.94519871 714473.364356221631739.29596646714442.457824022
1631553.85677324714535.1774206311631136.61858848714952.415605396
1630719.38040371715864.158305436
#Sta/Elev= 30
       0   51.83  105.06   51.98  140.08   53.42  231.12   51.39  301.16   51.79
  686.37   43.59  882.47   42.98  903.49   44.63  950.98    45.1  966.64   43.84
  990.11   37.48 1005.77   36.35 1013.59   35.34 1018.55    32.8 1040.82   33.36
 1041.61   34.65 1052.72    35.6 1091.86   34.46 1099.68   36.22 1107.51   38.91
 1123.16   40.51 1190.08   39.46 1239.58   34.55 1249.48   34.75 1279.18   38.94
 1447.47   39.64 1665.26   43.81 2533.47   47.66 2602.75   49.14 2743.23   54.91
#Mann= 3 , 0 , 0
       0      .1       0 1005.77     .04       0 1099.68     .08       0
Bank Sta=1005.77,1099.68
XS Rating Curve= 0 ,0
Exp/Cntr=0.3,0.1

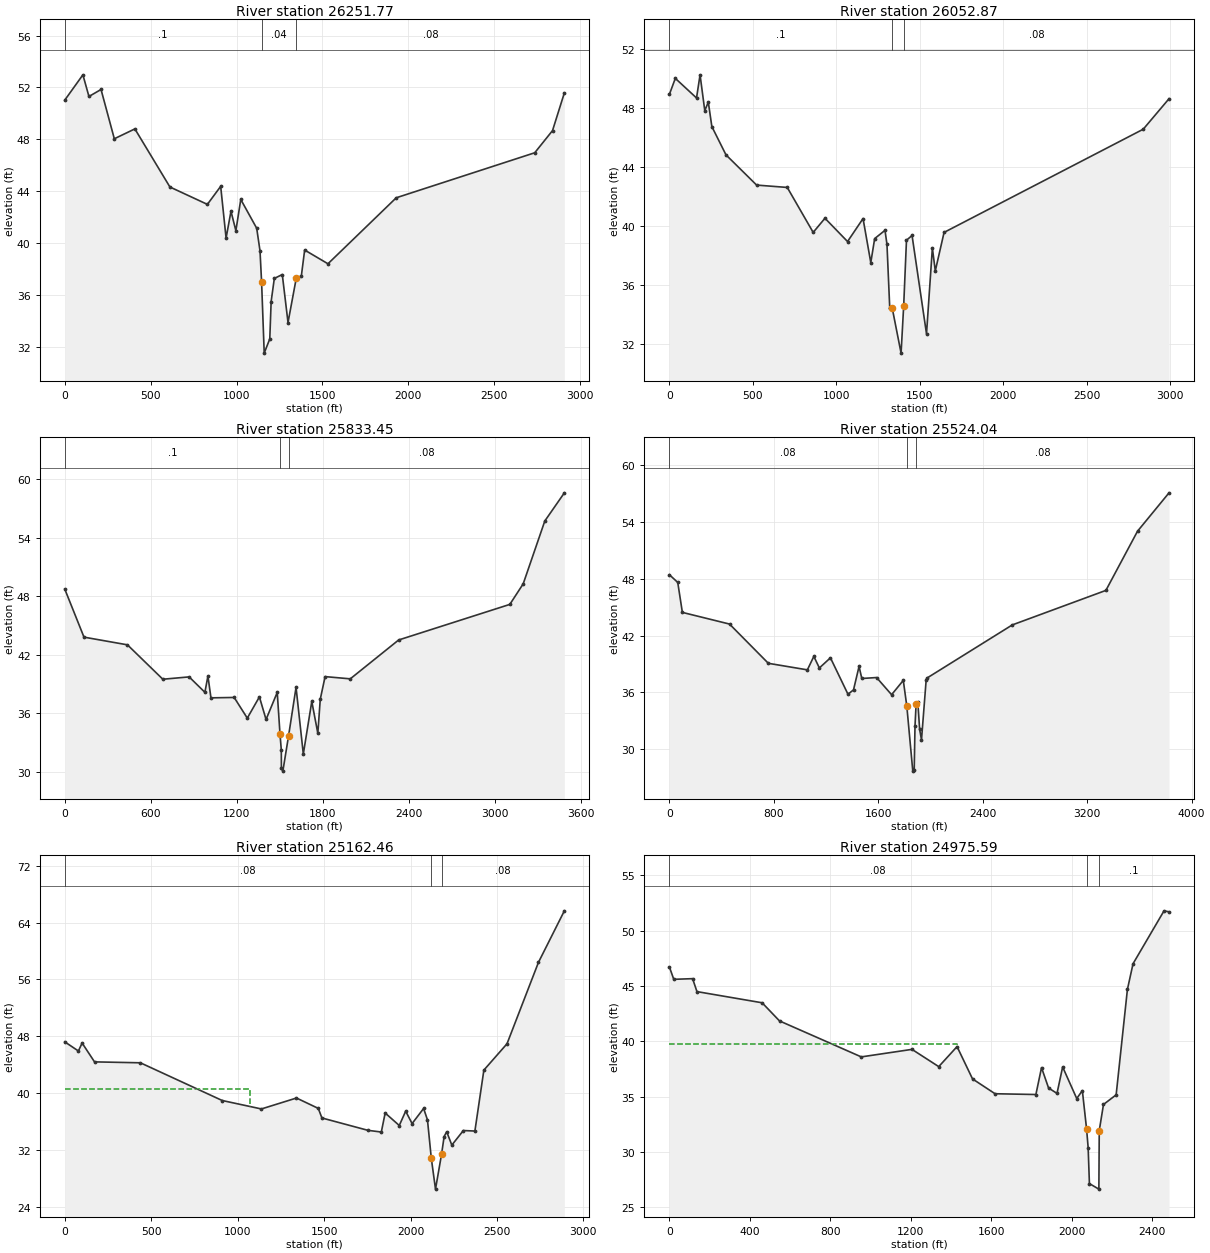
Type RM Length L Ch R = 1 ,26251.77,187.01,198.9,122.19
XS GIS Cut Line= 6
1632689.67183179714396.0980257091631762.47586565  714303.3784291
1631561.58340631714264.7452638451631445.68391052714365.191493511
1631090.25879017714705.1633477361630727.10703678715771.438708797
#Sta/Elev= 30
       0   51.02  105.52   52.97   140.7    51.3  211.05   51.84  288.43   48.04
  408.02    48.8  612.04   44.32  830.12   42.98   907.5   44.37  938.95   40.38
  967.46   42.45  995.97   40.95 1024.49   43.36 1117.16   41.14 1136.39    39.4
 1145.66   36.99 1160.89   31.51 1193.33   32.61 1201.24   35.49 1219.76   37.27
 1266.08   37.57 1299.45   33.87 1347.88   37.32 1376.94   37.45 1396.32   39.46
 1531.93    38.4  1929.5   43.49 2735.53   46.96 2839.06   48.67 2908.02   51.58
#Mann= 3 , 0 , 0
       0      .1       0 1145.66     .04       0 1347.88     .08       0
#XS Ineff= 2 , 0
         1026.32   43.26
Permanent Ineff=
       F       F
Bank Sta=1145.66,1347.88
XS Rating Curve= 0 ,0
Exp/Cntr=0.3,0.1

Type RM Length L Ch R = 1 ,26052.87,307.33,219.42,180.38
XS GIS Cut Line= 6
1632643.31203349714164.2990341781631638.84973682714032.946272284
 1631376.1442131714156.572401121 1631275.6979834714311.105062127
1630943.45276222714751.5231460631630719.38040371715678.719112203
#Sta/Elev= 30
       0   48.91    35.3   49.99  162.37   48.66  183.55   50.23  211.79    47.8
  232.97   48.38  254.15   46.72  338.86    44.8  522.41   42.75  705.96   42.59
  861.27   39.54  931.87    40.5 1067.17   38.92    1160   40.48 1206.42   37.49
 1229.63   39.12 1291.52   39.68 1303.35   38.73 1320.05   34.39 1335.27   34.38
 1387.89   31.35 1403.54   34.57 1420.23   39.01 1453.63   39.33 1540.27   32.66
 1575.34   38.48 1592.88   36.93 1645.49   39.54  2838.7   46.54 2993.22   48.61
#Mann= 3 , 0 , 0
       0      .1       0 1335.27     .04       0 1403.54     .08       0
Bank Sta=1335.27,1403.54
XS Rating Curve= 0 ,0
Exp/Cntr=0.3,0.1

Type RM Length L Ch R = 1 ,25833.45,223.15,309.41,218.09
XS GIS Cut Line= 6
1632527.41253769714002.0397401011631662.02963595713893.866877362
1631175.25175376713947.9533087461631136.61858848714179.752300277
1630943.45276222714465.6377231481630595.75427489715980.057801202
#Sta/Elev= 30
       0   48.74  134.04   43.81  437.38   43.02  684.28   39.49   867.7   39.73
  977.77   38.15  998.89   39.82 1020.02   37.58 1182.01   37.62 1273.57    35.5
 1358.09   37.68 1404.47   35.36 1482.53   38.14 1501.77   33.87 1510.92   32.23
 1511.62   30.34 1521.76   30.06  1561.9    33.7 1613.79   38.66 1664.47   31.81
 1723.61   37.21 1765.85   33.94 1782.75   37.44 1816.54   39.76 1992.19   39.53
 2329.75   43.52 3105.42   47.17 3198.79   49.28 3349.61   55.73 3486.07   58.62
#Mann= 3 , 0 , 0
       0      .1       0 1501.77     .04       0  1561.9     .08       0
Bank Sta=1501.77,1561.9
XS Rating Curve= 0 ,0
Exp/Cntr=0.3,0.1

Type RM Length L Ch R = 1 ,25524.04,309.94,361.58,520.55
XS GIS Cut Line= 6
 1632620.1321343713947.9533087461631708.38943426713808.873913825
1630989.81256053713909.3201434911630835.27989951714102.485969767
 1630657.5673393715168.7613308281630402.58844864715980.057801202
#Sta/Elev= 30
       0   48.41   63.73    47.6   99.13   44.44  460.26   43.21  757.66   39.07
 1056.58   38.38 1106.06    39.8 1148.47   38.58 1233.29   39.65 1367.58   35.81
 1409.99   36.27  1452.4   38.74  1473.6   37.47 1586.69   37.57 1701.64   35.76
 1791.29   37.27 1818.18   34.56 1864.06    27.7 1874.88    27.8 1880.93   32.45
 1889.59   34.83 1902.33   35.01 1916.52    32.1 1930.71      31  1966.2   37.27
 1973.29   37.52 2626.17   43.12 3343.08   46.76 3585.22      53 3826.63   57.05
#Mann= 3 , 0 , 0
       0     .08       0 1818.18     .04       0 1889.59     .08       0
Bank Sta=1818.18,1889.59
XS Rating Curve= 0 ,0
Exp/Cntr=0.3,0.1

Type RM Length L Ch R = 1 ,25162.46,147.24,186.87,217.38
XS GIS Cut Line= 5
1632712.85173091713909.3201434911631739.29596646713692.974418059
1630927.99949612713716.1543171851630286.68895285713940.226675689
1629884.90403418713940.226675689
#Sta/Elev= 30
       0   47.21   78.88   45.92  100.39   47.04   172.1   44.39  437.42   44.26
  910.69   38.95 1137.36   37.76 1340.44    39.3 1466.49   37.84  1487.5   36.49
 1753.61   34.75 1831.17   34.51 1853.42   37.19 1934.98   35.43 1972.06   37.45
 2009.13    35.7 2075.86   37.83 2098.11   36.22 2120.36   30.79 2144.59   26.47
 2179.68   31.39 2194.51   33.88 2209.34   34.55    2239   32.67 2305.73   34.72
 2372.47   34.65 2424.37   43.23 2558.26   46.94 2740.26   58.41 2890.04   65.66
#Mann= 3 , 0 , 0
       0     .08       0 2120.36     .04       0 2179.68     .08       0
#XS Ineff= 2 , 0
         1073.19   40.63
Permanent Ineff=
       F       F
Bank Sta=2120.36,2179.68
XS Rating Curve= 0 ,0
Exp/Cntr=0.3,0.1

Type RM Length L Ch R = 1 ,24975.59,94.11,100.66,93.14
XS GIS Cut Line= 3
1632705.12509789713870.6869782061631777.92913175713646.614619747
1630248.05578762 713638.88798669
#Sta/Elev= 30
       0   46.72    21.6   45.61  115.22   45.67  136.83    44.5   460.9   43.49
  547.31   41.85  953.89    38.6 1205.89   39.28 1338.89   37.72  1429.9   39.53
  1506.9   36.61  1618.9   35.27  1821.9    35.2  1849.9   37.63  1884.9   35.79
 1926.91    35.3 1954.91   37.69 2024.91   34.84 2052.91   35.55 2073.91   32.09
 2081.66   30.41 2088.01   27.15 2134.97   26.65 2136.91   31.94 2157.91    34.3
 2220.91   35.17 2276.91    44.7 2304.91   47.02 2458.91    51.8 2483.78   51.71
#Mann= 3 , 0 , 0
       0     .08       0 2073.91     .04       0 2136.91      .1       0
#XS Ineff= 2 , 0
         1430.92   39.76
Permanent Ineff=
       F       F
Bank Sta=2073.91,2136.91
XS Rating Curve= 0 ,0
Exp/Cntr=0.3,0.1