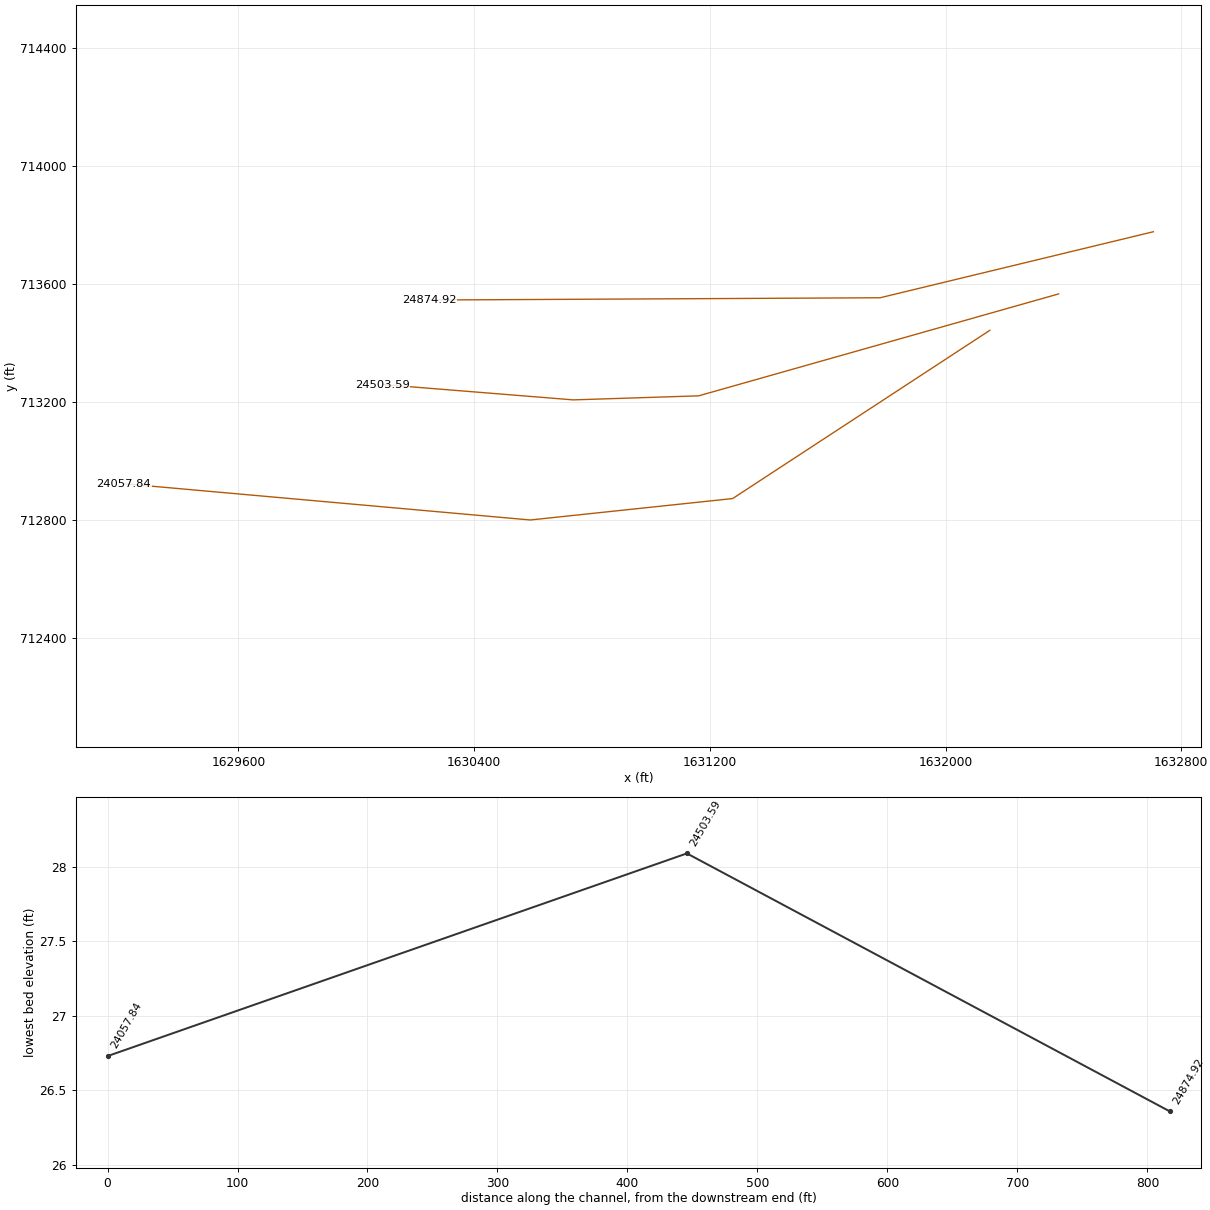
HEC-RAS study LittleElkCreek.prj: Little Elk Creek

--- LittleElkCreek.g01 (geometry) --- (continued)

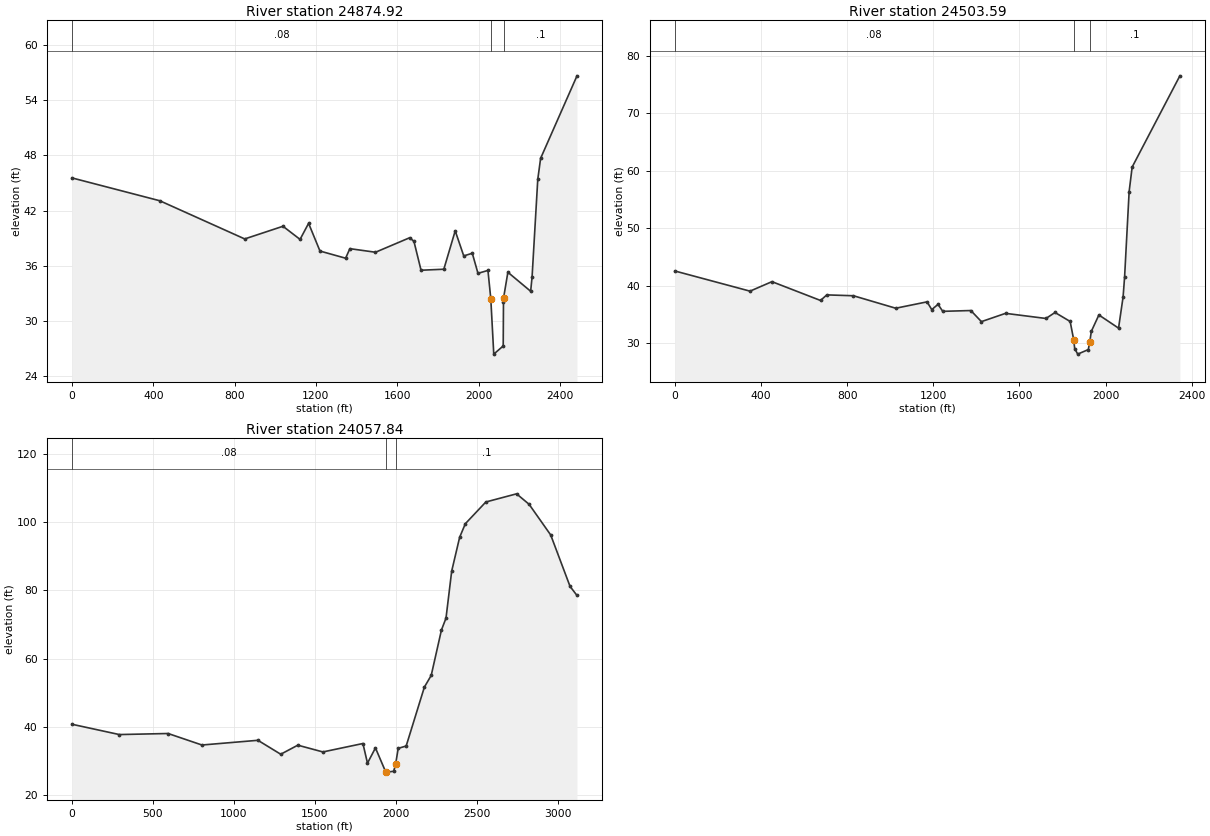
Type RM Length L Ch R = 1 ,24874.92,348.74,371.33,328.88
XS GIS Cut Line= 3
1632705.12509789713777.9673815971631777.92913175713553.895023137
1630248.05578762 713546.16839008
#Sta/Elev= 30
       0   45.56  432.09   43.07  849.78   38.91 1037.89   40.29 1121.89   38.86
 1163.89   40.61 1219.89   37.59  1345.9   36.81  1366.9   37.85  1492.9   37.46
  1660.9   39.04  1681.9   38.65  1716.9    35.5  1828.9   35.61  1884.9   39.79
 1926.91   37.06 1968.91   37.35 1996.91   35.16 2045.91   35.48 2059.91   32.39
 2074.52   26.36 2120.99   27.25 2122.28   32.08 2122.91    32.5 2143.91   35.28
 2255.91   33.21 2262.91   34.76 2290.91    45.4 2304.91   47.69 2483.78   56.68
#Mann= 3 , 0 , 0
       0     .08       0 2059.91     .04       0 2122.91      .1       0
Bank Sta=2059.91,2122.91
XS Rating Curve= 0 ,0
Exp/Cntr=0.3,0.1

Type RM Length L Ch R = 1 ,24503.59,476.9,445.75,432.8
XS GIS Cut Line= 4
1632383.56740624713566.9043237421631162.05285257713221.037281573
1630736.58149116713207.3123989551630088.76703121713259.466952935
#Sta/Elev= 30
       0   42.55  349.21   39.04  451.06   40.69  676.59   37.42  705.69   38.39
  829.37   38.24  1025.8   36.07 1171.31   37.18 1193.13   35.83 1222.23   36.75
 1244.06   35.53 1374.59   35.67 1423.62   33.74 1535.67   35.18 1723.32   34.29
 1765.46   35.33 1835.68   33.77  1852.2   30.58 1856.75   29.05  1870.8   28.09
 1919.96   28.88 1926.98   30.27    1934   32.05 1969.11    34.9 2060.41   32.61
 2081.48   38.03  2088.5   41.51 2109.57   56.36 2123.61   60.62 2345.14   76.48
#Mann= 3 , 0 , 0
       0     .08       0  1852.2     .04       0 1926.98      .1       0
Bank Sta=1852.2,1926.98
XS Rating Curve= 0 ,0
Exp/Cntr=0.3,0.1

Type RM Length L Ch R = 1 ,24057.84,594.6,610.74,602.65
XS GIS Cut Line= 4
1632150.24440165713443.3803801241631277.34186661712872.425262898
1630590.43599133712799.7090187071629210.77028471 712922.89345552
#Sta/Elev= 30
       0   40.75  292.76   37.73  593.87   38.04  802.99   34.67 1148.63   36.05
 1289.42   31.97    1395   34.62 1549.86   32.64 1797.04   35.11 1825.15   29.35
 1874.34   33.82  1937.826.77851 1944.62   26.73 1986.79   26.98 1998.93   29.06
  2014.9   33.69  2064.1   34.38 2176.54   51.63 2218.71   55.04 2281.96   68.35
 2310.07   71.82 2345.21    85.6  2394.4   95.51 2429.54   99.47 2556.04  105.83
  2745.8  108.22  2823.1  105.16 2956.63   96.17  3076.1   81.11 3118.94   78.46
#Mann= 3 , 0 , 0
       0     .08       0  1937.8     .04       0 1998.93      .1       0
Bank Sta=1937.8,1998.93
XS Rating Curve= 0 ,0
Exp/Cntr=0.3,0.1