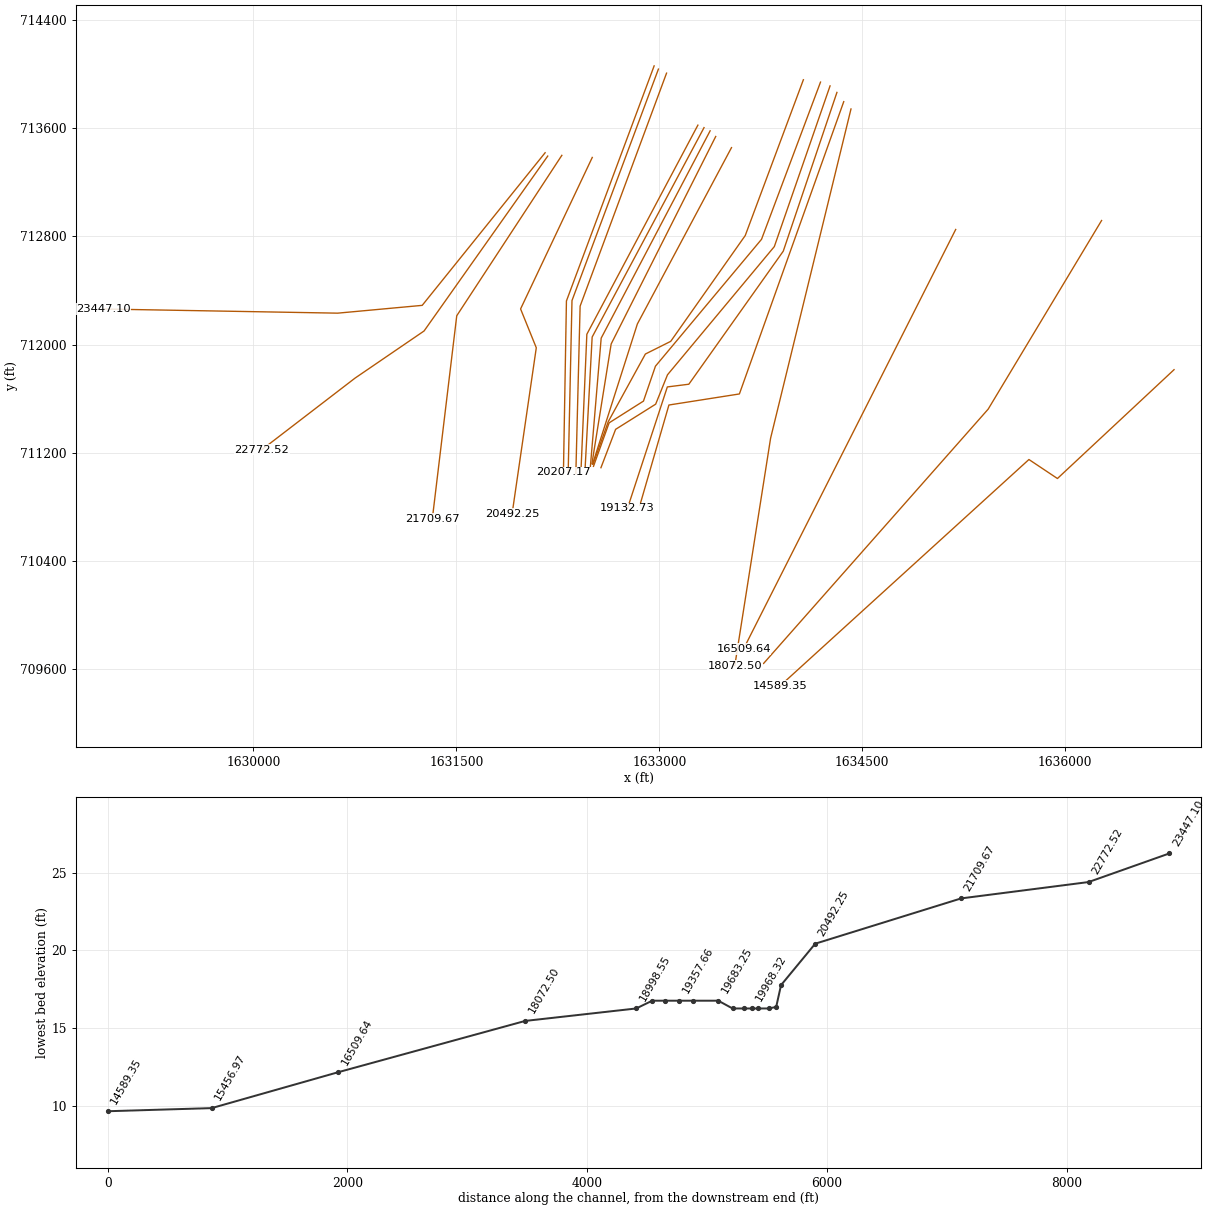
HEC-RAS study LittleElkCreek.prj: Little Elk Creek

--- LittleElkCreek.g01 (geometry) --- (continued)

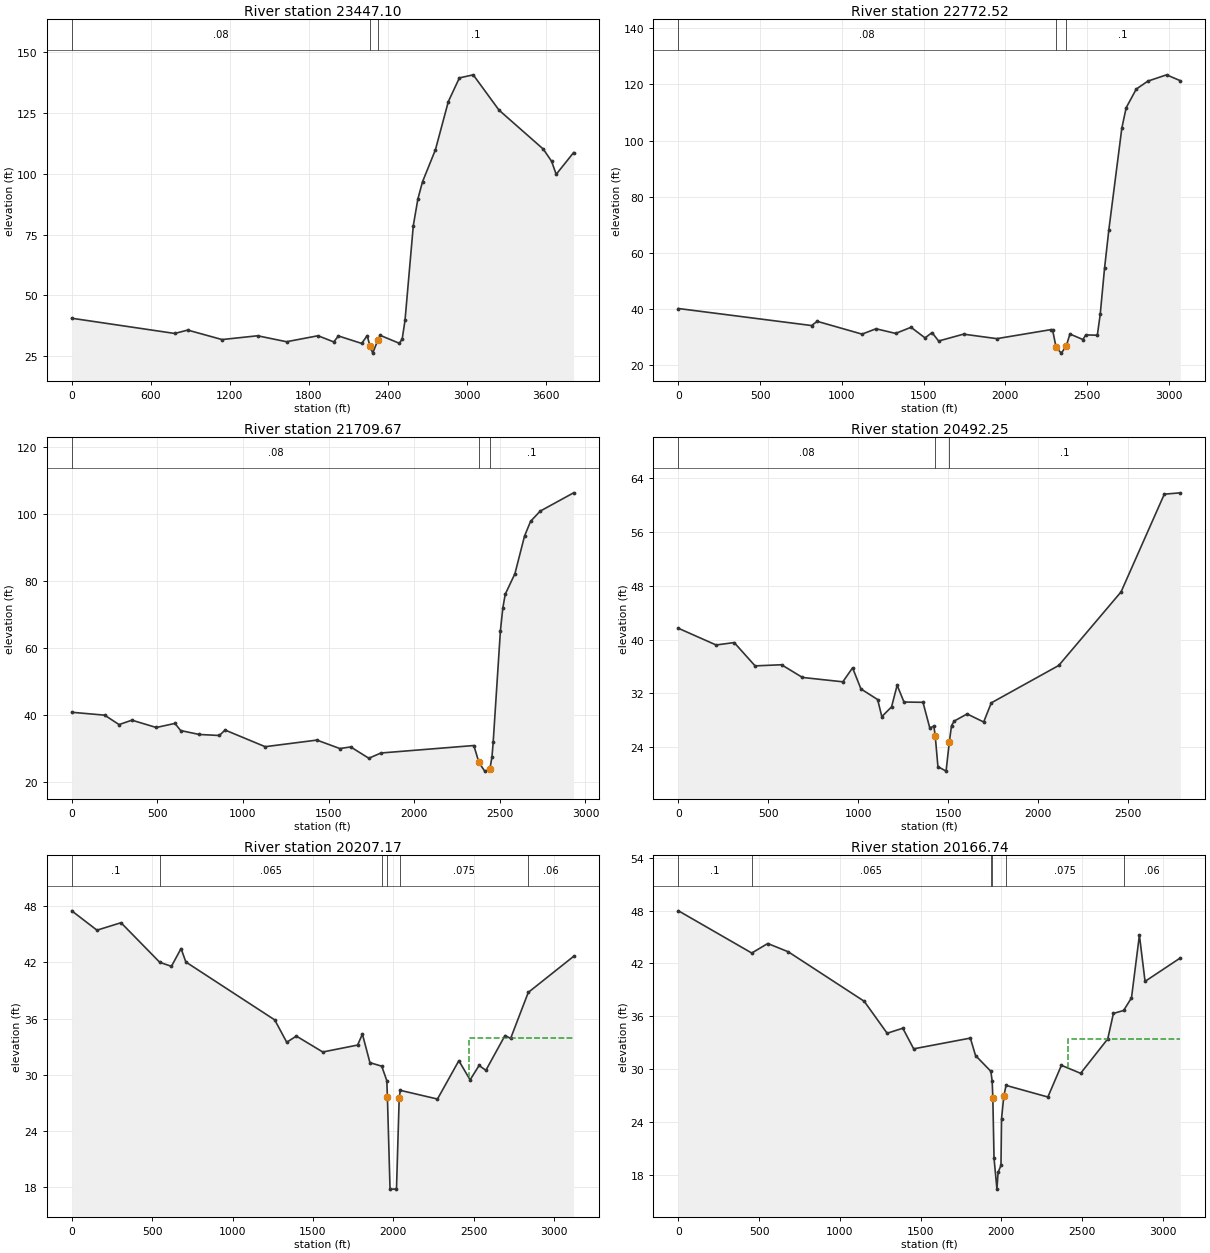
Type RM Length L Ch R = 1 ,23447.10,517.03,674.58,727.17
XS GIS Cut Line= 4
1632155.73435467713418.6755913941631247.14712484712290.490239531
1630622.58345607712232.8777828371628887.45657353712263.611305252
#Sta/Elev= 30
       0   40.58  781.94   34.32  880.81   35.71 1141.45   31.81 1411.09   33.37
 1631.33   30.92 1870.34   33.38 1989.85   30.84 2024.99    33.3 2201.79   30.22
  2243.8   33.43 2263.82   29.32  2285.8   26.23 2325.94   31.78 2341.81   33.56
 2488.83   30.26 2509.83   32.18 2530.84   39.67 2593.84   78.67 2628.85   89.69
 2663.85   96.73 2761.87  109.89 2859.88  129.72 2943.89  139.46 3048.91  140.72
 3244.94  126.19 3580.98  110.17 3643.99  105.17    3679   99.78 3811.14  108.73
#Mann= 3 , 0 , 0
       0     .08       0 2263.82     .04       0 2325.94      .1       0
Bank Sta=2263.82,2325.94
XS Rating Curve= 0 ,0
Exp/Cntr=0.3,0.1

Type RM Length L Ch R = 1 ,22772.52,806.85,1062.8,1002.73
XS GIS Cut Line= 4
1632174.94919035713393.9708026651631260.87200749712101.086859286
1630750.57575989711752.6412945091630060.74290657711222.948209777
#Sta/Elev= 30
       0   40.25  814.42    34.2  848.71    35.7 1123.04   31.15 1208.77   33.05
 1328.78    31.4 1423.08   33.58 1508.81   29.81 1551.68    31.7 1591.85    28.7
 1744.42   31.14 1947.85   29.54 2280.72   32.76 2289.54   32.56 2310.96   26.42
  2342.5   24.39 2372.07   26.77 2395.45   31.18 2474.88   29.23 2492.54   30.87
 2563.14   30.76 2580.79   38.18 2607.27   54.56 2633.75   68.33 2713.18  104.44
 2739.65  111.68 2801.43   118.3 2872.04  121.12 2986.77  123.37 3071.04  121.28
#Mann= 3 , 0 , 0
       0     .08       0 2310.96     .04       0 2372.07      .1       0
Bank Sta=2310.96,2372.07
XS Rating Curve= 0 ,0
Exp/Cntr=0.3,0.1

Type RM Length L Ch R = 1 ,21709.67,946.77,1217.47,1109.45
XS GIS Cut Line= 3
1632279.25829829713399.460755721 1631502.4299417712213.630896822
1631321.77753261710711.283670425
#Sta/Elev= 30
       0   40.88  192.47   40.01  276.15   37.21  351.47   38.52  493.73   36.34
  602.52   37.56  635.99   35.43  744.78   34.26  861.93   33.96  895.41   35.58
 1129.72   30.62 1431.72   32.59 1565.68   30.07 1629.14   30.55 1734.89   27.18
  1805.4   28.74 2348.28   30.97 2378.06   25.93 2411.74   23.34 2441.65   23.88
 2454.04   27.52 2461.09   31.87  2503.4   65.13  2517.5   71.93  2531.6   76.05
    2588   82.14 2644.41   93.39 2679.66   97.77 2736.06  100.82 2930.81  106.26
#Mann= 3 , 0 , 0
       0     .08       0 2378.06     .04       0 2441.65      .1       0
Bank Sta=2378.06,2441.65
XS Rating Curve= 0 ,0
Exp/Cntr=0.3,0.1

Type RM Length L Ch R = 1 ,20492.25,308.63,285.08,248.26
XS GIS Cut Line= 4
1632504.23263857713383.9090960031631974.31704521712264.164054871
1632090.43027879711977.0362224581631911.38443565710747.911617294
#Sta/Elev= 30
       0   41.68   209.1    39.2  309.77   39.56  425.94   36.09  573.08   36.26
  689.24   34.37  913.83   33.72  968.04    35.8  1014.5   32.66 1107.44   31.08
 1130.67   28.54 1184.88   29.99 1215.86   33.21 1253.91   30.71 1359.62   30.67
 1397.37   26.86 1420.02   27.12 1427.57   25.73 1442.67    21.1 1487.98   20.43
  1506.1   24.78 1518.18   27.19 1533.28   27.88 1605.11   28.94 1697.07   27.74
 1739.52   30.59 2114.43   36.15 2461.06    47.1 2701.57   61.64 2790.63   61.84
#Mann= 3 , 0 , 0
       0     .08       0 1427.57     .04       0  1506.1      .1       0
Bank Sta=1427.57,1506.1
XS Rating Curve= 0 ,0
Exp/Cntr=0.3,0.1

Type RM Length L Ch R = 1 ,20207.17,42.39,40.44,39.6
BEGIN DESCRIPTION:
underwater portion from hec2 section 220.03
END DESCRIPTION:
XS GIS Cut Line= 3
1632961.59876589714060.6971054671632313.25038508712322.807177424
1632291.11165988 711056.15582858
#Sta/Elev= 30
       0   47.52   156.9   45.45  306.32   46.25  547.8642.00952  620.11   41.59
  679.88   43.49  709.77   42.05 1262.64   35.86 1337.36   33.47 1397.13   34.13
  1561.5   32.43 1778.16   33.17 1808.05   34.34 1854.89   31.29 1928.2930.91206
 1959.91   29.36 1963.51   27.64    1980   17.77    2020   17.77 2036.92   27.51
 2043.92   28.33 2274.96    27.4 2407.98    31.5 2477.99   29.45 2533.99   30.99
    2576   30.47 2695.02   34.19 2730.02   33.88 2839.8338.79966 3121.73   42.65
#Mann= 6 ,-1 , 0
       0      .1       0  547.86    .065       0 1928.29      .1       0
 1959.91     .04       0 2043.92    .075       0 2839.83     .06       0
#XS Ineff= 1 ,-1
 2472.92 3121.73 33.9686
Permanent Ineff=
       F
Bank Sta=1963.51,2036.92
XS Rating Curve= 0 ,0
Exp/Cntr=0.5,0.3

Type RM Length L Ch R = 1 ,20166.74,63.84,61.57,60.13
BEGIN DESCRIPTION:
underwater portion from hec2 section 220.01
END DESCRIPTION:
XS GIS Cut Line= 3
1632993.22551619714036.9770427351632354.36516045712325.969852433
1632325.90108518711043.505128458
#Sta/Elev= 30
       0   47.97  453.9443.17752  552.93   44.26  679.96   43.32 1150.69    37.7
 1292.66   34.07  1389.8   34.64 1457.05    32.3 1808.23   33.52 1840.39   31.54
 1935.4629.74357 1943.54    28.6 1947.55   26.73    1955   19.87    1973   16.37
    1980   18.27    1998   19.07 2001.43   24.36 2015.43   26.91 2029.44   28.15
  2288.5   26.83 2372.52   30.43 2491.55   29.52 2659.59   33.43  2694.6   36.32
 2757.83 36.6554 2806.63   38.09 2855.64    45.2 2890.65   39.96 3109.17   42.62
#Mann= 6 ,-1 , 0
       0      .1       0  453.94    .065       0 1935.46      .1       0
 1943.54     .04       0 2029.44    .075       0 2757.83     .06       0
#XS Ineff= 1 ,-1
 2415.16 3109.17 33.4254
Permanent Ineff=
       F
Bank Sta=1947.55,2015.43
XS Rating Curve= 0 ,0
Exp/Cntr=0.5,0.3

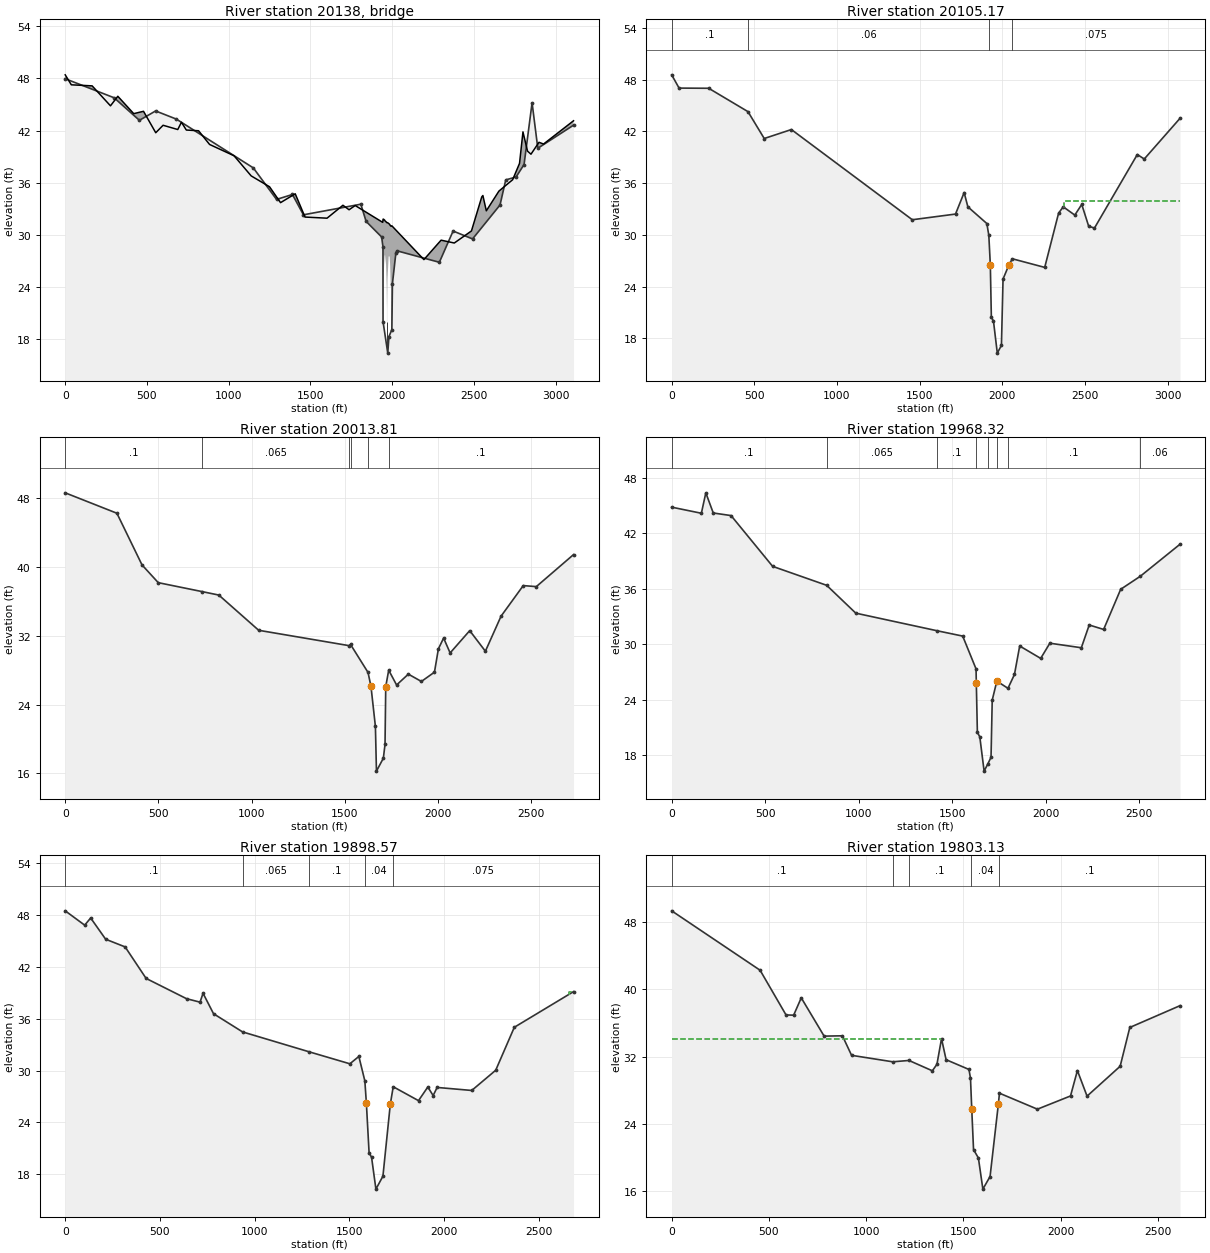
Type RM Length L Ch R = 3 ,20138   ,,,
BEGIN DESCRIPTION:
Thiokol Road Crossing  Geometry from HEC2 Section 220.02,  Top of Road from Lidar.
END DESCRIPTION:
Bridge Culvert--1,0,-1,-1, 0
Deck Dist Width WeirC Skew NumUp NumDn MinLoCord MaxHiCord MaxSubmerge Is_Ogee
20,20,2.6,0, 60, 60, , , 0.95, 0, 0,0,,
       0   37.42  164.64  276.89  321.79  419.08  478.95  553.78  598.68  688.48
  710.93  740.87   815.7  883.06 1032.73  1137.5 1249.75  1317.1  1406.9 1466.77
 1601.47 1698.76 1736.18 1773.59 1941.97  1944.3  1944.3  1946.3  1953.3  1956.2
  1962.3  1966.3    1968    1968  1969.3  1969.3  1971.3  1978.3  1984.3  1987.3
  1991.3    1993    1993 1997.98 2194.05 2299.08 2379.72 2484.74 2547.76 2554.76
 2575.76 2652.78  2736.8 2778.81 2799.82 2827.83 2848.83 2897.84 2925.85 3109.17
   48.42   47.27   47.15   44.85   45.95   43.95   44.22   41.75   42.61   42.12
   42.96   42.06   41.98    40.4    39.1   36.78   35.53    33.7   34.72   32.04
   31.91    33.4   32.88   33.37   31.43    31.8    31.8    31.8    31.7    31.6
    31.5    31.4    31.4    31.4    31.4    31.4    31.4    31.3    31.2    31.1
      31      31      31   31.03   27.14   29.38   29.05   30.44   34.36   34.52
   32.76   35.03   36.34   38.22   41.85   39.63   39.28   40.65   40.45   43.13
                                                                                
                                                                                
                                            31.8    21.4    24.8    27.5    27.7
    26.6      24    21.4      20      20    21.6    24.8    27.5    27.5    26.6
      24    24.1      31
                                                                                
       0   37.42  164.64  276.89  321.79  419.08  478.95  553.78  598.68  688.48
  710.93  740.87   815.7  883.06 1032.73  1137.5 1249.75  1317.1  1406.9 1466.77
 1601.47 1698.76 1736.18 1773.59 1941.97  1944.3  1944.3  1946.3  1953.3  1956.2
  1962.3  1966.3    1968    1968  1969.3  1969.3  1971.3  1978.3  1984.3  1987.3
  1991.3    1993    1993 1997.98 2194.05 2299.08 2379.72 2484.74 2547.76 2554.76
 2575.76 2652.78  2736.8 2778.81 2799.82 2827.83 2848.83 2897.84 3002.87 3079.89
   48.42   47.27   47.15   44.85   45.95   43.95   44.22   41.75   42.61   42.12
   42.96   42.06   41.98    40.4    39.1   36.78   35.53    33.7   34.72   32.04
   31.91    33.4   32.88   33.37   31.43    31.8    31.8    31.8    31.7    31.6
    31.5    31.4    31.4    31.4    31.4    31.4    31.4    31.3    31.2    31.1
      31      31      31   31.03   27.14   29.38   29.05   30.44   34.36   34.52
   32.76   35.03   36.34   38.22   41.85   39.63   39.28   40.65   41.43   43.13
                                                                                
                                                                                
                                            31.8    21.4    24.8    27.5    27.7
    26.6      24    21.4      20      20    21.6    24.8    27.5    27.5    26.6
      24    24.1      31
                                                                                
Pier Skew, UpSta & Num, DnSta & Num=  ,1968.8, 2 ,1968.8, 2 , 0 , 0 , 0 ,,
       2       2
       0      20
       2       2
       0      20
BR Coef=-1 , 1 , 0 ,, 0 ,,,0.8,0,0.5,0,
WSPro=,,,, 1 ,,,, 0 ,,,, 0 ,,,,-1 ,-1 ,-1 , 0 , 0 , 0 , 0 , 0
BR U #Sta/Elev= 30
       0   47.97  298.88   45.78  453.94  43.178  552.93   44.26  679.96   43.32
 1150.69    37.7 1292.66   34.07  1389.8   34.64 1457.05    32.3 1808.23   33.52
 1840.39   31.54 1935.46  29.744 1943.54    28.6    1944      20    1973   16.37
    1980   18.27    1998   19.07 2001.43   24.36 2022.44   27.89 2029.44   28.15
  2288.5   26.83 2372.52   30.43 2491.55   29.52 2659.59   33.43  2694.6   36.32
 2757.83  36.655 2806.63   38.09 2855.64    45.2 2890.65   39.96 3109.17   42.62
BR U #Mann= 6
       0      .1  453.94    .065 1935.46      .1 1943.54    .035 2029.44    .075
 2757.83     .06
BR U Banks=1943.54,2022.44
BR D #Sta/Elev= 30
       0   48.57    44.8   47.03  223.99   47.01  461.61  44.297  559.96   41.18
  619.69   42.41  724.22   42.22 1455.91   31.75 1717.22   32.41 1769.49   34.91
 1791.88   33.25 1906.79   31.31 1918.71   29.94 1927.79   26.53    1934   20.47
    1947   19.97    1970   16.27    1995   17.17 2004.82   24.87 2060.84   27.22
  2256.9   26.22 2340.93   32.52 2368.93   33.25 2438.96   32.29 2480.97   33.53
 2522.98   30.99 2557.99   30.79 2817.07   39.32 2859.09    38.8 3075.34   43.52
BR D #Mann= 4
       0      .1  461.61     .06 1918.71    .035 2060.84    .075
BC Design=,, 0 ,, 0 ,,,,,,
BC Use User HTab Curves=0
BC User HTab FreeFlow(D)= 0

Type RM Length L Ch R = 1 ,20105.17,119.24,91.35,53.85
BEGIN DESCRIPTION:
underwater portion from hec2 section 219.2
END DESCRIPTION:
XS GIS Cut Line= 3
1633053.31634168714006.9316299861632414.45598601712284.855077058
1632382.82923573711046.667803496
#Sta/Elev= 30
       0   48.57    44.8   47.03  223.99   47.01  461.6144.29692  559.96   41.18
  724.22   42.22 1455.91   31.75 1717.22   32.41 1769.49   34.91 1791.88   33.25
 1906.79   31.31 1918.71   29.94 1927.79   26.53    1934   20.47    1947   19.97
    1970   16.27    1995   17.17 2004.82   24.87 2039.83   26.48 2060.84   27.22
  2256.9   26.22 2340.93   32.52 2368.93   33.25 2438.96   32.29 2480.97   33.53
 2522.98   30.99 2557.99   30.79 2817.07   39.32 2859.09    38.8 3075.34   43.52
#Mann= 4 ,-1 , 0
       0      .1       0  461.61     .06       0 1918.71     .04       0
 2060.84    .075       0
#XS Ineff= 1 ,-1
 2375.05 3075.34  33.907
Permanent Ineff=
       F
Bank Sta=1927.79,2039.83
XS Rating Curve= 0 ,0
Exp/Cntr=0.5,0.3

Type RM Length L Ch R = 1 ,20013.81,46.33,45.49,39.6
BEGIN DESCRIPTION:
underwater portion from hec2 section 219.2
END DESCRIPTION:
XS GIS Cut Line= 3
 1633284.9323552713622.6523343181632464.18099193712077.003781512
1632422.24479085711100.489385739
#Sta/Elev= 30
       0   48.58   277.4   46.21  412.14   40.21  499.32   38.15  735.3237.10884
  824.27   36.71 1038.26   32.62 1521.92 30.8424 1530.9230.97684 1624.76   27.73
 1640.61   26.11 1664.39   21.46    1670   16.27    1707   17.77    1716   19.37
 1719.87   26.08 1735.72   27.99 1778.07   26.27 1841.13   27.53 1911.19   26.68
 1981.26   27.76 2002.28   30.46  2030.3   31.72 2065.33   29.99 2170.43   32.58
  2254.5   30.19 2338.58   34.26 2457.69   37.81 2527.75   37.69 2727.45   41.41
#Mann= 6 ,-1 , 0
       0      .1       0  735.32    .065       0 1521.92      .1       0
 1530.92     .06       0 1624.76     .04       0 1735.72      .1       0
Bank Sta=1640.61,1719.87
XS Rating Curve= 0 ,0
Exp/Cntr=0.3,0.1

Type RM Length L Ch R = 1 ,19968.32,63.68,69.75,65.72
BEGIN DESCRIPTION:
underwater portion from hec2 section 219.2
END DESCRIPTION:
XS GIS Cut Line= 3
1633330.39456381713604.2607564931632503.39206424712056.252925202
1632451.88535023711095.669582248
#Sta/Elev= 30
       0   44.81  158.73   44.15  182.54   46.36  222.22   44.18  317.45    43.9
  539.67   38.41  828.4236.36083   984.1   33.35 1418.01   31.45 1555.52   30.87
 1626.94   27.32 1628.28   25.81    1634   20.47    1647   19.97    1670   16.27
 1690.5317.07537    1707   17.77 1713.35   23.95 1738.05      26 1797.5825.22385
 1832.18   26.72 1860.22    29.8 1972.38   28.46 2021.45    30.1 2189.69   29.61
 2231.75   32.07 2308.86   31.59 2399.99   35.93 2504.8237.33768 2717.02    40.8
#Mann= 8 ,-1 , 0
       0      .1       0  828.42    .065       0 1418.01      .1       0
 1626.94     .04       0 1690.53    .075       0 1738.05      .1       0
 1797.58      .1       0 2504.82     .06       0
Bank Sta=1628.28,1738.05
XS Rating Curve= 0 ,0
Exp/Cntr=0.3,0.1

Type RM Length L Ch R = 1 ,19898.57,84.19,95.44,77.21
BEGIN DESCRIPTION:
underwater portion from hec2 section 219.1
END DESCRIPTION:
XS GIS Cut Line= 3
1633375.54711138713580.7595585581632570.09206373712048.195773393
1632490.37125693711099.793072239
#Sta/Elev= 30
       0   48.51   102.8   46.85  134.43   47.68  213.51   45.22  316.31   44.33
  427.02   40.68  640.54   38.33  711.71   37.93  727.52   38.96  782.88   36.59
  936.1234.48354 1288.6832.16962  1502.5   30.79 1549.94   31.64 1581.57   28.81
 1589.48   26.28    1604   20.47    1617   19.97    1640   16.27    1677   17.77
 1716.01   26.12 1731.33   28.13  1864.8   26.52 1913.97    28.1 1942.07   27.11
 1963.14   28.05 2145.78    27.7 2272.23   30.04 2370.57   35.02 2683.07   39.15
#Mann= 5 ,-1 , 0
       0      .1       0  936.12    .065       0 1288.68      .1       0
 1581.57     .04       0 1731.33    .075       0
#XS Ineff= 1 ,-1
 2656.81 2683.0739.14881
Permanent Ineff=
       F
Bank Sta=1589.48,1716.01
XS Rating Curve= 0 ,0
Exp/Cntr=0.3,0.1

Type RM Length L Ch R = 1 ,19803.13,113.45,119.88,137.49
BEGIN DESCRIPTION:
unnderwater portion from hec2 section 219.1
END DESCRIPTION:
XS GIS Cut Line= 3
1633416.73184422713538.7799322461632643.90756778712005.113151163
1632501.77762793711120.326650634
#Sta/Elev= 30
       0   49.34  454.63   42.28  587.89   36.97  627.08   36.94  666.27      39
  783.85   34.45  877.91   34.49  924.94   32.17 1136.62    31.4 1219.99   31.56
 1340.38   30.33  1363.9   31.11 1387.41   34.15 1410.93   31.65 1528.51   30.49
 1536.35   29.44 1542.76   25.81    1552   20.97    1577   19.97    1600   16.27
    1637   17.77 1679.59   26.36 1685.28   27.67 1880.44   25.77  2050.6   27.34
 2086.04   30.36 2135.67   27.32 2305.83   30.87 2355.46   35.48 2613.52   38.07
#Mann= 5 ,-1 , 0
       0      .1       0 1136.62     .06       0 1219.99      .1       0
    1541     .04       0 1685.28      .1       0
#XS Ineff= 2 , 0
         1386.49   34.13
Permanent Ineff=
       F       F
Bank Sta=1542.76,1679.59
XS Rating Curve= 0 ,0
Exp/Cntr=0.3,0.1

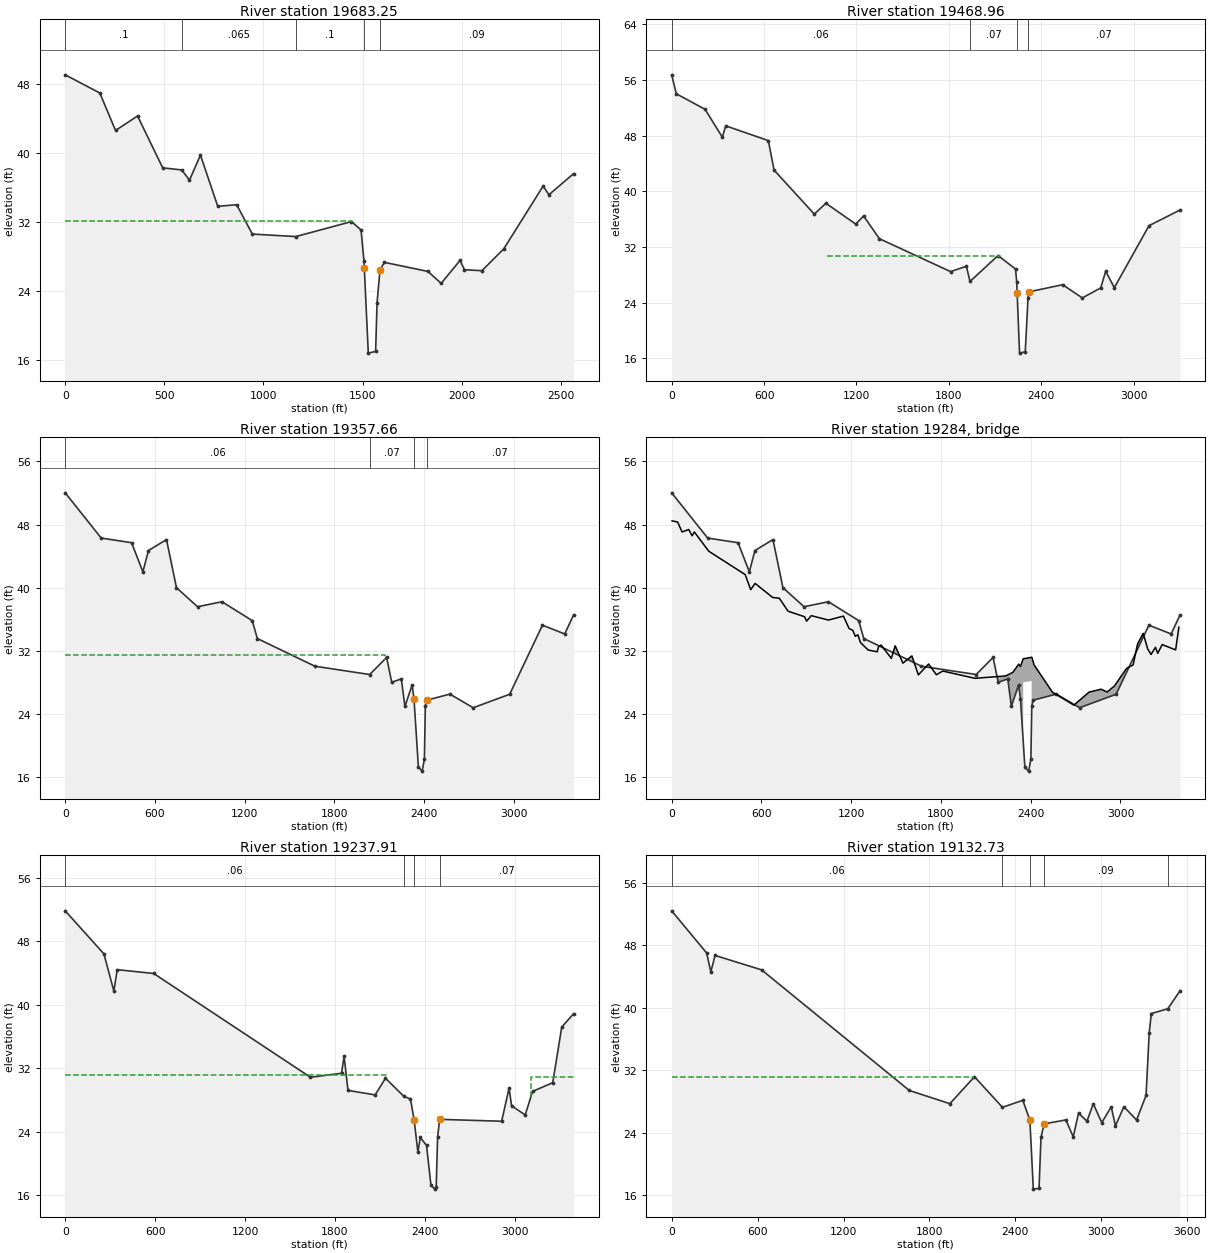
Type RM Length L Ch R = 1 ,19683.25,238.78,214.29,122.87
BEGIN DESCRIPTION:
underwater portion from hec2 section 218
END DESCRIPTION:
XS GIS Cut Line= 3
1633533.44241612713456.5394221691632837.60347778712152.915238291
1632506.86521696711117.747434959
#Sta/Elev= 30
       0   49.08  174.57   46.97  253.91   42.62     365    44.3  491.96   38.28
  588.0238.03754  626.85   36.85  682.39   39.76  769.67   33.81  864.89      34
  944.24   30.59 1163.4830.30281 1444.13   32.04 1492.41   31.07 1507.11   27.48
 1509.03   26.62    1529   16.77    1566   16.97 1573.24   22.62 1587.94   26.41
 1609.99   27.31 1830.44   26.25 1896.58   24.87 1992.11   27.54 2014.16   26.45
 2102.34   26.34 2212.57   28.88 2410.99   36.16 2440.38   35.16 2564.43    37.6
#Mann= 5 ,-1 , 0
       0      .1       0  588.02    .065       0 1163.48      .1       0
 1507.11     .04       0 1587.94     .09       0
#XS Ineff= 2 , 0
         1445.95   32.08
Permanent Ineff=
       F       F
Bank Sta=1509.03,1587.94
XS Rating Curve= 0 ,0
Exp/Cntr=0.3,0.1

Type RM Length L Ch R = 1 ,19468.96,109.91,111.3,162.56
BEGIN DESCRIPTION:
underwater portion from hec2 section 218
END DESCRIPTION:
XS GIS Cut Line= 6
1634064.83258772713958.2248785051633635.10831478712806.784198508
1633084.17975976712024.4656503951632896.86405107711930.807796031
1632622.32499713711430.5983125571632509.44772673711115.097089708
#Sta/Elev= 30
       0   56.75   29.89   54.03  216.68    51.8  328.75    47.8  351.17   49.42
  627.61    47.3  664.97   43.06  926.48   36.74  1001.2    38.3 1195.46   35.31
 1246.14   36.48 1348.88   33.21 1811.21   28.48 1913.95   29.25 1937.34 27.0667
 2119.42   30.79 2232.82   28.85 2240.64   27.01 2243.64   25.34    2259   16.77
    2296   16.97 2314.31   24.72 2318.91   25.57 2539.02    26.6 2666.78    24.7
 2786.55   26.15 2818.49   28.54 2874.39   26.17 3099.71   35.08 3300.98   37.33
#Mann= 4 ,-1 , 0
       0     .06       0 1937.34     .07       0 2240.64     .04       0
 2314.31     .07       0
#XS Ineff= 1 ,-1
 1009.45 2129.5830.77467
Permanent Ineff=
       F
Bank Sta=2243.64,2318.91
XS Rating Curve= 0 ,0
Exp/Cntr=0.5,0.3

Type RM Length L Ch R = 1 ,19357.66,97.09,119.75,160.62
BEGIN DESCRIPTION:
underwater portion from hec2 section 217.4
END DESCRIPTION:
XS GIS Cut Line= 6
1634191.48445137713940.8816475721633755.39585179712778.730916515
 1632971.2261837711840.830144435 1632882.6545018711582.731134966
1632628.78662363711421.9481454791632513.13570136 711100.38216649
#Sta/Elev= 30
       0   52.03  240.72    46.3  443.83   45.71  519.06   42.02  556.67   44.72
  677.04   46.11  743.79   40.01  884.81    37.6  1048.1   38.23 1250.03   35.84
 1284.26   33.57 1669.36   30.06 2035.39 29.0107 2148.59   31.17 2182.82   28.02
  2246.7   28.46 2270.79   24.97 2318.96   27.68 2331.69   25.89    2361   17.27
    2386   16.77    2401   18.27 2407.27   24.99  2415.3   25.75 2571.68   26.53
 2727.09    24.8 2971.18   26.51 3190.15   35.26 3338.93   34.15 3397.98   36.55
#Mann= 4 ,-1 , 0
       0     .06       0 2035.39     .07       0 2331.69     .04       0
  2415.3     .07       0
#XS Ineff= 1 ,-1
       0 2134.53 31.4944
Permanent Ineff=
       F
Bank Sta=2331.69,2415.3
XS Rating Curve= 0 ,0
Exp/Cntr=0.5,0.3

Type RM Length L Ch R = 3 ,19284   ,,,
BEGIN DESCRIPTION:
Thiokol/Triumph Rd , Top of road from LIDAR. Geometry of bridge from hec2 model section 217.2
END DESCRIPTION:
Bridge Culvert--1,0,-1,-1, 0
Deck Dist Width WeirC Skew NumUp NumDn MinLoCord MaxHiCord MaxSubmerge Is_Ogee
46,20,2.6,0, 60, 60, , , 0.95, 0, 0,0,,
    2.63   39.82   69.57   114.2  136.51  151.39  248.09  491.49  528.24  557.64
  675.23  719.33  778.13  888.37  902.06   932.8 1048.06 1147.96 1186.38 1210.41
 1227.61  1244.8    1262 1313.58 1373.77 1382.37 1399.56 1468.34 1494.13 1545.72
  1605.9 1648.89 1717.67 1769.26 1812.25 2027.19 2233.06 2281.31 2319.91 2331.11
    2350 2407.39 2422.65 2545.42 2688.72 2790.07 2870.74 2911.07 2959.48 3040.15
 3084.61 3114.51  3151.9 3181.81 3204.24 3234.14  3249.1    3279 3368.73 3390.41
   48.48   48.33   47.07   47.38   46.58   47.07   44.63   41.67   39.76   40.55
   38.77   38.68   37.03   36.33   35.77   36.47   35.91   36.41   34.83   34.61
   33.86   34.04   33.06   32.11   31.89   32.51   32.75   31.05   32.65   30.45
   31.37   28.96   30.35   28.98   29.45   28.53   28.83    29.3   30.33   30.03
      31    31.2   30.23   26.77   25.13   26.78   27.15   26.79   27.56   29.77
   30.24   32.89   34.22   32.26   31.55   32.46    31.7    32.8   32.13      35
                                                                                
                                                                                
                                                                                
                                                                                
      28    28.2
                                                                                
       0   37.19   81.82  111.57   156.2  178.51  193.39  290.09  533.49  570.24
  599.64  717.23  761.33  820.13  930.37  944.06   974.8 1090.06 1189.96 1228.38
 1252.41 1269.61  1286.8    1304 1355.58 1415.77 1441.56 1510.34 1536.13 1587.72
  1647.9 1690.89 1759.67 1811.26 1854.25 2069.19 2275.06 2323.31 2361.91 2373.11
 2424.68 2482.73 2489.38 2587.42 2730.72 2832.07 2912.74 2953.07 3001.48 3082.15
 3126.61 3156.51  3193.9 3223.81 3246.24 3276.14  3291.1    3321 3410.73 3432.41
   50.04   48.59   48.33   47.07   47.38   46.58   47.07   44.63   41.67   39.76
   40.55   38.77   38.68   37.03   36.33   35.77   36.47   35.91   36.41   34.83
   34.61   33.86   34.04   33.06   32.11   31.89   32.75   31.05   32.65   30.45
   31.37   28.96   30.35   28.98   29.45   28.53   28.83    29.3   30.33   30.03
      31    31.2    29.6   26.77   25.13   26.78   27.15   26.79   27.56   29.77
   30.24   32.89   34.22   32.26   31.55   32.46    31.7    32.8   32.13      35
                                                                                
                                                                                
                                                                                
                                                                                
      28    28.2
                                                                                
BR Coef=-1 , 0 , 0 ,, 0 ,,,0.8,0,,0,
WSPro=,,,, 1 ,,,, 0 ,,,, 0 ,,,,-1 ,-1 ,-1 , 0 , 0 , 0 , 0 , 0
BR U #Sta/Elev= 30
       0   52.03  240.72    46.3  443.83   45.71  519.06   42.02  556.67   44.72
  677.04   46.11  743.79   40.01  884.81    37.6  1048.1   38.23 1250.03   35.84
 1284.26   33.57 1669.36   30.06 2035.39  29.011 2148.59   31.17 2182.82   28.02
  2246.7   28.46 2270.79   24.97 2318.96   27.68 2331.69   25.89    2361   17.27
    2386   16.77    2401   18.27 2407.27   24.99  2415.3   25.75 2571.68   26.53
 2727.09    24.8 2971.18   26.51 3190.15   35.26 3338.93   34.15 3397.98   36.55
BR U #Mann= 4
       0     .06 2035.39     .07 2331.69    .035  2415.3     .07
BR D #Sta/Elev= 30
       0   51.86  258.33   46.43  324.76   41.74  346.91   44.44  590.48   43.96
 1636.88   30.87    1844   31.38 1861.26   33.52 1887.15   29.22 2068.39   28.65
 2137.43   30.75 2260.41  28.457 2304.26   28.14 2328.94   25.45 2353.63   21.46
 2370.08   23.28 2411.22   22.28    2441   17.27    2466   16.77    2476   17.07
 2485.27   23.31  2498.9   25.57 2912.79   25.33  2962.4   29.51 2978.94   27.28
 3069.89   26.12 3118.97   29.09 3253.86   30.19 3313.81   37.21 3392.47   38.88
BR D #Mann= 4
       0     .06 2260.41     .07 2328.94    .035  2498.9     .07
BC Design=,, 0 ,, 0 ,,,,,,
BC Use User HTab Curves=0
BC User HTab FreeFlow(D)= 0

Type RM Length L Ch R = 1 ,19237.91,126.24,105.17,65.21
BEGIN DESCRIPTION:
underwater portion from hec2 section 217.1
Right ineffective flow limit set at RR alignment.
END DESCRIPTION:
XS GIS Cut Line= 6
1634262.00330642713912.6741055551633850.17319296712725.136586651
1633060.36201647  711777.36317491632972.91863623711560.165101364
1632676.73944505711373.9953240451632568.42248371711090.509526789
#Sta/Elev= 30
       0   51.86  258.33   46.43  324.76   41.74  346.91   44.44  590.48   43.96
 1636.88   30.87    1844   31.38 1861.26   33.52 1887.15   29.22 2068.39   28.65
 2137.43   30.75 2260.4128.45735 2304.26   28.14 2328.94   25.45 2353.63   21.46
 2370.08   23.28 2411.22   22.28    2441   17.27    2466   16.77    2476   17.07
 2485.27   23.31  2498.9   25.57 2912.79   25.33  2962.4   29.51 2978.94   27.28
 3069.89   26.12 3118.97   29.09 3253.86   30.19 3313.81   37.21 3392.47   38.88
#Mann= 4 ,-1 , 0
       0     .06       0 2260.41     .07       0 2328.94     .04       0
  2498.9     .07       0
#XS Ineff= 2 ,-1
  -40.62 2139.0931.17846  3107.6 3392.4730.93387
Permanent Ineff=
       F       F
Bank Sta=2328.94,2498.9
XS Rating Curve= 0 ,0
Exp/Cntr=0.5,0.3

Type RM Length L Ch R = 1 ,19132.73,137.22,134.18,68.73
BEGIN DESCRIPTION:
underwater portion from hec2 section 216 with 0.5 foot adjustment
Right ineffective flow limit set at RR alignment.
END DESCRIPTION:
XS GIS Cut Line= 5
1634312.75043747713864.5670241561633916.08187783712691.089201942
1633218.18997662711707.6102367191633059.17769675711687.524475023
1632764.64119786710790.385687143
#Sta/Elev= 30
       0    52.4  243.84   47.01   273.4   44.58  302.95   46.69  628.07   44.84
 1659.29    29.4 1942.54   27.71 2114.21   31.16 2309.4527.24254  2451.7   28.14
 2501.09    25.6    2525   16.77    2565   16.87  2578.7   23.39 2599.87   25.12
 2752.27   25.63 2803.84   23.46 2840.68    26.5 2899.62   25.47 2943.83    27.7
 3002.77   25.28 3069.08   27.31 3098.55   24.88 3157.49   27.32 3245.91   25.62
 3312.21   28.77 3334.32   36.81 3349.05   39.25    346439.86224 3549.18   42.16
#Mann= 5 ,-1 , 0
       0     .06       0 2309.45      .1       0 2501.09     .04       0
 2599.87     .09       0    3464     .06       0
#XS Ineff= 1 ,-1
       0 2112.35  31.144
Permanent Ineff=
       F
Bank Sta=2501.09,2599.87
XS Rating Curve= 0 ,0
Exp/Cntr=0.3,0.1

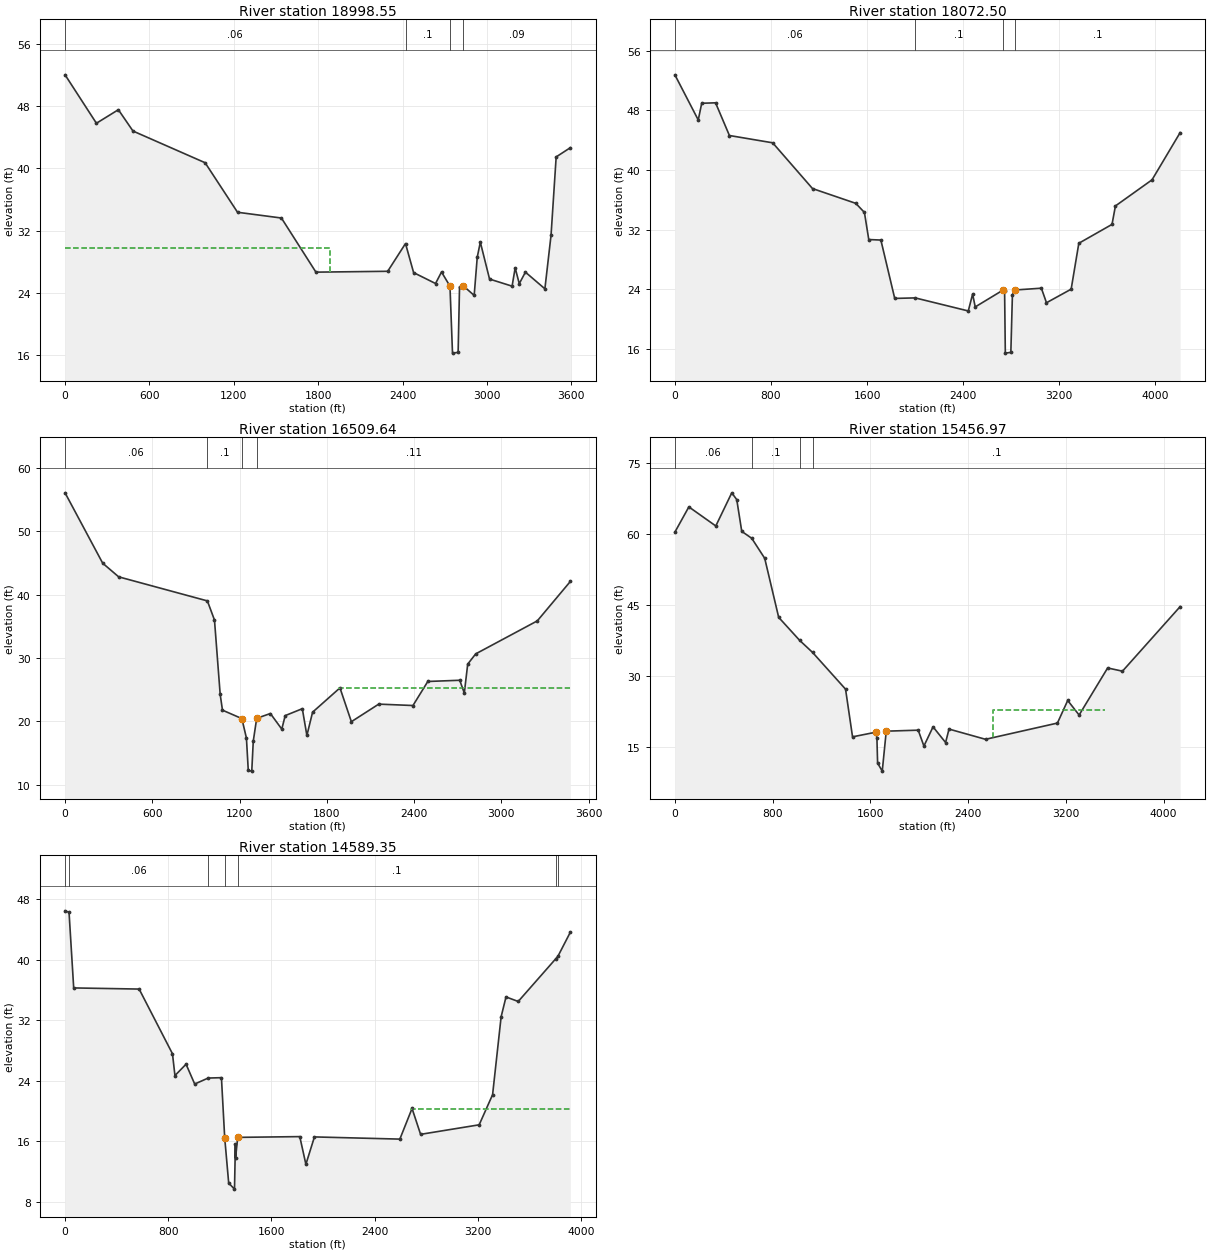
Type RM Length L Ch R = 1 ,18998.55,721.38,926.05,919.72
BEGIN DESCRIPTION:
underwater portion from hec2 section 216
Right ineffective flow limit set at RR alignment.
END DESCRIPTION:
XS GIS Cut Line= 4
1634363.15031348713796.3357522491633591.83123891711635.620728835
1633070.80775809711553.8915553991632856.26867779710813.220920876
#Sta/Elev= 30
       0   52.01  222.98   45.79  379.06   47.53  483.12   44.79  995.97   40.72
 1226.38   34.36 1538.55   33.62 1783.83   26.67 2294.25   26.78 2420.8230.34146
 2478.48   26.61 2634.37   25.21 2676.88   26.69 2736.98   24.87    2755   16.27
    2795   16.37    2805   24.77 2828.94   24.95 2909.11   23.68 2930.97   28.59
 2952.84   30.52 3018.43   25.78 3178.76   24.87 3200.62   27.22 3229.77   25.19
  3273.5   26.67 3411.97   24.53  3455.7   31.41 3492.14   41.47 3592.78   42.65
#Mann= 4 ,-1 , 0
       0     .06       0 2420.82      .1       0 2736.98     .04       0
 2828.94     .09       0
#XS Ineff= 1 ,-1
       0 1883.21  29.822
Permanent Ineff=
       F
Bank Sta=2736.98,2828.94
XS Rating Curve= 0 ,0
Exp/Cntr=0.3,0.1

Type RM Length L Ch R = 1 ,18072.50,1245.55,1562.86,1381.73
BEGIN DESCRIPTION:
underwater portion from hec2 section 215
END DESCRIPTION:
XS GIS Cut Line= 3
1634416.71918614 713742.258697481633822.42402351711308.258528858
 1633557.9783171709627.926436052
#Sta/Elev= 30
       0   52.76  194.55   46.71  223.37   48.95  338.66   49.01  453.95   44.63
  814.24   43.65  1145.7   37.52 1505.98   35.54 1578.04   34.32 1614.07   30.69
 1714.95   30.62 1830.24    22.8 2000.6222.87088 2442.71   21.12 2478.74   23.38
 2500.36   21.66 2732.26   23.92    2745   23.77    2751   15.47    2797   15.57
    2810   23.27 2831.47   23.93 3051.14   24.17 3093.66   22.22 3299.16   24.04
 3362.93   30.19 3639.29   32.72 3667.64   35.19 3972.34   38.69 4206.52   45.02
#Mann= 4 ,-1 , 0
       0     .06       0 2000.62      .1       0 2732.26     .04       0
 2831.47      .1       0
Bank Sta=2732.26,2831.47
XS Rating Curve= 0 ,0
Exp/Cntr=0.3,0.1

Type RM Length L Ch R = 1 ,16509.64,975.94,1052.67,722.73
BEGIN DESCRIPTION:
underwater portion from hec2 section 214
Right Ineffective flow limit set to define narrowed flow in channel.
END DESCRIPTION:
XS GIS Cut Line= 2
1635190.65819475712851.3421841111633622.47967897  709750.7416659
#Sta/Elev= 30
       0   56.03  258.86   44.94  368.69   42.79   978.838.99567 1027.61   35.98
 1066.83   24.25 1082.52   21.78 1215.88   20.45 1247.25   17.38    1260   12.27
    1284   12.17 1294.32    16.9 1317.85   20.49 1411.99   21.25 1490.43   18.79
 1513.96   20.92 1631.63   22.01    1663   17.79 1702.23   21.46 1890.49   25.29
 1968.93   19.96  2157.2   22.73 2392.54   22.51 2494.51    26.3 2714.16   26.49
 2745.54   24.48 2769.07   29.04 2823.98   30.65 3247.58   35.85 3474.63   42.06
#Mann= 4 ,-1 , 0
       0     .06       0   978.8      .1       0 1215.88     .04       0
 1317.85     .11       0
#XS Ineff= 1 ,-1
 1885.17 3478.4125.31432
Permanent Ineff=
       F
Bank Sta=1215.88,1317.85
XS Rating Curve= 0 ,0
Exp/Cntr=0.3,0.1

Type RM Length L Ch R = 1 ,15456.97,993.14,867.62,487.29
BEGIN DESCRIPTION:
END OF DETAILED REACH
underwater portion from hec2 section 213
Right ineffective flow limit is set to define how flow expands dowstream of a narrow section.
END DESCRIPTION:
XS GIS Cut Line= 3
1636269.09522088712917.695100397 1635430.7376418711523.243115336
1633770.61380588709643.472125724
#Sta/Elev= 30
       0   60.35  114.35   65.68  334.88   61.65  465.56   68.65   506.4   67.21
  547.24   60.51  628.91   59.05  735.09   54.82  849.44   42.35 1020.96   37.49
 1127.14   34.93 1396.68   27.18 1453.85   17.11 1645.74    18.1 1653.42   16.82
    1659   11.57    1697    9.87  1729.8   18.31 1991.29   18.52 2037.99   15.17
  2112.7   19.22 2215.43   15.91 2243.45   18.75  2542.3   16.59 3130.66   20.02
 3214.71   24.79 3308.11   21.72 3541.58   31.66 3662.99   30.98 4134.98   44.62
#Mann= 4 ,-1 , 0
       0     .06       0  628.91      .1       0 1020.96    .045       0
 1127.14      .1       0
#XS Ineff= 1 ,-1
    2600 3516.22  22.785
Permanent Ineff=
       F
Bank Sta=1645.74,1729.8
XS Rating Curve= 0 ,0
Exp/Cntr=0.3,0.1

Type RM Length L Ch R = 1 ,14589.35,432.68,541.87,347.86
BEGIN DESCRIPTION:
underwater portion from hec2 section 211 with 2 ft vert adjustment
Right ineffective flow limit set at RR.
END DESCRIPTION:
XS GIS Cut Line= 4
1636804.80937064711815.041804954 1635942.8219943711010.520253703
1635732.11396892711150.9922705891633893.20756604709478.098251298
#Sta/Elev= 30
       0   46.45   30.9546.25251   67.03   36.26  574.51   36.11  833.04   27.56
  852.19   24.68  938.37   26.18  1005.4   23.56 1110.06   24.35 1212.75    24.4
 1237.99   16.48    1269   10.47    1314    9.67    1321   15.57 1322.12   13.79
 1338.95   16.51 1820.33   16.61 1867.65   12.95 1933.89   16.57 2596.31   16.28
 2690.94   20.33 2757.19   16.91 3211.42   18.17 3315.51   22.15 3381.75   32.45
 3419.61   35.07 3514.24   34.47 3805.4740.11639 3821.9340.43574 3918.32   43.62
#Mann= 7 ,-1 , 0
       0      .1       0   30.95     .06       0 1110.06      .1       0
 1237.99    .045       0 1338.95      .1       0 3805.47     .06       0
 3821.93      .1       0
#XS Ineff= 1 ,-1
 2685.82 3917.88  20.273
Permanent Ineff=
       T
Bank Sta=1237.99,1338.95
XS Rating Curve= 0 ,0
Exp/Cntr=0.3,0.1