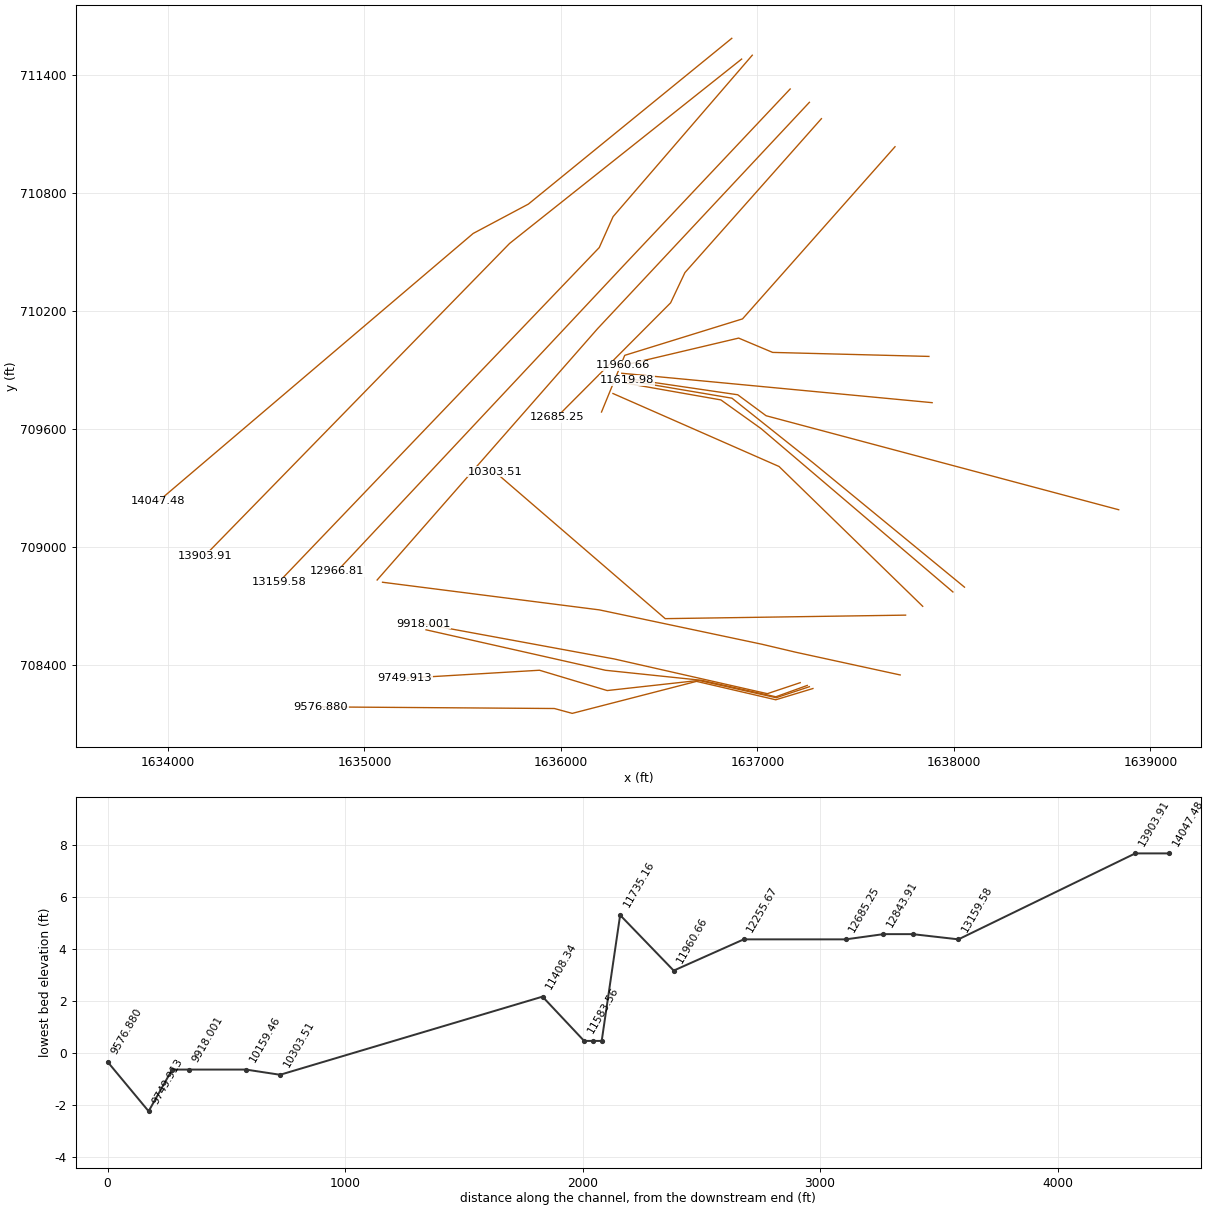
HEC-RAS study LittleElkCreek.prj: Little Elk Creek

--- LittleElkCreek.g01 (geometry) --- (continued)

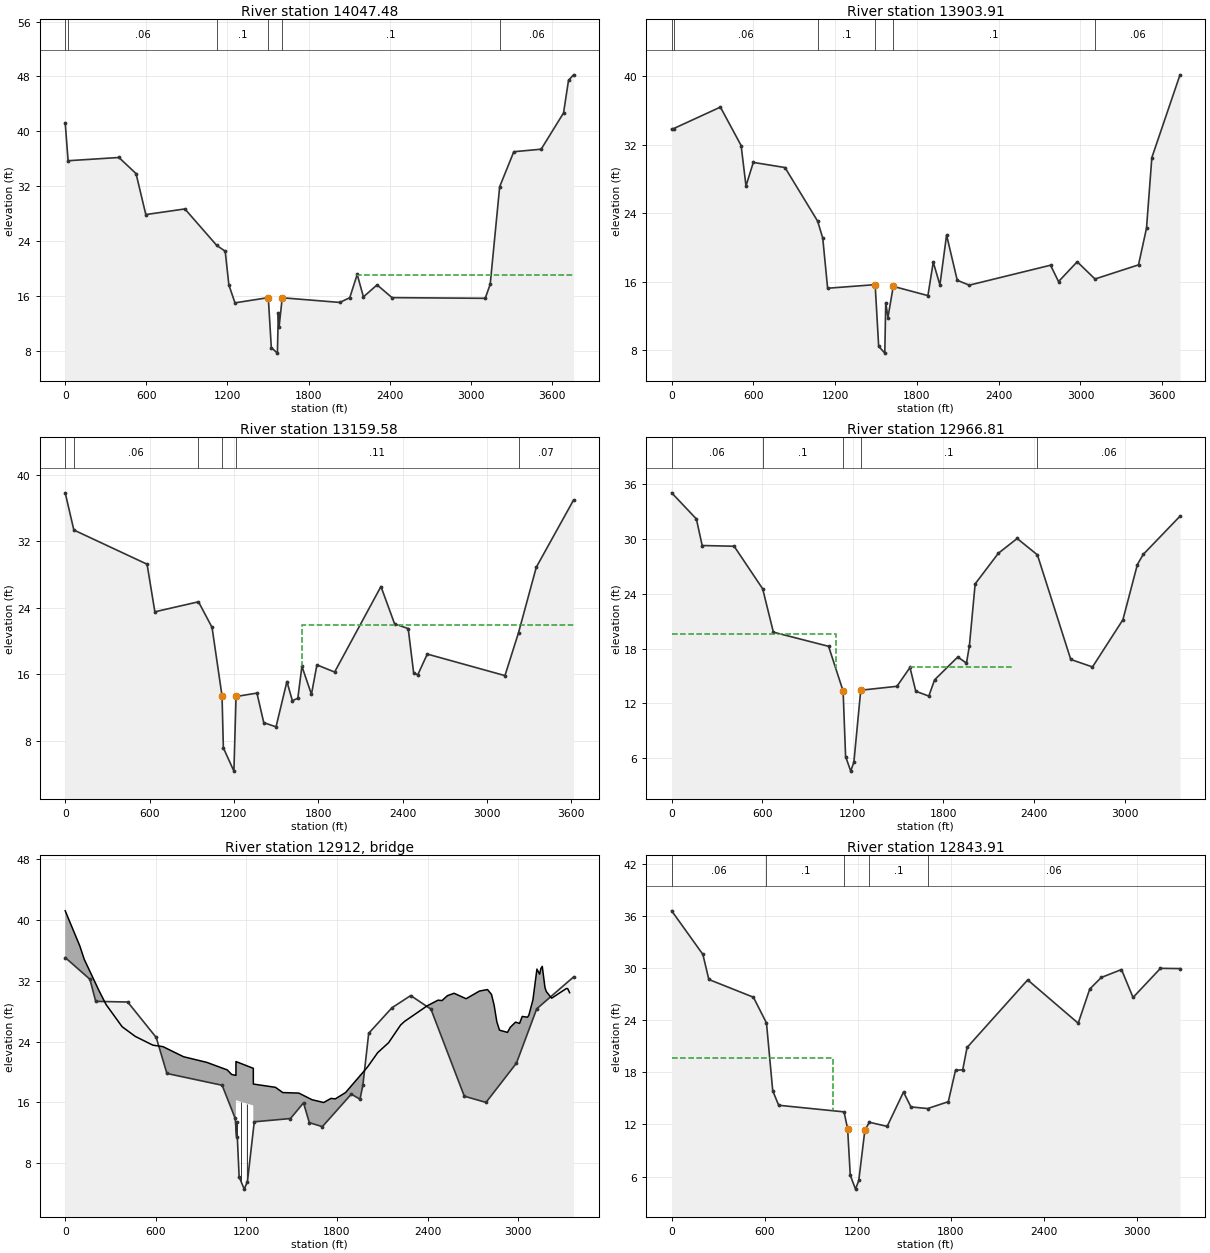
Type RM Length L Ch R = 1 ,14047.48,121.42,143.58,175.82
BEGIN DESCRIPTION:
underwater portion from hec2 section 211
END DESCRIPTION:
XS GIS Cut Line= 4
1636869.54140584711588.5611387341635834.57007897710745.029594883
1635553.39289773710595.467264414 1633950.0847151709231.458810523
#Sta/Elev= 30
       0   41.25   21.4235.71744  397.34   36.19  523.77   33.84  596.01   27.87
  884.99   28.69 1120.8423.36413 1182.99   22.53 1210.08   17.62 1255.24      15
 1501.69   15.76    1524    8.47    1569    7.67    1576   13.57 1580.97   11.41
 1604.76   15.74 2030.47   15.06    2104   15.75 2159.14   19.14 2205.09   15.87
 2306.19   17.62 2416.47   15.76 3105.75   15.66 3142.51   17.71 3212.5431.93008
 3317.13   37.03 3519.32    37.4 3684.75   42.68 3721.51   47.43 3758.68   48.24
#Mann= 6 ,-1 , 0
       0      .1       0   21.42     .06       0 1120.84      .1       0
 1501.69    .045       0 1604.76      .1       0 3212.54     .06       0
#XS Ineff= 1 ,-1
 2155.57 3758.68   19.13
Permanent Ineff=
       T
Bank Sta=1501.69,1604.76
XS Rating Curve= 0 ,0
Exp/Cntr=0.3,0.1

Type RM Length L Ch R = 1 ,13903.91,447.97,744.33,383.86
BEGIN DESCRIPTION:
underwater portion from hec2 section 211
END DESCRIPTION:
XS GIS Cut Line= 3
1636919.74102083711483.017037764 1635738.4990606710544.408561304
1634186.92178321708954.520733818
#Sta/Elev= 30
       0   33.82   14.1833.89998  357.63   36.41  509.63   31.92  545.39    27.2
  599.03   29.95  831.49   29.35 1070.9623.09538 1108.66   21.11 1144.42   15.25
 1493.11   15.67    1519    8.47    1564    7.67    1571   13.57    1587   11.83
 1626.12   15.47 1880.43   14.39 1919.55    18.3 1968.46   15.63 2017.36   21.46
 2095.61   16.18 2183.64   15.61 2780.28   17.94 2838.97   16.03  2975.9   18.34
 3106.5716.33119 3425.83   17.98 3484.51   22.27 3523.64   30.51 3730.28   40.18
#Mann= 6 ,-1 , 0
       0      .1       0   14.18     .06       0 1070.96      .1       0
 1493.11    .045       0 1626.12      .1       0 3106.57     .06       0
#XS Ineff= 1 ,-1
    2017 3730.28   21.41
Permanent Ineff=
       T
Bank Sta=1493.11,1626.12
XS Rating Curve= 0 ,0
Exp/Cntr=0.3,0.1

Type RM Length L Ch R = 1 ,13159.58,221.45,192.77,363.3
BEGIN DESCRIPTION:
underwater portion from hec2 section 210.4
END DESCRIPTION:
XS GIS Cut Line= 4
 1636973.9655589 711502.659724371636265.56157091710681.078767881
1636195.13059784710523.713065669 1634563.6421921 708820.43380858
#Sta/Elev= 30
       0   37.82   61.47 33.3504   582.3   29.24  637.75   23.52  948.0624.72245
 1044.44   21.65 1115.49   13.41    1125    7.17    1200    4.37 1215.19   13.34
 1363.85   13.75 1412.31    10.2 1499.55    9.69  1577.1   15.14 1615.87   12.83
 1654.64   13.13 1683.72   16.97 1751.57    13.6 1790.35   17.14 1916.36   16.28
 2245.92   26.56 2342.85   22.08 2439.78    21.5 2478.56   16.18 2507.64   15.94
 2575.49   18.44    3128   15.85 3224.5821.01718 3350.94   28.88 3615.81   36.95
#Mann= 6 ,-1 , 0
       0      .1       0   61.47     .06       0  948.06     .11       0
 1115.49    .045       0 1215.19     .11       0 3224.58     .07       0
#XS Ineff= 1 ,-1
 1685.77 3615.8221.96427
Permanent Ineff=
       F
Bank Sta=1115.49,1215.19
XS Rating Curve= 0 ,0
Exp/Cntr=0.5,0.3

Type RM Length L Ch R = 1 ,12966.81,134.44,122.9,128.76
BEGIN DESCRIPTION:
underwater portion from hec2 section 210.3
END DESCRIPTION:
XS GIS Cut Line= 3
1637166.78557931711330.7984018331636314.07375693710426.880160823
 1634861.3705529708876.962976083
#Sta/Elev= 30
       0   35.05  163.59   32.19  202.09   29.28   413.8    29.2  602.68 24.5384
  673.62   19.79  1039.3   18.24 1135.53   13.34    1152    6.17    1186    4.57
    1207    5.57 1252.25   13.43  1492.1   13.86 1578.45   15.92 1616.82   13.32
 1703.17   12.79 1741.55   14.57 1895.05   17.07 1952.62    16.4  1971.8   18.27
 2010.18   25.08 2163.69   28.43 2288.41   30.05 2422.5128.25482 2643.38    16.8
 2787.29   15.98 2988.77   21.15 3084.71    27.2 3123.08    28.3 3366.93   32.49
#Mann= 5 ,-1 , 0
       0     .06       0  602.68      .1       0 1135.53    .045       0
 1252.25      .1       0 2422.51     .06       0
#XS Ineff= 3 ,-1
       0    1088   19.54 1578.05 2269.22   15.92 2269.22 3324.56   29.72
Permanent Ineff=
       F       T       F
Bank Sta=1135.53,1252.25
XS Rating Curve= 0 ,0
Exp/Cntr=0.5,0.3

Type RM Length L Ch R = 3 ,12912   ,,,
BEGIN DESCRIPTION:
US Route 279 Bridge # CE050908PF-1.  Top of Rd elevation from lidar.   Geometry of bridge from HEC2 model section 210.3.
END DESCRIPTION:
Bridge Culvert--1,0,-1,-1, 0
Deck Dist Width WeirC Skew NumUp NumDn MinLoCord MaxHiCord MaxSubmerge Is_Ogee
45,46,2.6,0, 60, 60, , , 0.95, 0, 0,0,,
       0   96.71  125.72  222.44  270.79  377.17  464.21  580.27  647.97  783.36
   938.1  1073.5 1102.51  1130.9    1131    1246  1246.1 1392.64    1441 1547.38
 1634.42 1711.79 1760.15 1789.16 1856.86 2001.93 2069.62  2141.9 2221.57 2248.13
 2398.61 2469.43 2495.98 2531.39 2575.65 2655.32 2743.84 2796.95 2823.51 2841.21
 2858.92 2876.62 2929.73 2947.44 2982.85  3009.4 3027.11 3062.52 3071.37 3097.92
 3124.48 3142.18 3151.04 3159.89 3177.59 3186.44 3221.85 3319.23 3328.08 3341.01
    41.2   36.58   34.83   30.75   28.86   25.94   24.67   23.52   23.32      22
   21.25   20.26   19.66   19.54   21.36   20.47    18.4   17.97   17.28   17.21
   16.34   15.97   16.51   16.45   17.28   20.63   22.53   23.84   26.17   26.65
   28.71   29.44   29.39   30.03   30.35   29.63   30.64   30.84    30.2   28.76
   26.59   25.49    25.2   25.86   26.55   26.38    27.3    27.2   27.49   29.48
   33.53   32.86   33.63   33.89   31.12   30.58    29.7   30.97   30.96   30.42
                                                                                
                                   16.27   15.58
                                                                                
                                                                                
                                                                                
                                                                                
       0   96.71  125.72  222.44  270.79  377.17  464.21  580.27  647.97  783.36
   938.1  1073.5 1102.51  1130.9    1131    1246  1246.1 1392.64    1441 1547.38
 1634.42 1711.79 1760.15 1789.16 1856.86 2001.93 2069.62  2141.9 2221.57 2248.13
 2398.61 2469.43 2495.98 2531.39 2575.65 2655.32 2743.84 2796.95 2823.51 2841.21
 2858.92 2876.62 2929.73 2947.44 2982.85  3009.4 3027.11 3062.52 3071.37 3097.92
 3124.48 3142.18 3151.04 3159.89 3177.59 3186.44 3221.85 3319.23 3328.08 3341.01
    41.2   36.58   34.83   30.75   28.86   25.94   24.67   23.52   23.32      22
   21.25   20.26   19.66   19.54   21.36   20.47    18.4   17.97   17.28   17.21
   16.34   15.97   16.51   16.45   17.28   20.63   22.53   23.84   26.17   26.65
   28.71   29.44   29.39   30.03   30.35   29.63   30.64   30.84    30.2   28.76
   26.59   25.49    25.2   25.86   26.55   26.38    27.3    27.2   27.49   29.48
   33.53   32.86   33.63   33.89   31.12   30.58    29.7   30.97   30.96   30.42
                                                                                
                                   16.27   15.58
                                                                                
                                                                                
                                                                                
                                                                                
Pier Skew, UpSta & Num, DnSta & Num=  ,1166, 2 ,1166, 2 , 0 , 0 , 0 ,,
       2       2
       0      16
       2       2
       0      16
Pier Skew, UpSta & Num, DnSta & Num=  ,1206, 2 ,1206, 2 , 0 , 0 , 0 ,,
       2       2
       0      16
       2       2
       0      16
BR Coef=-1 , 1 , 0 ,, 0 ,,,0.8,0,0.5,0,
WSPro=,,,, 1 ,,,, 0 ,,,, 0 ,,,,-1 ,-1 ,-1 , 0 , 0 , 0 , 0 , 0
BR U #Sta/Elev= 30
       0   35.05  163.59   32.19  202.09   29.28   413.8    29.2  602.68  24.538
  673.62   19.79  1039.3   18.24 1125.91   13.88  1135.2   11.48 1135.53   13.34
    1152    6.17    1186    4.57    1207    5.57 1252.25   13.43  1492.1   13.86
 1578.45   15.92 1616.82   13.32 1703.17   12.79 1895.05   17.07 1952.62    16.4
  1971.8   18.27 2010.18   25.08 2163.69   28.43 2288.41   30.05 2422.51  28.255
 2643.38    16.8 2787.29   15.98 2988.77   21.15 3123.08    28.3 3366.93   32.49
BR U #Mann= 5
       0     .06  602.68      .1 1135.53     .04 1252.25      .1 2422.51     .06
BR D #Sta/Elev= 30
       0   36.56  201.32   31.55  239.67   28.67  527.27   26.63  611.57  23.667
   651.9   15.88  690.25   14.21 1112.07   13.45 1131.24   12.44    1152    6.17
    1186    4.57    1207    5.57 1246.28   11.34 1275.04   12.26 1390.08   11.78
 1495.54   15.73 1543.47   14.02 1651.41  13.833  1784.5   14.62 1831.05   18.23
 1877.61   18.29 1905.54   20.85  2296.6   28.62 2622.49   23.64 2696.98   27.57
 2771.47    28.9 2901.82   29.81 2976.31    26.6 3153.22   29.95 3279.21   29.92
BR D #Mann= 5
       0     .06  611.57      .1 1112.07     .04 1275.04      .1 1651.41     .06
BC Design=,, 0 ,, 0 ,,,,,,
BC Use User HTab Curves=0
BC User HTab FreeFlow(D)= 0

Type RM Length L Ch R = 1 ,12843.91,157.19,158.66,186.87
BEGIN DESCRIPTION:
underwater portion from hec2 section 210.2
END DESCRIPTION:
XS GIS Cut Line= 3
1637264.66829802711262.9232188171636185.34535463710109.504878849
1635064.66117619708831.787282035
#Sta/Elev= 30
       0   36.56  201.32   31.55  239.67   28.67  527.27   26.63  611.5723.66741
   651.9   15.88  690.25   14.21 1112.07   13.45  1135.2   11.48    1152    6.17
    1186    4.57    1207    5.57 1246.28   11.34 1275.04   12.26 1390.08   11.78
 1495.54   15.73 1543.47   14.02 1651.4113.83278  1784.5   14.62 1831.05   18.23
 1877.61   18.29 1905.54   20.85  2296.6   28.62 2622.49   23.64 2696.98   27.57
 2771.47    28.9 2901.82   29.81 2976.31    26.6 3153.22   29.95 3279.21   29.92
#Mann= 5 ,-1 , 0
       0     .06       0  611.57      .1       0 1112.07    .045       0
 1275.04      .1       0 1651.41     .06       0
#XS Ineff= 1 ,-1
       0 1043.6619.65067
Permanent Ineff=
       F
Bank Sta=1135.2,1246.28
XS Rating Curve= 0 ,0
Exp/Cntr=0.5,0.3

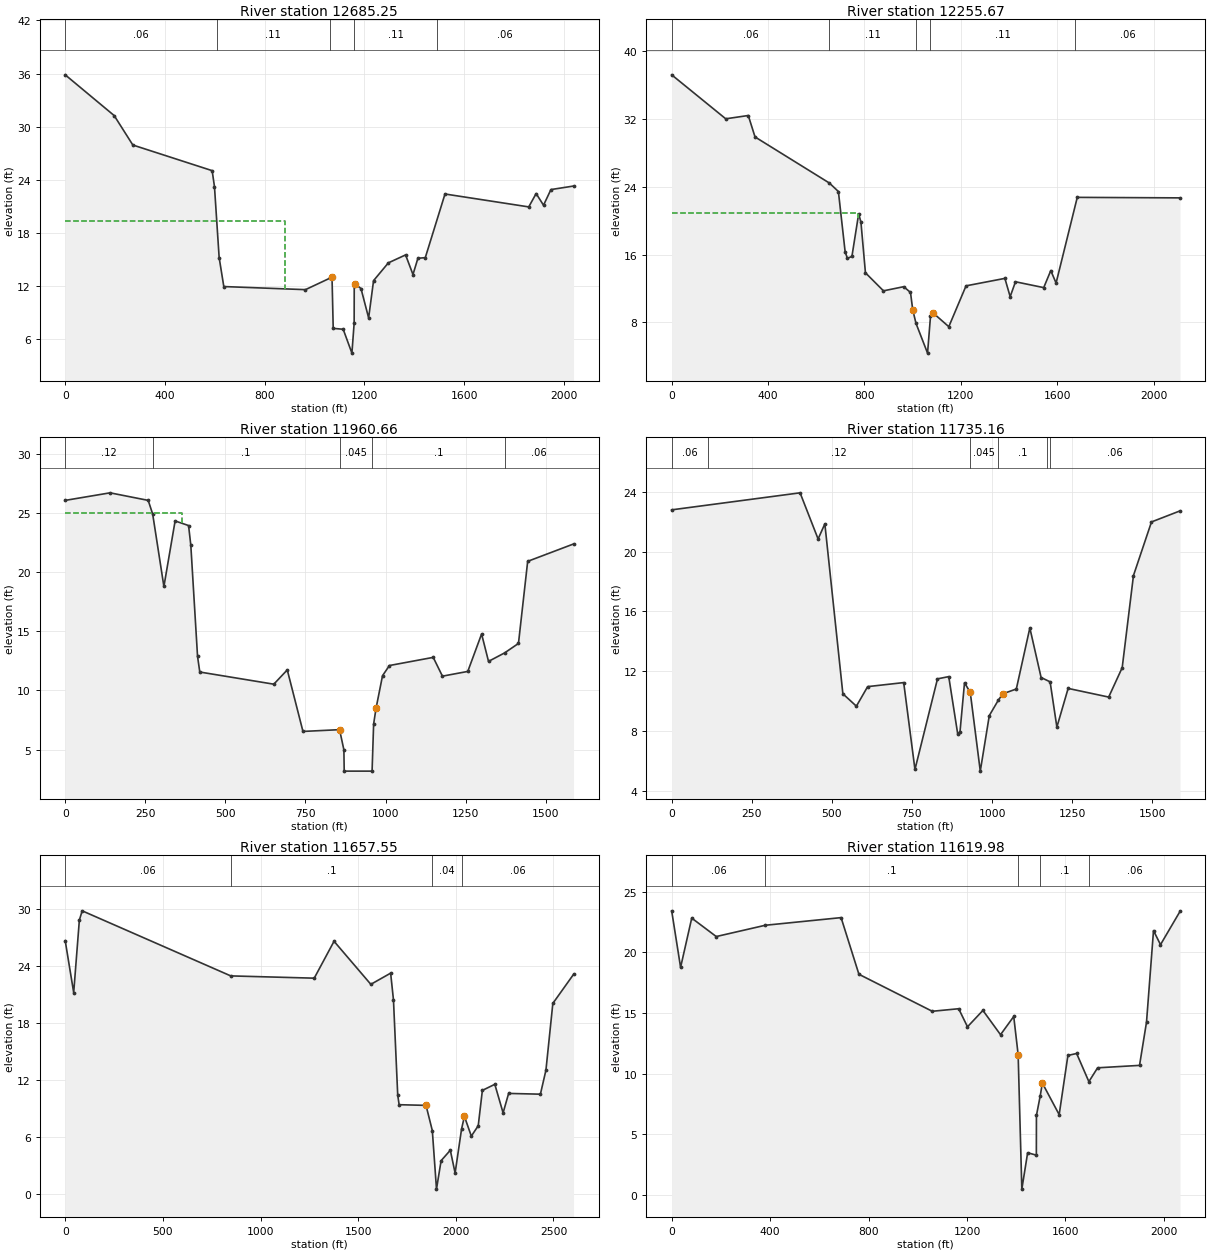
Type RM Length L Ch R = 1 ,12685.25,433.8,429.58,387.72
BEGIN DESCRIPTION:
underwater portion from hec2 section 210.1
Ineffective flow limits to define the expanding flow on the left bank.
END DESCRIPTION:
XS GIS Cut Line= 4
 1637325.7970002711179.6430803841636631.15265732710396.238627046
1636558.45175847710242.5001645091635978.44169255709660.224398106
#Sta/Elev= 30
       0   35.85  196.47   31.24  271.31   27.91   589.4   25.01  598.75    23.2
  617.46   15.18  636.17    11.9  963.62   11.55 1062.51   12.86 1070.25   12.93
    1075    7.17    1115    7.07    1150    4.37    1159    7.77 1159.34   11.96
 1163.17   12.19  1186.4   11.68 1217.08    8.35 1236.84   12.57 1296.12   14.58
 1365.29   15.48 1394.93   13.26 1414.69    15.1 1444.33   15.17 1523.37   22.37
  1859.3   20.91 1888.94   22.42 1918.58    21.1 1948.22   22.87 2038.94   23.27
#Mann= 5 ,-1 , 0
       0     .06       0  607.74     .11       0 1062.51    .045       0
 1159.38     .11       0 1490.13     .06       0
#XS Ineff= 1 ,-1
       0     880  19.316
Permanent Ineff=
       F
Bank Sta=1070.25,1163.17
XS Rating Curve= 0 ,0
Exp/Cntr=0.3,0.1

Type RM Length L Ch R = 1 ,12255.67,411.43,295.01,93.76
BEGIN DESCRIPTION:
underwater portion from hec2 section 209.42
END DESCRIPTION:
XS GIS Cut Line= 4
1637700.45885623711036.8694540111636924.39391491 710160.70561555
1636324.76862441709975.0975932931636206.67446627709686.715702221
#Sta/Elev= 30
       0   37.21  224.43   32.02  317.94   32.41  345.99   29.88  654.58   24.44
  691.98   23.44  720.04    16.3  729.39   15.56  748.09   15.78  776.14   20.82
  785.49   19.83   804.2   13.85  879.01   11.72  963.17   12.21  991.22   11.53
 1000.57    9.47 1014.08    7.88    1062    4.37 1074.23    8.71 1084.73    9.12
 1150.19    7.49 1221.74   12.31 1382.95   13.19 1404.93   11.03 1426.91   12.79
 1544.15    12.1 1573.46   14.11 1595.45   12.64 1683.38   22.75 2109.76   22.69
#Mann= 5 ,-1 , 0
       0     .06       0  654.58     .11       0 1014.08    .045       0
 1074.23     .11       0 1675.68     .06       0
#XS Ineff= 2 , 0
          773.63   20.94
Permanent Ineff=
       F       F
Bank Sta=1000.57,1084.73
XS Rating Curve= 0 ,0
Exp/Cntr=0.3,0.1

Type RM Length L Ch R = 1 ,11960.66,187.69,225.5,234.74
BEGIN DESCRIPTION:
underwater portion from hec2 section 209.41
END DESCRIPTION:
XS GIS Cut Line= 4
1637873.02808465 709969.674193681637077.54296626709990.084031105
1636904.56488889710062.9169057911636317.25650567709924.182121918
#Sta/Elev= 30
       0   26.09  140.05   26.73  259.09   26.09  273.09   24.93   308.1    18.8
  343.11   24.35  385.13   23.96  392.13   22.29  413.14   12.88  420.14   11.56
  651.21   10.53  693.23   11.74  742.24    6.53  856.51    6.68     870    4.97
     871    3.17     958    3.17  962.84    7.16  970.44     8.5  990.63   11.25
  1012.2   12.11 1148.86    12.8 1177.63   11.21 1256.75   11.61 1299.91   14.78
 1321.49   12.46 1371.84   13.18 1414.99   13.98 1443.76   20.93  1586.9    22.4
#Mann= 5 ,-1 , 0
       0     .12       0  273.09      .1       0  856.51    .045       0
     958      .1       0 1371.84     .06       0
#XS Ineff= 2 , 0
          363.24      25
Permanent Ineff=
       F       F
Bank Sta=856.51,970.44
XS Rating Curve= 0 ,0
Exp/Cntr=0.3,0.1

Type RM Length L Ch R = 1 ,11735.16,148.85,77.61,53.39
BEGIN DESCRIPTION:
underwater portion from hec2 section 209.4  --- Old channel alignment on left
Expansion, contraction coefficents changed to .3 and .5 to adjust for remaining constriction from previous tressel bridge abutments.
END DESCRIPTION:
XS GIS Cut Line= 2
1637889.37524794709734.2750426231636309.76307884709883.869422168
#Sta/Elev= 30
       0    22.8  400.79   23.94  457.04   20.85  478.13   21.86  534.38   10.48
  576.57    9.65  611.72   10.96  724.23   11.23  759.38    5.41   829.7   11.48
  864.85   11.63  892.98    7.77  900.01    7.94  914.07   11.22  932.02   10.57
  963.29     5.3  991.42    9.02 1019.54   10.05  1033.6   10.48 1075.79    10.8
 1117.98   14.89 1153.14   11.57 1181.26   11.28 1202.36    8.25 1237.51   10.84
 1364.08   10.26 1406.27   12.23 1441.42    18.4 1497.67   21.99 1586.68   22.73
#Mann= 6 ,-1 , 0
       0     .06       0   114.4     .12       0  932.02    .045       0
 1019.54      .1       0 1171.45      .1       0 1179.38     .06       0
Bank Sta=932.02,1033.6
XS Rating Curve= 0 ,0
Exp/Cntr=0.5,0.3

Type RM Length L Ch R = 1 ,11657.55,39.22,37.57,21.72
BEGIN DESCRIPTION:
underwater portion from hec2 section 209.3  Cross section upstream of wood tressle bridge. This bridge has been removed.  Abutments remain in place.
Expansion, contraction coefficents changed to .3 and .5 to adjust for remaining constriction from previous tressel bridge abutments.
END DESCRIPTION:
XS GIS Cut Line= 4
1638838.93732356709189.3094674651637044.29229569709667.774782449
1636899.91414976709774.4890642611636340.11011001709856.557094157
#Sta/Elev= 30
       0   26.66   43.47   21.19   72.45   28.83   86.93   29.81  847.61   22.95
 1275.03   22.71 1376.46    26.6 1564.81   22.06 1666.24   23.24 1680.73   20.42
 1702.46   10.39  1709.7    9.37 1847.35     9.3 1879.65    6.64    1901     .47
  1924.6    3.47  1971.8    4.57  1996.3    2.17 2029.54    6.83 2043.94    8.14
 2079.32    6.06 2114.69    7.15 2135.91   10.88 2199.59   11.52 2242.03    8.51
 2270.33   10.56 2433.05   10.48 2461.35   13.01 2496.72   20.05 2602.65   23.11
#Mann= 4 ,-1 , 0
       0     .06       0  847.61      .1       0 1879.65     .04       0
 2029.54     .06       0
Bank Sta=1847.35,2043.94
XS Rating Curve= 0 ,0
Exp/Cntr=0.5,0.3

Type RM Length L Ch R = 1 ,11619.98,30.03,36.42,20.36
BEGIN DESCRIPTION:
Previous location of wood tressel bridge. Bridge has been removed.  Underwater portion from HEC2 Section 209.3.
Expansion, contraction coefficents changed to .3 and .5 to adjust for remaining constriction from previous tressel bridge abutments.
END DESCRIPTION:
XS GIS Cut Line= 4
1638054.07704498708795.2295403031637284.19873492709427.656158105
 1636870.6430589709757.0774529431636337.48463944709847.188735127
#Sta/Elev= 30
       0   23.41   36.24   18.75   81.53   22.81  181.18   21.29  380.48   22.22
  688.48   22.85  760.95   18.18 1058.98   15.13 1166.37   15.34 1202.16   13.85
 1264.81    15.2  1336.4    13.2  1390.1    14.7    1408   11.56    1423     .47
  1446.6    3.47    1482    3.27 1482.34    6.54 1497.49    8.13 1506.44    9.21
 1574.75    6.61 1610.24   11.49 1645.74   11.65 1695.43    9.33 1730.93   10.47
 1901.31   10.67 1929.71   14.24 1958.11   21.78  1986.5   20.62 2065.77   23.36
#Mann= 5 ,-1 , 0
       0     .06       0  380.48      .1       0    1408     .04       0
 1497.49      .1       0 1695.43     .06       0
Bank Sta=1408,1506.44
XS Rating Curve= 0 ,0
Exp/Cntr=0.5,0.3

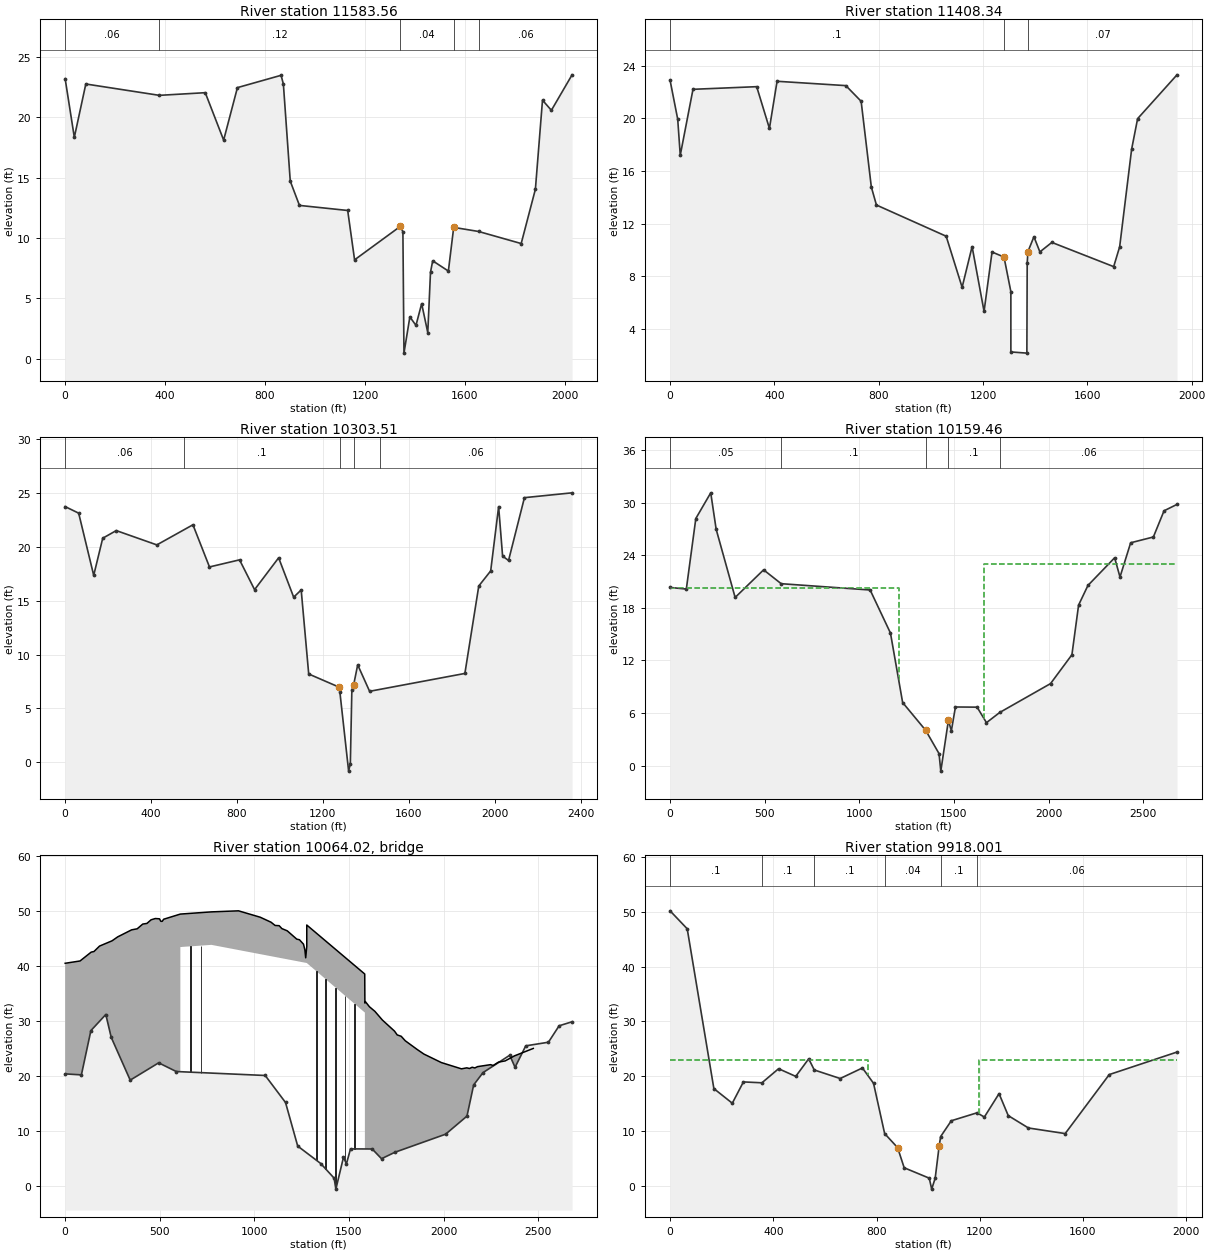
Type RM Length L Ch R = 1 ,11583.56,156.73,175.23,190.99
BEGIN DESCRIPTION:
underwater portion from hec2 section 209.2
Expansion, contraction coefficents changed to .3 and .5 to adjust for remaining constriction from previous tressel bridge abutments.
END DESCRIPTION:
XS GIS Cut Line= 4
1637995.10331687 708770.946240471637019.18305294709601.863020167
1636814.12423691709748.3336030391636326.58643964709834.123515859
#Sta/Elev= 30
       0   23.21   36.77   18.35   82.74   22.77  376.93   21.83   560.8   22.05
  634.35   18.12  689.51   22.47  864.19   23.49  873.38   22.77  900.97   14.72
  937.74   12.71  1130.8   12.29 1158.38     8.2 1341.95   10.98 1351.76   10.52
    1356     .47  1379.6    3.47  1404.1    2.77  1426.8    4.57  1451.3    2.17
  1462.2    7.17 1470.99    8.12 1533.73    7.27 1555.05   10.89 1654.56   10.55
 1825.14    9.55    1882   14.05 1910.43   21.43 1945.97   20.59 2028.76   23.53
#Mann= 5 ,-1 , 0
       0     .06       0  376.93     .12       0 1341.95     .04       0
 1555.05      .1       0 1654.56     .06       0
Bank Sta=1341.95,1555.05
XS Rating Curve= 0 ,0
Exp/Cntr=0.5,0.3

Type RM Length L Ch R = 1 ,11408.34,1014.74,1104.82,920.34
XS GIS Cut Line= 3
1637841.36623608708697.8131508831637110.11677401709409.479773074
1636264.86093339709780.908353686
#Sta/Elev= 30
       0    22.9    29.3   19.94   39.07    17.2   87.91   22.21  332.11   22.41
  380.95   19.24  410.25   22.82  673.98   22.49  732.59    21.3  771.66   14.79
  791.19   13.42 1058.62   11.05 1119.79    7.17 1158.02   10.26 1203.89    5.34
 1234.48    9.85 1280.35    9.47 1306.65    6.84 1306.68    2.26    1368    2.17
  1369.3    9.01  1372.1    9.88 1395.04   11.01 1417.98    9.86 1463.86   10.58
 1700.88    8.74 1723.82   10.25  1769.7   17.66 1792.63   19.98 1943.65   23.31
#Mann= 3 , 0 , 0
       0      .1       0 1280.35     .04       0  1372.1     .07       0
Bank Sta=1280.35,1372.1
XS Rating Curve= 0 ,0
Exp/Cntr=0.3,0.1

Type RM Length L Ch R = 1 ,10303.51,73.67,144.05,139.66
BEGIN DESCRIPTION:
underwater portion from hec2 section 208.4
END DESCRIPTION:
XS GIS Cut Line= 3
1637754.25889412708652.905723408 1636530.8151411708635.025782704
1635664.59911136709381.856370732
#Sta/Elev= 30
       0   23.76   63.01   23.15  133.01   17.37  175.02   20.82  238.03   21.53
  427.05    20.2  595.06   22.07  672.07   18.15  812.09   18.81  882.09   16.04
   994.1      19 1064.11   15.34 1099.12   16.01 1134.12     8.2 1275.26    6.98
 1279.03    6.57    1320    -.83    1328    -.13    1335    6.67 1343.73    7.22
 1362.21    9.05 1417.67    6.59 1861.31    8.25 1926.01   16.38 1981.46   17.78
 2018.43   23.76 2036.92   19.16 2064.64   18.75 2138.58   24.59  2360.4   25.04
#Mann= 5 ,-1 , 0
       0     .06       0  553.35      .1       0 1279.03     .04       0
 1343.73      .1       0  1464.5     .06       0
Bank Sta=1275.26,1343.73
XS Rating Curve= 0 ,0
Exp/Cntr=0.5,0.3

Type RM Length L Ch R = 1 ,10159.46,272.37,241.47,246.62
BEGIN DESCRIPTION:
underwater portion from hec2 section 208.3
END DESCRIPTION:
XS GIS Cut Line= 5
1637726.75848141708348.4368683991637195.15158108708464.136574149
1637022.85488401708504.7799684261636196.00812963708679.589341417
1635092.12963074708820.270340323
#Sta/Elev= 30
       0   20.33   85.97   20.15  136.11    28.2  214.92   31.13  243.57   26.97
  343.87   19.19  494.31   22.34   587.2   20.76 1057.35   20.04 1164.67   15.13
 1229.07     7.2  1350.7    4.03  1421.4    1.37  1430.8    -.63 1470.85    5.15
 1486.64    3.98  1508.1    6.69 1622.66    6.67 1672.06     4.9 1742.62    6.07
 2010.77    9.36 2123.68   12.65 2158.96   18.32 2208.36   20.56 2349.49   23.72
 2377.72   21.52 2434.17   25.43 2554.14   26.09 2610.59   29.08 2679.02   29.81
#Mann= 5 ,-1 , 0
       0     .05       0   587.2      .1       0  1350.7     .04       0
 1470.85      .1       0 1742.62     .06       0
#XS Ineff= 2 , 0
       0    1209   20.29    1660       0      23
Permanent Ineff=
       F       F
Bank Sta=1350.7,1470.85
XS Rating Curve= 0 ,0
Exp/Cntr=0.5,0.3

Type RM Length L Ch R = 3 ,10064.02,,,
BEGIN DESCRIPTION:
Hwy 40 Bridge- CE050907PF-9
No new survey information.
Geometry for main river channel from HEC2.
Left opening is for the Conrail Railroad. - But no
information on the RR opening.
END DESCRIPTION:
Bridge Culvert--1,0,-1,-1, 0
Deck Dist Width WeirC Skew NumUp NumDn MinLoCord MaxHiCord MaxSubmerge Is_Ogee
67,100,2.6,0, 60, 60, , , 0.98, 0, 0,0,,
       0   78.73  137.64  152.36  181.82  248.09  277.55  351.19  380.64   410.1
  432.19  454.28  476.37  498.46  505.82  513.19  520.55  608.91  608.92  773.12
  773.13  916.28 1030.81 1088.07 1109.54 1131.02 1145.33 1173.97 1224.07 1238.39
 1259.86 1267.02  1271.3 1276.94 1276.95 1583.32 1584.13  1586.7 1608.21 1636.88
 1677.04 1740.71 1754.86 1776.08  1797.3 1860.96 1896.33 1988.29  2094.4  2122.7
 2136.84 2150.99 2165.14 2179.29 2248.06  2262.1  2290.2 2325.32 2374.49 2474.01
   40.45   40.87   42.48   42.59   43.58   44.54   45.25   46.53   46.72   47.58
    47.7   48.36   48.59   48.54   48.08   48.08   48.46    49.4    49.4    49.8
    49.8   49.99   48.83   47.92   47.33   47.29   46.76   46.35   44.84   44.73
   43.92   42.86   41.44   43.51   47.41    38.5   33.21   33.48   32.54   31.71
   30.11   28.11   27.42   27.17   26.36   24.76   23.93   22.39   21.25   21.43
   21.31   21.54   21.41   21.65   22.01   21.86   22.47   22.69   23.61   24.96
                                                                                
                                                                    43.4    43.8
                                                                                
                            40.5    40.5    31.5    31.5
                                                                                
                                                                                
    -388 -314.36 -299.64 -270.18 -203.91 -174.45 -100.81  -71.36   -41.9  -19.81
    2.28   24.37   46.46   53.82   61.19   68.55  160.99     161     325  325.01
  464.28  578.81  636.07  657.54  679.02  693.33  721.97  772.07  786.39  807.86
  815.02   819.3  824.94  824.95 1131.32 1132.13  1134.7 1156.21 1184.88 1225.04
 1288.71 1302.86 1324.08  1345.3 1408.96 1444.33 1536.29  1642.4  1670.7 1684.84
 1698.99 1713.14 1727.29 1796.06  1810.1  1838.2 1873.32 1908.44 1922.49 2022.01
   40.45   42.48   42.59   43.58   44.54   45.25   46.53   46.72   47.58    47.7
   48.36   48.59   48.54   48.08   48.08   48.46    49.4    49.4    49.8    49.8
   49.99   48.83   47.92   47.33   47.29   46.76   46.35   44.84   44.73   43.92
   42.86   41.44   43.51   47.41    38.5   33.21   33.48   32.54   31.71   30.11
   28.11   27.42   27.17   26.36   24.76   23.93   22.39   21.25   21.43   21.31
   21.54   21.41   21.65   22.01   21.86   22.47   22.69   23.21   23.61   24.96
                                                                                
                                                            43.4    43.8
                                                                                
                    40.5    40.5    31.5    31.5
                                                                                
                                                                                
Pier Skew, UpSta & Num, DnSta & Num=  ,663, 2 ,216, 2 , 0 , 0 , 0 ,,
       3       3
       0      48
       3       3
       0      48
Pier Skew, UpSta & Num, DnSta & Num=  ,718, 2 ,271, 2 , 0 , 0 , 0 ,,
       3       3
       0      48
       3       3
       0      48
Pier Skew, UpSta & Num, DnSta & Num=  ,1329, 2 ,877, 2 , 0 , 0 , 0 ,,
       3       3
       0      42
       3       3
       0      42
Pier Skew, UpSta & Num, DnSta & Num=  ,1375, 2 ,923, 2 , 0 , 0 , 0 ,,
       3       3
       0      42
       3       3
       0      42
Pier Skew, UpSta & Num, DnSta & Num=  ,1430, 2 ,978, 2 , 0 , 0 , 0 ,,
       3       3
       0      42
       3       3
       0      42
Pier Skew, UpSta & Num, DnSta & Num=  ,1480, 2 ,1028, 2 , 0 , 0 , 0 ,,
       3       3
       0      42
       3       3
       0      42
Pier Skew, UpSta & Num, DnSta & Num=  ,1530, 2 ,1078, 2 , 0 , 0 , 0 ,,
       3       3
       0      42
       3       3
       0      42
BR Coef=-1 , 1 , 0 ,, 0 ,,,0.8,0,1.2,0,
WSPro=,,,, 1 ,,,, 0 ,,,, 0 ,,,,-1 ,-1 ,-1 , 0 , 0 , 0 , 0 , 0
BR U #Sta/Elev= 30
       0   20.33   85.97   20.15  136.11    28.2  214.92   31.13  243.57   26.97
  343.87   19.19  494.31   22.34   587.2   20.76 1057.35   20.04 1164.67   15.13
 1229.07     7.2  1350.7    4.03  1421.4    1.37  1430.8    -.63 1470.85    5.15
 1486.64    3.98  1508.1    6.69 1622.66    6.67 1672.06     4.9 1742.62    6.07
 2010.77    9.36 2123.68   12.65 2158.96   18.32 2208.36   20.56 2349.49   23.72
 2377.72   21.52 2434.17   25.43 2554.14   26.09 2610.59   29.08 2679.02   29.81
BR U #Mann= 5
       0     .05   587.2      .1  1350.7    .038 1470.85      .1 1742.62     .06
BR D #Sta/Elev= 30
       0   50.17   66.43   46.89  132.86    28.7     155    20.5     335    20.5
  355.96   18.78  420.56   21.35     487   19.95  537.25   23.16  558.78   21.12
  659.27   19.56   745.4   21.49  788.47   18.69  831.53    9.51  867.42    8.26
   907.2    3.27  1004.4    1.37  1013.8    -.63  1027.4    1.37 1048.61    8.97
 1089.79   11.85 1189.44    13.3 1217.91   12.53 1274.85    16.8 1310.44   12.79
 1388.73   10.53 1531.09    9.51 1602.26    15.5 1701.91   20.28 1964.42   24.39
BR D #Mann= 6
       0      .1  355.96      .1  558.78      .1  831.53    .038 1048.61      .1
 1189.44     .06
BC Design=,, 0 ,, 0 ,,,,,,
BC Use User HTab Curves=0
BC User HTab FreeFlow(D)= 0

Type RM Length L Ch R = 1 ,9918.001,50.03,69.07,81.11
BEGIN DESCRIPTION:
underwater portion from hec2 section 208.2
END DESCRIPTION:
XS GIS Cut Line= 5
1637218.00084625708309.1505645361637050.59047493708253.175877616
1636775.79765914708315.4925300931636270.99628022708429.969802707
1635298.83067147708608.954665169
#Sta/Elev= 30
       0   50.17   66.43   46.89  169.76   17.72  241.12   15.05  284.19   18.94
  355.96   18.78  420.56   21.35     487   19.95  537.25   23.16  558.78   21.12
  659.27   19.56   745.4   21.49  788.47   18.69  831.53    9.51  881.78    6.94
   907.2    3.27  1004.4    1.37  1013.8    -.63  1027.4    1.37 1042.77    7.25
 1048.61    8.97 1089.79   11.85 1189.44    13.3 1217.91   12.53 1274.85    16.8
 1310.44   12.79 1388.73   10.53 1531.09    9.51 1701.91   20.28 1964.42   24.39
#Mann= 6 ,-1 , 0
       0      .1       0  355.96      .1       0  558.78      .1       0
  831.53     .04       0 1048.61      .1       0 1189.44     .06       0
#XS Ineff= 2 , 0
       0     766      23    1197       0      23
Permanent Ineff=
       F       F
Bank Sta=881.78,1042.77
XS Rating Curve= 0 ,0
Exp/Cntr=0.5,0.3

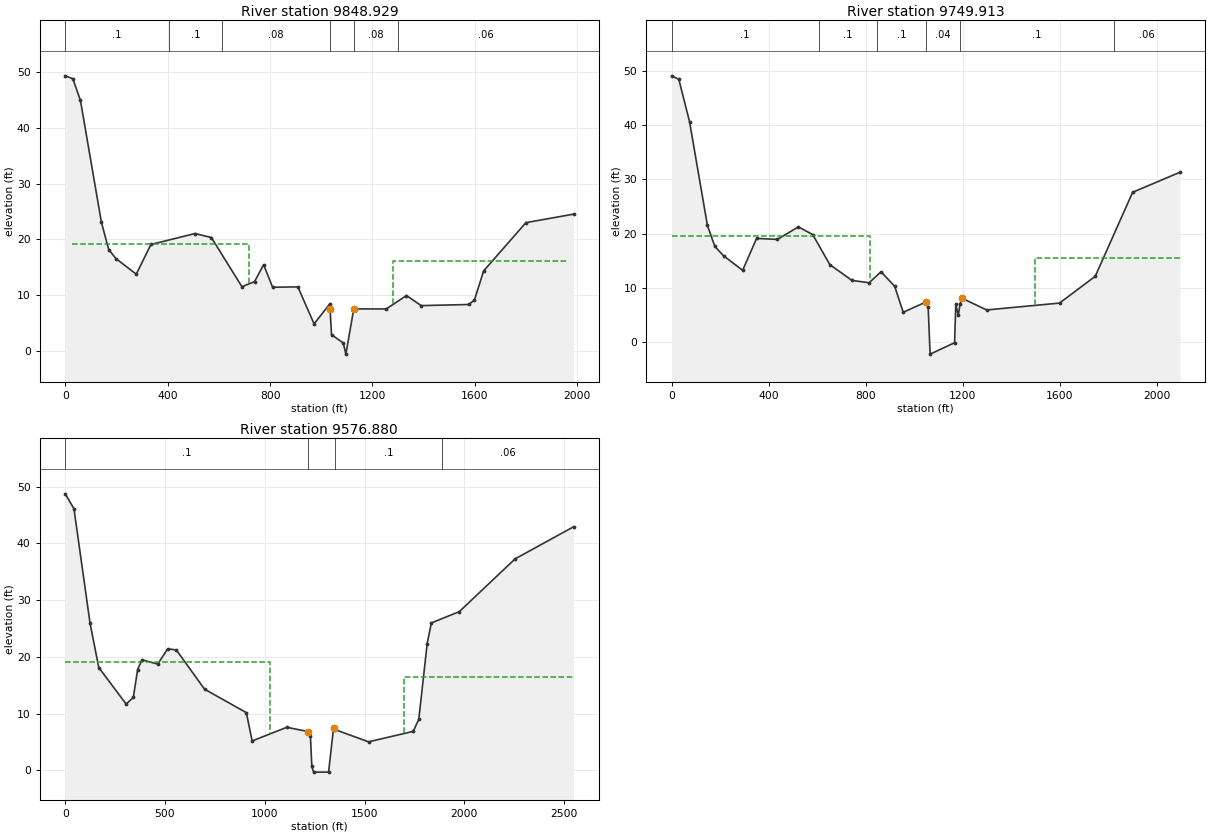
Type RM Length L Ch R = 1 ,9848.929,95.46,99.02,104.05
BEGIN DESCRIPTION:
underwater portion from hec2 section 208.1
END DESCRIPTION:
XS GIS Cut Line= 6
1637253.72944094708295.0816793741637093.90592553708237.366967678
1636716.37430218 708321.155873881636227.28862149708372.188072294
 1636033.9266149708415.7783512621635313.48085377708578.190979481
#Sta/Elev= 30
       0   49.39   29.77   48.87   59.54   44.96  141.41   23.06  169.93   18.15
  198.61   16.53  277.48   13.74  334.84   19.08  506.93   21.04  570.72   20.33
  690.37   11.47  739.63   12.42  774.82   15.45  810.01   11.39  908.54   11.46
  971.89    4.81 1032.97    8.38  1034.2    7.57    1040    2.87    1086    1.37
    1096    -.63 1126.97     7.5 1253.78    7.49 1332.71     9.9 1390.11    8.09
 1576.68    8.29 1598.21    9.11 1634.09   14.33 1799.13      23 1985.12   24.53
#Mann= 6 ,-1 , 0
       0      .1       0  403.77      .1       0  613.11     .08       0
 1032.97     .04       0 1126.97     .08       0 1300.77     .06       0
#XS Ineff= 2 ,-1
   28.08  716.6919.14286    1280 1960.38  16.139
Permanent Ineff=
       F       F
Bank Sta=1034.2,1126.97
XS Rating Curve= 0 ,0
Exp/Cntr=0.3,0.1

Type RM Length L Ch R = 1 ,9749.913,132.08,173.03,177.44
BEGIN DESCRIPTION:
underwater portion from hec2 section 207.5
END DESCRIPTION:
XS GIS Cut Line= 6
1637264.67147899708288.6373709441637095.65499072708232.631907374
1636701.61655056708320.6404929761636235.54032139708269.047607809
1635890.87746014708372.4464661931635205.85754006708331.581730023
#Sta/Elev= 30
       0   49.06    29.5   48.42   73.74    40.6  147.49   21.48  178.05   17.62
  213.92    15.9  292.81   13.21  350.19    19.1  436.26   18.91  522.33   21.22
   581.8   19.81  652.23   14.27  743.79   11.36  814.21   10.92  863.51   12.95
  919.86   10.27  955.07    5.48 1050.73    7.42 1058.03    6.41    1066   -2.23
    1167    -.13    1172    6.97 1182.27    4.89 1189.58    6.99 1196.89    8.09
 1299.21    5.91  1599.9    7.18 1747.16   12.11 1901.44    27.6  2096.8   31.29
#Mann= 6 ,-1 , 0
       0      .1       0   606.4      .1       0   847.5      .1       0
 1050.73     .04       0 1189.58      .1       0 1824.77     .06       0
#XS Ineff= 2 ,-1
  -33.13  816.6419.60635    1500 2145.02  15.555
Permanent Ineff=
       F       F
Bank Sta=1050.73,1196.89
XS Rating Curve= 0 ,0
Exp/Cntr=0.3,0.1

Type RM Length L Ch R = 1 ,9576.880,86.55,62.74,113.73
BEGIN DESCRIPTION:
underwater portion from hec2 section 207.4
END DESCRIPTION:
XS GIS Cut Line= 6
1637282.67101382708279.3640560361637093.46692295708222.087987721
1636690.33708146708315.7932048741636057.60032934 708152.89731735
1635966.81379172708177.6572821591634778.33548109708185.910603747
#Sta/Elev= 30
       0   48.71   43.88   46.08  124.33   25.95  168.22    18.1  305.48   11.66
  341.42   12.85  362.98   17.74  384.54   19.46  463.59   18.71  513.89   21.41
  557.01   21.19   698.3   14.29  907.92   10.15  936.83    5.16 1110.31    7.57
 1218.74    6.81 1229.02    6.03    1236     .67    1245    -.33    1320    -.33
 1344.74    7.44    1352    7.17 1520.04    5.01 1744.04    6.85 1772.04    8.97
 1814.04   22.32 1835.04   25.96 1975.04   27.95 2255.05   37.26 2547.54    42.9
#Mann= 4 ,-1 , 0
       0      .1       0 1218.74     .04       0    1352      .1       0
 1888.68     .06       0
#XS Ineff= 2 ,-1
  -96.06 1028.7319.14286    1700 2553.65  16.416
Permanent Ineff=
       F       F
Bank Sta=1218.74,1344.74
XS Rating Curve= 0 ,0
Exp/Cntr=0.5,0.3