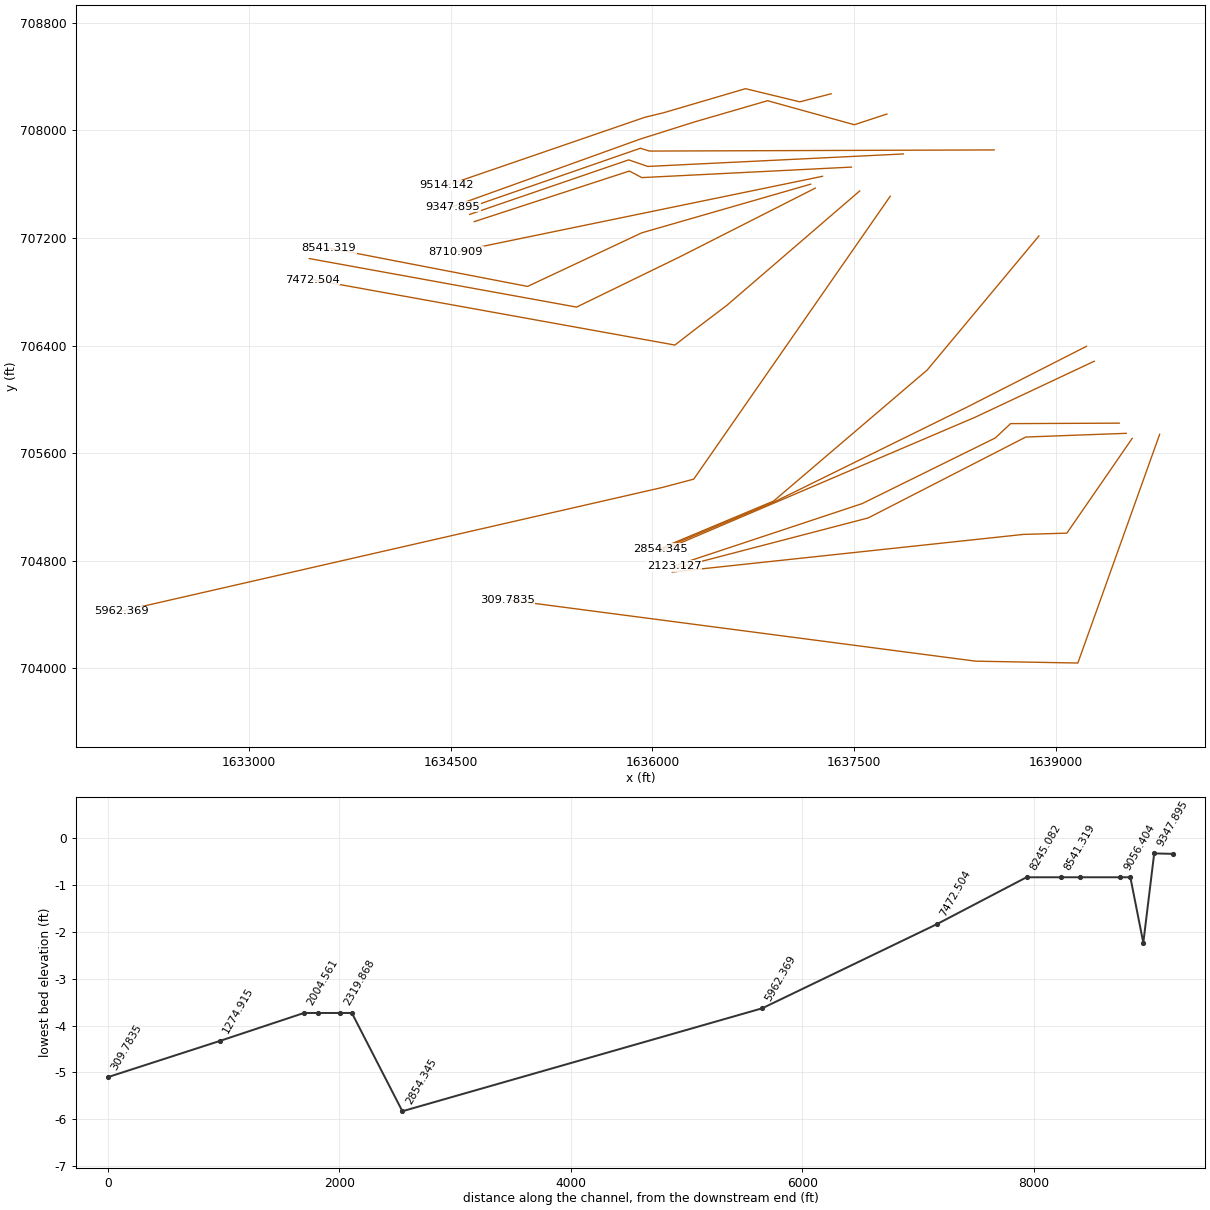
HEC-RAS study LittleElkCreek.prj: Little Elk Creek

--- LittleElkCreek.g01 (geometry) --- (continued)

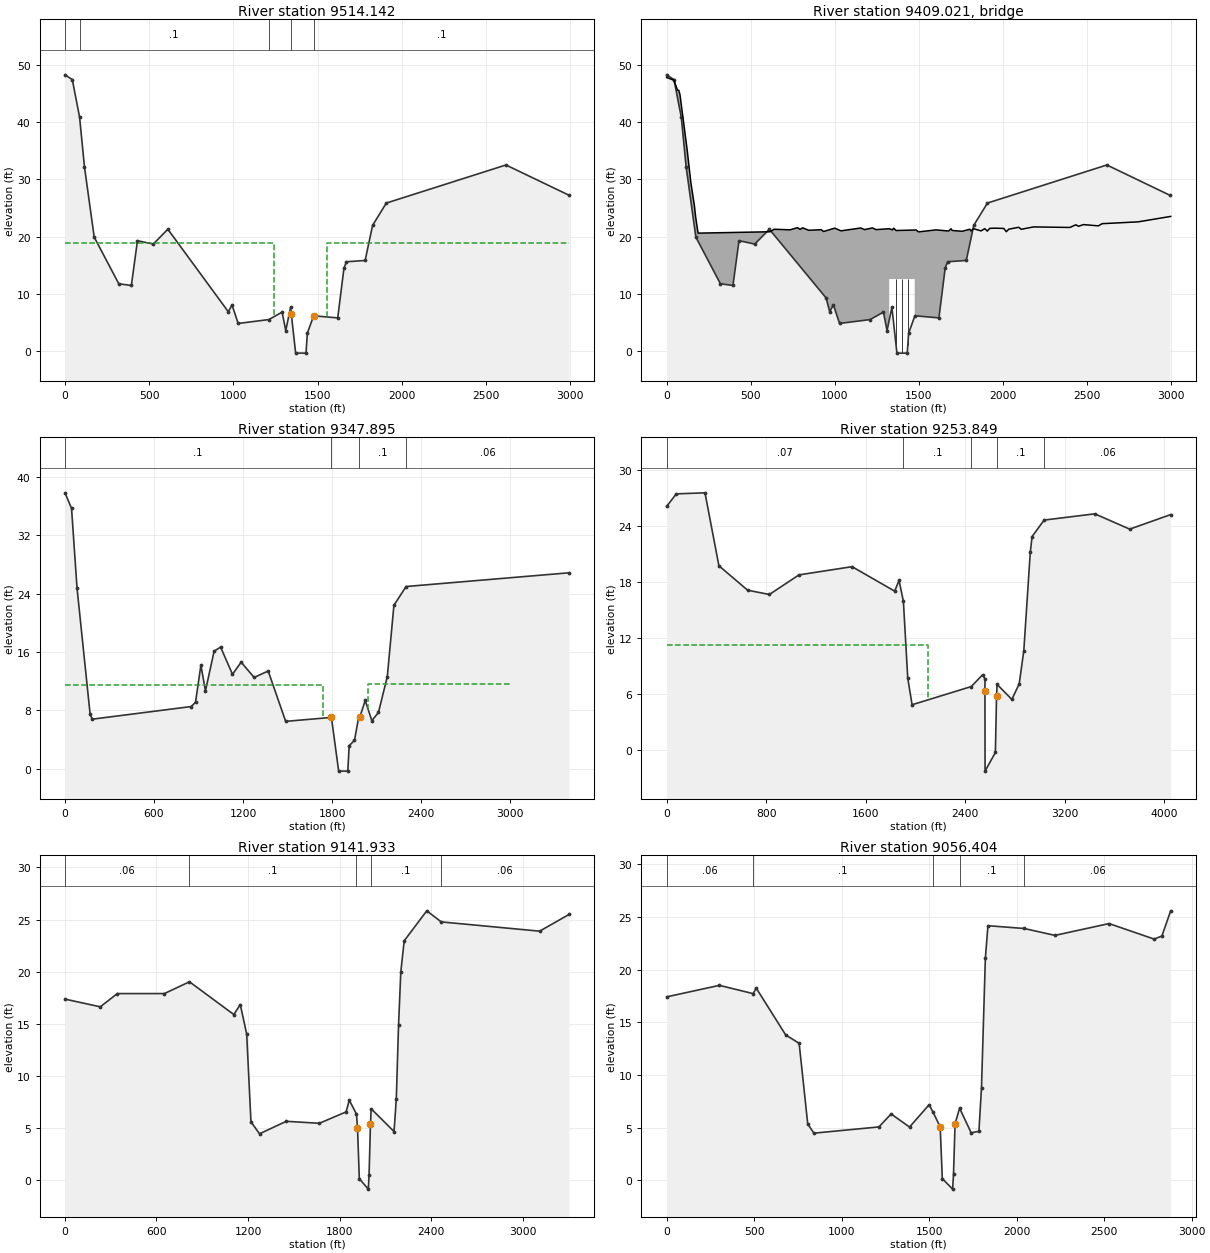
Type RM Length L Ch R = 1 ,9514.142,248.39,166.25,163.93
BEGIN DESCRIPTION:
underwater portion from hec2 section 207.3
END DESCRIPTION:
XS GIS Cut Line= 6
1637329.65026085708272.9285427481637096.55596931708213.078269109
1636692.40573435708310.8980711851636084.89846766 708132.32122919
1635943.75972366708098.0368446411634469.63617587 707591.30687508
#Sta/Elev= 30
       0   48.26   43.36   47.43   86.72   40.87  115.63    32.2  173.45   19.93
  319.55   11.78  394.29   11.48   430.4    19.3  524.27   18.71  610.92    21.3
  970.25    6.89  992.14     8.1 1028.62    4.85 1211.02    5.53 1289.72    6.83
 1311.33    3.61 1340.15    7.66 1344.57    6.43  1370.1    -.33  1431.6    -.33
  1439.8    3.17 1477.17    6.19 1620.02    5.82 1657.03   14.48 1671.83   15.62
 1782.86   15.85 1827.27   21.98 1908.69   25.87 2619.29   32.52 2993.76   27.24
#Mann= 5 ,-1 , 0
       0     .06       0   86.72      .1       0 1211.02     .06       0
 1340.15     .04       0 1477.17      .1       0
#XS Ineff= 2 , 0
       0 1238.81   18.89 1555.97       0   18.89
Permanent Ineff=
       F       F
Bank Sta=1344.57,1477.17
XS Rating Curve= 0 ,0
Exp/Cntr=0.5,0.3

Type RM Length L Ch R = 3 ,9409.021,,,
BEGIN DESCRIPTION:
Conrail RR.  Geometry from HEC2 model section 207.3  Deck elevation from LIDAR.
END DESCRIPTION:
Bridge Culvert--1,0,-1,-1, 0
Deck Dist Width WeirC Skew NumUp NumDn MinLoCord MaxHiCord MaxSubmerge Is_Ogee
85,40,2.6,0, 60, 60, , , 0.98, 0, 0,0,,
       0   43.07   64.61   71.79   78.97  122.04  143.58  165.12  172.29  186.65
  615.37  638.93  734.77     779  793.75  808.49  845.35  919.07  933.82 1000.16
 1037.03 1154.98 1177.09 1224.25 1246.53 1320.791324.125 1343.07 1350.49 1365.35
1475.865 1484.16 1499.02 1602.98 1677.24  1692.1 1699.52 1758.93 1803.49 1810.91
 1825.77 1870.32  1892.6 1907.45 1922.31 1952.01 2005.99  2020.8 2035.61 2094.86
 2109.67 2183.73  2398.5 2435.53 2450.35 2479.97 2568.84 2591.06 2805.83  2999.1
   47.79   47.32   45.57   45.57   44.82   35.11   29.49   25.36   23.46   20.62
   20.86    21.3    21.2   21.58   21.27   21.55   21.12   21.22   20.91   21.49
   21.02   21.52   21.24   21.53   21.23   21.39   21.39   21.19   21.48   21.08
   21.16   21.18   20.84   21.19   20.99   21.38   21.08   20.95    21.3      21
    21.4   21.01    21.4   20.98   21.45   21.49   21.44   20.87   21.31   21.64
   21.29   21.71   21.61   22.08   21.81   22.11   21.89   22.27   22.59   23.54
                                                                                
                                                                                
                                                    12.6    12.6    12.6    12.6
    12.6
                                                                                
                                                                                
       0   43.07   64.61   71.79   78.97  122.04  143.58  165.12  172.29  186.65
  615.37  638.93  734.77     779  793.75  808.49  845.35  919.07  933.82 1000.16
 1037.03 1154.98 1177.09 1224.25 1246.53 1343.07 1350.49 1365.35 1484.16 1499.02
 1602.98 1677.24  1692.1 1699.52 1744.08 1758.93 1803.491809.125 1810.91 1825.77
 1870.32  1892.6 1907.45 1922.311960.865 1961.55 2005.99  2020.8 2035.61 2094.86
 2109.67 2183.73  2398.5 2435.53 2450.35 2479.97 2568.84 2591.06 2805.83  2999.1
   47.79   47.32   45.57   45.57   44.82   35.11   29.49   25.36   23.46   20.62
   20.86    21.3    21.2   21.58   21.27   21.55   21.12   21.22   20.91   21.49
   21.02   21.52   21.24   21.53   21.23   21.19   21.48   21.08   21.18   20.84
   21.19   20.99   21.38   21.08   21.22   20.95    21.3    21.3      21    21.4
   21.01    21.4   20.98   21.45   21.38   21.38   21.44   20.87   21.31   21.64
   21.29   21.71   21.61   22.08   21.81   22.11   21.89   22.27   22.59   23.54
                                                                                
                                                                                
                                                                                
                                                            12.6    12.6    12.6
    12.6    12.6    12.6    12.6    12.6
                                                                                
Pier Skew, UpSta & Num, DnSta & Num=  ,1365, 4 ,1850, 4 , 0 , 0 , 0 ,,
    3.25    3.25     2.5     2.5
       0     6.7     6.7    12.7
    3.25    3.25     2.5     2.5
       0     6.7     6.7    12.7
Pier Skew, UpSta & Num, DnSta & Num=  ,1400, 4 ,1885, 4 , 0 , 0 , 0 ,,
    3.25    3.25     2.5     2.5
       0     6.7     6.7    12.7
    3.25    3.25     2.5     2.5
       0     6.7     6.7    12.7
Pier Skew, UpSta & Num, DnSta & Num=  ,1435, 4 ,1920, 4 , 0 , 0 , 0 ,,
    3.25    3.25     2.5     2.5
       0     6.7     6.7    12.7
    3.25    3.25     2.5     2.5
       0     6.7     6.7    12.7
BR Coef=-1 , 1 , 0 ,, 0 ,,,0.8,0,1.2,0,
WSPro=,,,, 1 ,,,, 0 ,,,, 0 ,,,,-1 ,-1 ,-1 , 0 , 0 , 0 , 0 , 0
BR U #Sta/Elev= 30
       0   48.26   43.36   47.43   86.72   40.87  115.63    32.2  173.45   19.93
  319.55   11.78  394.29   11.48   430.4    19.3  524.27   18.71  610.92    21.3
  948.36    9.31  970.25    6.89  992.14     8.1 1028.62    4.85 1211.02    5.53
 1289.72    6.83 1311.33    3.61 1340.15    7.66  1370.1    -.33  1431.6    -.33
  1439.8    3.17 1477.17    6.19 1620.02    5.82 1657.03   14.48 1671.83   15.62
 1782.86   15.85 1827.27   21.98 1908.69   25.87 2619.29   32.52 2993.76   27.24
BR U #Mann= 5
       0     .06   86.72      .1 1211.02     .06 1340.15    .038 1477.17      .1
BR D #Sta/Elev= 30
       0   37.82   44.21   35.69   81.05   24.78  169.47    7.46   184.2     6.8
  850.52    8.53  879.58    9.12   915.9    14.2   946.5   10.67 1004.82   16.12
 1048.55   16.68 1128.74   12.95 1187.05   14.61 1274.52   12.52 1369.28    13.4
 1487.07     6.5 1795.36    7.04 1844.24    -.32 1905.75    -.32 1915.04    3.17
  1950.8    3.89 1951.27    6.11 1978.51    7.02 2023.15    9.37 2067.79     6.6
 2112.43    7.72 2171.94   12.64 2216.58   22.41 2298.42   24.98 3396.22   26.86
BR D #Mann= 4
       0      .1 1795.36    .038 1978.51      .1 2298.42     .06
BC Design=,, 0 ,, 0 ,,,,,,
BC Use User HTab Curves=0
BC User HTab FreeFlow(D)= 0

Type RM Length L Ch R = 1 ,9347.895,127.75,94.04,80.23
BEGIN DESCRIPTION:
underwater portion from hec2 section 207.2
END DESCRIPTION:
XS GIS Cut Line= 6
1637744.18379956708122.2161466931637502.00776157708042.644019932
1636856.58496095708221.4150390631636316.47846156708064.534036741
1635911.68008515707936.7520876381634514.75764555707433.860009387
#Sta/Elev= 30
       0   37.82   44.21   35.69   81.05   24.78  169.47    7.46   184.2     6.8
  850.52    8.53  879.58    9.12   915.9    14.2   946.5   10.67 1004.82   16.12
 1048.55   16.68 1128.74   12.95 1187.05   14.61 1274.52   12.52 1369.28    13.4
 1487.07     6.5 1795.36    7.04 1844.24    -.32 1905.75    -.32 1915.04    3.17
  1950.8    3.89 1978.51    7.02 1985.95    7.04 2023.15    9.37 2067.79     6.6
 2112.43    7.72 2171.94   12.64 2216.58   22.41 2298.42   24.98 3396.22   26.86
#Mann= 4 ,-1 , 0
       0      .1       0 1795.36     .04       0 1978.51      .1       0
 2298.42     .06       0
#XS Ineff= 2 ,-1
   -2.76 1737.2411.48163 2044.98    3000 11.5615
Permanent Ineff=
       F       F
Bank Sta=1795.36,1985.95
XS Rating Curve= 0 ,0
Exp/Cntr=0.5,0.3

Type RM Length L Ch R = 1 ,9253.849,111.76,111.92,67.89
BEGIN DESCRIPTION:
underwater portion from 207
END DESCRIPTION:
XS GIS Cut Line= 4
1638542.73541248707855.2305368331635977.26253153707846.765785351
1635910.25691575707867.7050402911634570.14459956707402.853580624
#Sta/Elev= 30
       0   26.13      77   27.47     308   27.58     420   19.77     651   17.15
  826.01   16.69 1064.01   18.79 1491.01   19.67 1834.01   17.05 1869.01    18.2
 1904.01   15.97 1939.01    7.74 1974.01    4.88 2450.01    6.83 2541.01    8.09
 2560.09    7.66 2560.11    6.34    2561   -2.23    2644    -.23  2653.4    5.82
 2657.91    7.06 2776.45    5.45 2835.73    7.12 2872.77   10.68 2924.64    21.2
 2939.46    22.9 3035.78   24.66 3443.28   25.33 3724.83   23.69 4054.13   25.25
#Mann= 5 ,-1 , 0
       0     .07       0 1904.01      .1       0 2450.01     .04       0
  2653.4      .1       0 3035.78     .06       0
#XS Ineff= 1 ,-1
       0    210011.24513
Permanent Ineff=
       F
Bank Sta=2560.11,2653.4
XS Rating Curve= 0 ,0
Exp/Cntr=0.3,0.1

Type RM Length L Ch R = 1 ,9141.933,83.78,85.53,101.31
BEGIN DESCRIPTION:
underwater portion from hec2 section 206.04
END DESCRIPTION:
XS GIS Cut Line= 4
1637866.71690178707825.2190646831635964.95427376707732.330915764
1635823.17762542707781.2194152031634640.07593907707375.444869891
#Sta/Elev= 30
       0   17.38  231.28   16.64  343.41   17.91  651.78   17.91  816.27   19.04
 1107.32    15.9 1149.37   16.86 1191.42   14.03 1219.45    5.62 1275.52    4.47
 1450.73    5.67 1667.98    5.48 1843.19    6.57 1864.22    7.69 1911.43    6.36
    1918    5.07    1930     .17    1989    -.83    1994     .57    2003    5.37
 2007.69    6.87  2157.6    4.69  2172.4    7.79  2187.2    14.9    2202   19.99
  2224.2   22.97  2372.2   25.84 2467.3124.77884 3112.22   23.89 3304.73   25.49
#Mann= 5 ,-1 , 0
       0     .06       0  816.27      .1       0 1911.43     .04       0
 2007.69      .1       0 2467.31     .06       0
Bank Sta=1918,2003
XS Rating Curve= 0 ,0
Exp/Cntr=0.3,0.1

Type RM Length L Ch R = 1 ,9056.404,255,345.5,348.1
BEGIN DESCRIPTION:
underwater portion from hec2 section 206.03
END DESCRIPTION:
XS GIS Cut Line= 4
1637480.49775621707727.4420658051635920.95462424707649.220466703
1635828.06647535707698.1089661421634674.29788868707321.667520493
#Sta/Elev= 30
       0   17.41  301.38    18.5  494.2317.71503  511.64   18.24  679.85    13.8
  756.95      13  806.01    5.35  841.06    4.48 1212.52    5.07 1282.61     6.3
 1387.74    5.06 1499.88    7.18 1520.91    6.51    1563    5.07    1575     .17
    1634    -.83    1639     .57    1648    5.37 1673.83    6.85  1740.1    4.51
 1784.28    4.66 1799.01    8.79  1821.1   21.09 1835.82   24.16 2042.8623.89409
 2218.71   23.24 2527.97   24.36 2785.68   22.89 2829.86   23.18 2880.11   25.57
#Mann= 5 ,-1 , 0
       0     .06       0  494.23      .1       0 1520.91     .04       0
 1673.83      .1       0 2042.86     .06       0
Bank Sta=1563,1648
XS Rating Curve= 0 ,0
Exp/Cntr=0.3,0.1

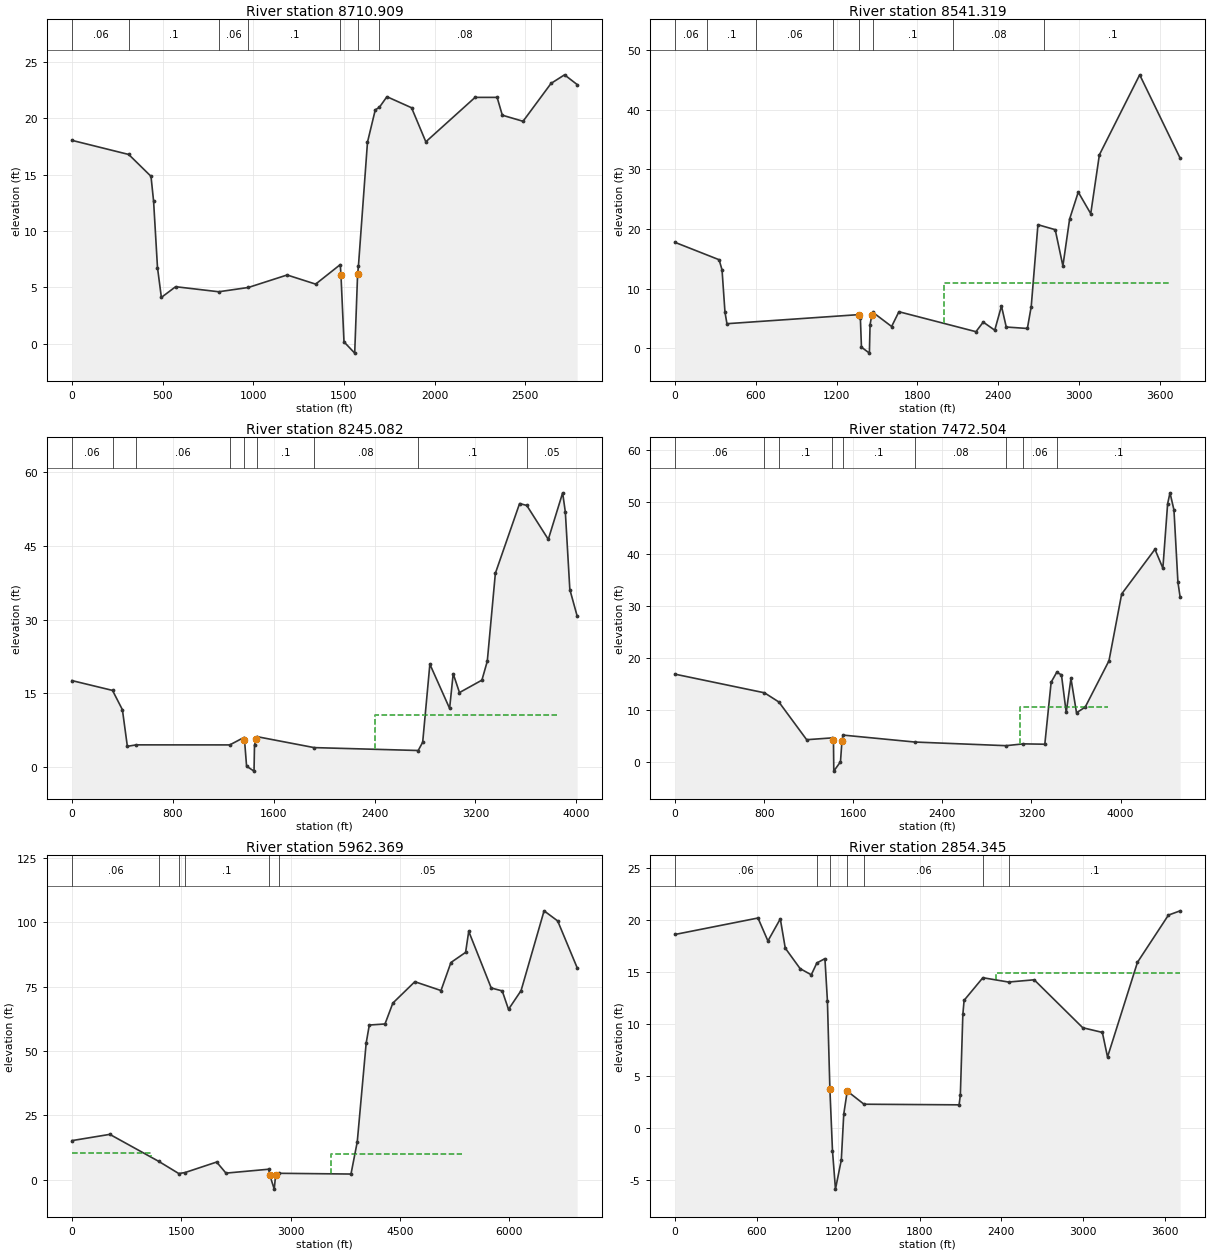
Type RM Length L Ch R = 1 ,8710.909,131.31,169.59,184.21
BEGIN DESCRIPTION:
underwater portion from section 206.02
END DESCRIPTION:
XS GIS Cut Line= 2
1637265.38835873707658.9981665911634537.41009027 707096.78042312
#Sta/Elev= 30
       0   18.04  313.0716.78725  435.97   14.85  450.27   12.64  471.71    6.76
  493.15    4.11  571.77    5.06  809.414.612462  972.634.992157 1186.42     6.1
 1343.66    5.29 1479.45    7.02 1483.23    6.12    1500     .17    1559    -.83
 1575.06    6.19 1579.51    6.87 1629.54   17.88 1672.42   20.74 1695.1420.97223
 1736.75   21.91 1872.54   20.93 1951.16   17.91 2222.75   21.85 2344.25   21.85
 2372.84   20.27  2487.2   19.73 2641.5923.09035 2715.91   23.85 2785.32   22.99
#Mann= 8 ,-1 , 0
       0     .06       0  313.07      .1       0  809.41     .06       0
  972.63      .1       0 1479.45     .04       0 1579.51      .1       0
 1695.14     .08       0 2641.59      .1       0
Bank Sta=1483.23,1575.06
XS Rating Curve= 0 ,0
Exp/Cntr=0.3,0.1

Type RM Length L Ch R = 1 ,8541.319,268.75,296.24,291.81
BEGIN DESCRIPTION:
underwater portion from hec2 section 206.01
END DESCRIPTION:
XS GIS Cut Line= 4
1637177.38905971707600.3319673091635920.95462424707238.557071477
1635070.86856116706839.5835769181633592.84370638707124.926317796
#Sta/Elev= 30
       0   17.77   327.8   14.85  349.65   13.15   371.5    6.04  386.07    4.11
 1369.35    5.64 1377.08    5.01    1385     .17    1444    -.83 1448.96    3.94
 1462.14    5.57 1469.87    6.02 1609.06    3.64 1663.19    6.12  2235.4    2.77
 2289.32    4.38 2374.87    3.02 2424.77    7.08 2460.42    3.55 2617.26    3.31
 2645.78    6.98 2695.68   20.73 2824.01   19.89 2881.04   13.81 2930.94   21.68
 2995.11    26.2 3087.79   22.58 3151.95   32.46 3451.37   45.89 3751.84   31.89
#Mann= 8 ,-1 , 0
       0     .06       0  237.93      .1       0  604.37     .06       0
 1173.87      .1       0 1369.35     .04       0 1469.87      .1       0
  2061.7     .08       0 2744.28      .1       0
#XS Ineff= 1 ,-1
    2000 3671.7710.93533
Permanent Ineff=
       F
Bank Sta=1369.35,1462.14
XS Rating Curve= 0 ,0
Exp/Cntr=0.3,0.1

Type RM Length L Ch R = 1 ,8245.082,559.98,772.58,586.99
BEGIN DESCRIPTION:
underwater portion from hec2 section 206
END DESCRIPTION:
XS GIS Cut Line= 4
1637211.61100931707570.9988676161636199.61907105707057.669623554
1635435.50466412706685.7812429961633446.59566508707046.927362442
#Sta/Elev= 30
       0   17.61  321.81   15.61   400.3   11.68  439.55    4.22  510.19    4.52
 1251.52    4.51 1360.51    5.98 1368.29     5.6    1385     .17    1444    -.83
 1447.76     4.5 1461.71     5.7  1469.5    6.18 1921.03    3.96  2745.8    3.37
 2781.37    5.06 2838.29   20.95 2994.81   11.94 3023.27   19.01 3073.07   15.17
 3250.93    17.7 3293.62   21.55 3357.65   39.46 3549.74   53.67 3606.65   53.28
  3777.4   46.37 3891.23   55.85 3912.58   51.91 3948.15   36.16 4005.99   30.78
#Mann= 9 ,-1 , 0
       0     .06       0  321.81      .1       0  510.19     .06       0
 1251.52      .1       0 1360.51     .04       0  1469.5      .1       0
 1921.03     .08       0  2745.8      .1       0 3606.65     .05       0
#XS Ineff= 1 ,-1
    2400 3845.95    10.5
Permanent Ineff=
       F
Bank Sta=1368.29,1461.71
XS Rating Curve= 0 ,0
Exp/Cntr=0.3,0.1

Type RM Length L Ch R = 1 ,7472.504,1283.96,1510.14,1109.43
BEGIN DESCRIPTION:
underwater portion from hec2 section 205
END DESCRIPTION:
XS GIS Cut Line= 5
 1637542.0972655707549.9768128691636552.46926525706697.872932389
1636331.11701614706530.3631222841636166.80923326706403.435980737
1633466.09540391706890.929451719
#Sta/Elev= 30
       0   16.84  803.65   13.25  932.97   11.48 1182.37    4.22 1411.27    4.57
    1423    4.07    1426   -1.83    1486    -.03 1499.05    3.89 1507.83    5.11
 2153.91    3.77 2971.91    3.07  3128.4    3.42 3320.45    3.35 3377.35    15.3
 3427.14   17.19 3469.82   16.71  3512.5    9.46 3555.18   16.02 3604.97     9.4
 3683.21    10.5  3896.6   19.42 4010.41   32.28 4309.17   40.88  4380.3   37.24
 4422.98   49.64 4444.32   51.75 4479.89   48.45 4515.45   34.55 4535.48   31.64
#Mann= 9 ,-1 , 0
       0     .06       0  803.65      .1       0  932.97      .1       0
 1411.27     .04       0 1507.83      .1       0 2153.91     .08       0
 2971.91      .1       0  3128.4     .06       0 3427.14      .1       0
#XS Ineff= 1 ,-1
    3100 3886.17    10.5
Permanent Ineff=
       F
Bank Sta=1423,1499.05
XS Rating Curve= 0 ,0
Exp/Cntr=0.3,0.1

Type RM Length L Ch R = 1 ,5962.369,2315.13,3108.02,2712.55
BEGIN DESCRIPTION:
underwater portion from hec2 section 204
END DESCRIPTION:
XS GIS Cut Line= 4
1637769.29005411707510.7893129891636307.18704328 705405.65439716
1636075.78202462705344.3187707511632049.80025665704423.528514624
#Sta/Elev= 30
       0   15.21  519.89   17.64 1193.18    7.12 1465.91    2.43 1551.13     2.8
 1985.79    6.89 2113.63    2.59 2700.66     4.1 2713.32    1.96    2776   -3.63
  2794.8     1.7 2838.36    2.52  3829.3    2.23 3915.46   14.76 4037.53   53.06
 4080.62    60.1 4296.04   60.52 4403.75   68.63 4705.34   76.93 5064.37    73.5
  5200.8   84.39 5401.86   88.32 5444.94   96.49 5753.71   74.49 5904.51   73.36
 5990.68    66.2 6163.01   73.46 6478.96  104.46 6665.66  100.53 6932.35   82.38
#Mann= 6 ,-1 , 0
       0     .06       0 1193.18      .1       0 1465.91     .06       0
 1551.13      .1       0 2700.66    .035       0 2838.36     .05       0
#XS Ineff= 2 ,-1
    -3.61081.735  10.208 3552.45 5352.4510.19978
Permanent Ineff=
       F       F
Bank Sta=2713.32,2794.8
XS Rating Curve= 0 ,0
Exp/Cntr=0.3,0.1

Type RM Length L Ch R = 1 ,2854.345,466.13,436.37,400.52
BEGIN DESCRIPTION:
underwater portion from hec2 section 203
END DESCRIPTION:
XS GIS Cut Line= 4
1638875.43738921707214.8577396571638044.77041292706218.057368055
1636901.31251782705242.4460756781636058.82089826704889.625981182
#Sta/Elev= 30
       0   18.61   610.5   20.19   683.4   17.99  774.52   20.11  810.96    17.3
  920.31   15.33 1002.31   14.74 1043.2715.87891 1102.55   16.29 1120.77   12.26
 1138.99    3.78    1158   -2.13    1180   -5.83    1223   -3.03    1241    1.37
 1266.56    3.58 1389.79   2.319 2088.88    2.26 2098.09    3.19 2116.49   10.94
 2125.69   12.29 2263.7114.45992 2452.3814.04497 2640.98   14.26 2997.96    9.66
 3142.15    9.21  3180.1    6.85 3400.18   15.94 3627.86   20.47 3714.04   20.88
#Mann= 7 ,-1 , 0
       0     .06       0 1043.27      .1       0 1138.99    .035       0
 1266.56     .11       0 1389.79     .06       0 2263.71      .1       0
 2452.38      .1       0
#XS Ineff= 2 , 0
                         2358.21           14.92
Permanent Ineff=
       F       F
Bank Sta=1138.99,1266.56
XS Rating Curve= 0 ,0
Exp/Cntr=0.3,0.1

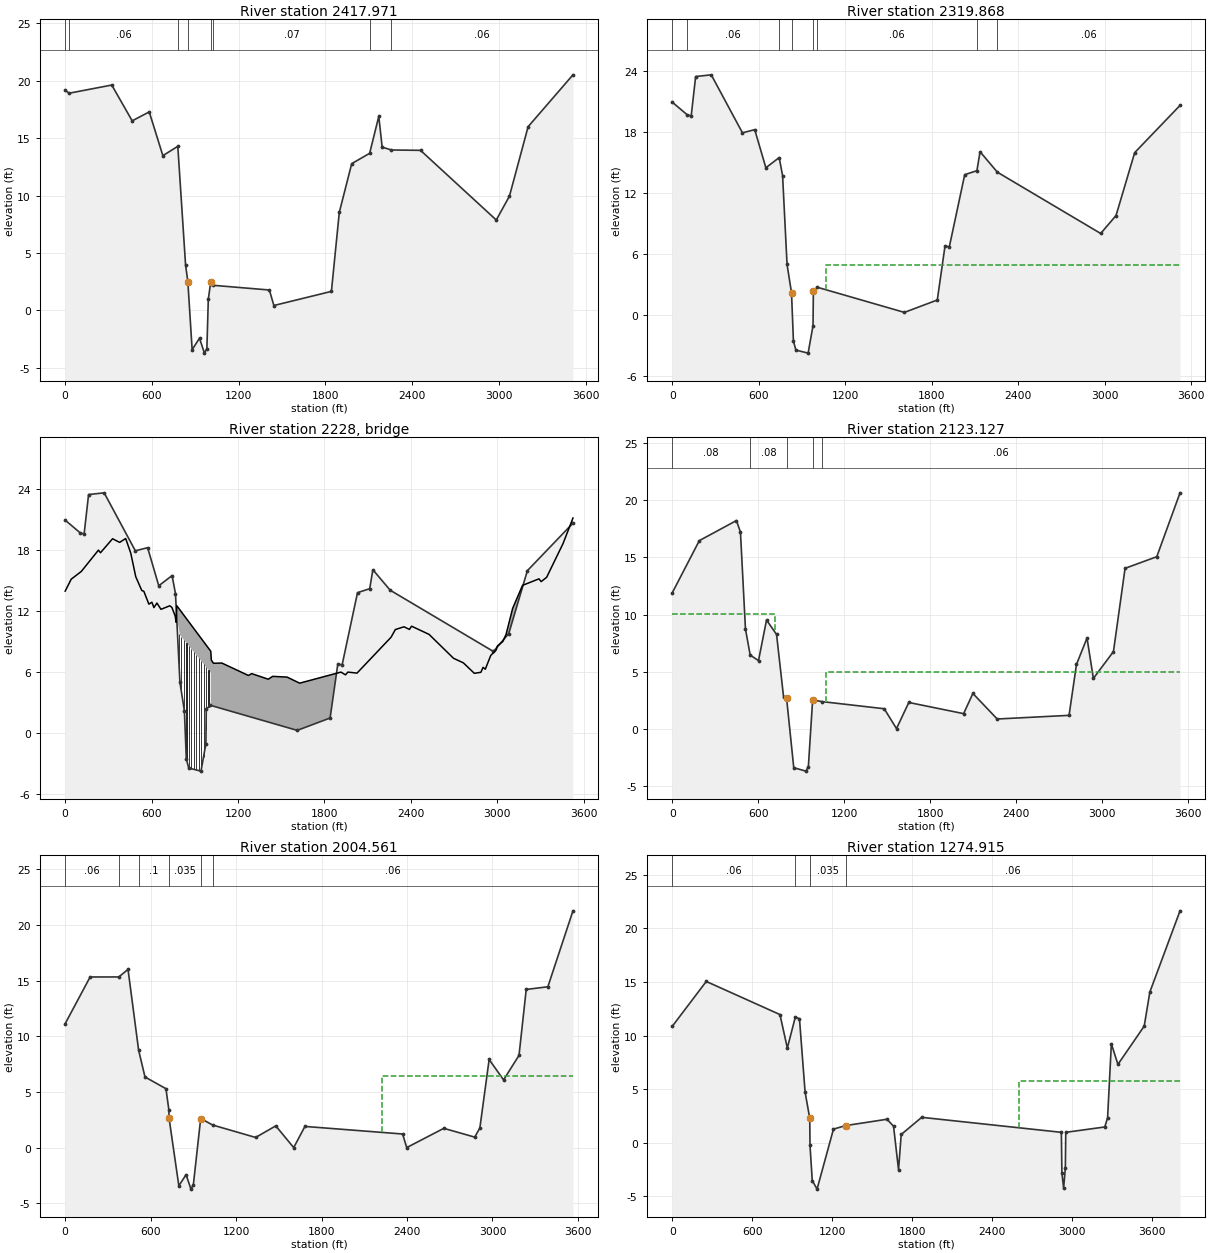
Type RM Length L Ch R = 1 ,2417.971,106.58,98.1,97.95
BEGIN DESCRIPTION:
underwater portion from hec2 section 202.4
END DESCRIPTION:
XS GIS Cut Line= 4
1639229.72640872706394.2257087381638339.74842578 705941.07178165
1636908.08282954 705236.992193491636062.04079492704881.740141869
#Sta/Elev= 30
       0   19.18   27.3918.91759  322.06   19.63  463.45   16.51  581.28   17.29
  675.54   13.48   778.914.28799  832.65    3.94  848.36    2.49     878   -3.43
     929   -2.43     963   -3.73     980   -3.33  989.75     .95  1006.5    2.47
 1022.622.180846 1412.14    1.77 1443.34     .42 1841.17    1.65 1895.78    8.54
 1981.59   12.78 2105.6313.68172  2168.8    16.9 2192.21   14.22 2256.2913.97015
 2457.43   13.94 2981.33    7.87 3072.43    9.95 3201.49      16 3511.73   20.52
#Mann= 8 ,-1 , 0
       0     .06       0   27.39     .06       0   778.9      .1       0
  848.36    .035       0  1006.5     .06       0 1022.62     .07       0
 2105.63      .1       0 2256.29     .06       0
Bank Sta=848.36,1006.5
XS Rating Curve= 0 ,0
Exp/Cntr=0.5,0.3

Type RM Length L Ch R = 1 ,2319.868,181.24,196.74,212.96
BEGIN DESCRIPTION:
underwater portion from hec2 section 202.4
END DESCRIPTION:
XS GIS Cut Line= 3
1639287.41364653706283.1959024821638401.05966985705866.306374997
1636060.67896421704867.569536015
#Sta/Elev= 30
       0   20.98  104.6719.72841  131.51   19.62  162.45    23.5  270.75   23.67
  487.34   17.96  572.44   18.27  649.79   14.52  742.1715.52291  765.83   13.75
  796.77       5  827.71    2.22     841   -2.53     858   -3.43     943   -3.73
     977   -1.03   979.5    2.36 1007.192.754205 1611.19     .28 1839.51     1.5
 1892.78    6.79 1923.23    6.75 2029.78   13.84 2114.4514.23111 2136.33    16.1
 2256.4714.08428 2973.52    8.05 3080.07    9.82 3209.46   16.01 3524.09   20.66
#Mann= 8 ,-1 , 0
       0     .06       0  104.67     .06       0  742.17     .08       0
  827.71    .035       0   979.5     .06       0 1007.19     .06       0
 2114.45      .1       0 2256.47     .06       0
#XS Ineff= 2 , 0
       0     710   11.79 1069.01       0    4.93
Permanent Ineff=
       F       F
Bank Sta=827.71,979.5
XS Rating Curve= 0 ,0
Exp/Cntr=0.5,0.3

Type RM Length L Ch R = 3 ,2228    ,,,
BEGIN DESCRIPTION:
Old Field Point, Geom from HEC2 model section 202.3.  Top of road from LIDAR.
END DESCRIPTION:
Bridge Culvert--1,0,-1,-1, 0
Deck Dist Width WeirC Skew NumUp NumDn MinLoCord MaxHiCord MaxSubmerge Is_Ogee
60,30,2.6,0, 60, 60, , , 0.95, 0, 0,0,,
       0      42     112     231     245     329     378     420     455     490
  532.01  546.01  581.01  602.01  616.01  637.01  665.01  726.47  741.26  763.43
  770.82   774.2    1011 1014.76 1029.54 1087.92 1271.93 1294.93 1409.94  1440.6
 1540.28 1628.09 1914.77 1946.62 1962.55 2026.26 2262.55 2292.57 2352.61 2390.14
 2405.15  2526.8 2696.23  2764.7 2840.77 2886.41 2901.63 2916.84 2954.88 2992.91
 3000.52 3038.56 3061.38 3107.02 3175.49 3289.59 3304.81 3342.84 3456.95 3525.71
   13.99   15.17   15.93   18.03   17.77   19.15   18.79   19.17   17.75   15.41
   14.05   13.98   12.71    12.9   12.37   12.82    12.2   12.55   12.38   11.55
   10.92   12.57    8.07     7.2    6.89    6.91    5.69    5.87    5.32     5.6
    5.53    4.93    6.02    5.75    6.02    5.92    9.45   10.21   10.48   10.22
   10.54    9.73    7.38    6.93     5.9       6    6.49     6.3    7.66     8.2
    8.58    9.03    9.74    12.3   14.56    15.2   14.93   15.35   18.68   21.19
                                                                                
                                                                                
           10.07    5.97
                                                                                
                                                                                
                                                                                
       0      42     112     231     245     329     378     420     455     490
  532.01  546.01  581.01  602.01  616.01  637.01  665.01  726.47  741.26  763.43
  770.82   774.2    1011 1014.76 1029.54 1271.93 1294.93 1409.94  1440.6 1540.28
 1628.09 1914.77 1946.62 1962.55 2026.26 2262.55 2292.57 2352.61 2390.14 2405.15
  2526.8 2696.23  2764.7 2840.77 2886.41 2901.63 2916.84 2954.88 2992.91 3000.52
 3038.56 3061.38 3107.02 3175.49 3289.59 3304.81 3342.84 3456.95 3517.81 3543.62
   13.99   15.17   15.93   18.03   17.77   19.15   18.79   19.17   17.75   15.41
   14.05   13.98   12.71    12.9   12.37   12.82    12.2   12.55   12.38   11.55
   10.92   12.57    8.07     7.2    6.89    5.69    5.87    5.32     5.6    5.53
    4.93    6.02    5.75    6.02    5.92    9.45   10.21   10.48   10.22   10.54
    9.73    7.38    6.93     5.9       6    6.49     6.3    7.66     8.2    8.58
    9.03    9.74    12.3   14.56    15.2   14.93   15.35   18.68   21.02   21.19
                                                                                
                                                                                
           10.07    5.97
                                                                                
                                                                                
                                                                                
Pier Skew, UpSta & Num, DnSta & Num=  ,790.5, 2 ,790.5, 2 , 0 , 0 , 0 ,,
       1       1
       0    10.5
       1       1
       0    10.5
Pier Skew, UpSta & Num, DnSta & Num=  ,807, 2 ,807, 2 , 0 , 0 , 0 ,,
       1       1
       0    10.5
       1       1
       0    10.5
Pier Skew, UpSta & Num, DnSta & Num=  ,825, 2 ,825, 2 , 0 , 0 , 0 ,,
       1       1
       0    10.5
       1       1
       0    10.5
Pier Skew, UpSta & Num, DnSta & Num=  ,842, 2 ,842, 2 , 0 , 0 , 0 ,,
       1       1
       0    10.5
       1       1
       0    10.5
Pier Skew, UpSta & Num, DnSta & Num=  ,859, 2 ,859, 2 , 0 , 0 , 0 ,,
       1       1
       0    10.5
       1       1
       0    10.5
Pier Skew, UpSta & Num, DnSta & Num=  ,876, 2 ,876, 2 , 0 , 0 , 0 ,,
       1       1
       0    10.5
       1       1
       0    10.5
Pier Skew, UpSta & Num, DnSta & Num=  ,893, 2 ,893, 2 , 0 , 0 , 0 ,,
       1       1
       0    10.5
       1       1
       0    10.5
Pier Skew, UpSta & Num, DnSta & Num=  ,910, 2 ,910, 2 , 0 , 0 , 0 ,,
       1       1
       0    10.5
       1       1
       0    10.5
Pier Skew, UpSta & Num, DnSta & Num=  ,927, 2 ,927, 2 , 0 , 0 , 0 ,,
       1       1
       0    10.5
       1       1
       0    10.5
Pier Skew, UpSta & Num, DnSta & Num=  ,944, 2 ,944, 2 , 0 , 0 , 0 ,,
       1       1
       0    10.5
       1       1
       0    10.5
Pier Skew, UpSta & Num, DnSta & Num=  ,961, 2 ,961, 2 , 0 , 0 , 0 ,,
       1       1
       0    10.5
       1       1
       0    10.5
Pier Skew, UpSta & Num, DnSta & Num=  ,978, 2 ,978, 2 , 0 , 0 , 0 ,,
       1       1
       0    10.5
       1       1
       0    10.5
Pier Skew, UpSta & Num, DnSta & Num=  ,995, 2 ,995, 2 , 0 , 0 , 0 ,,
       1       1
       0    10.5
       1       1
       0    10.5
BR Coef=-1 , 1 , 0 ,, 0 ,,,0.8,0,0.5,0,
WSPro=,,,, 1 ,,,, 0 ,,,, 0 ,,,,-1 ,-1 ,-1 , 0 , 0 , 0 , 0 , 0
BR U #Sta/Elev= 30
       0   20.98  104.67  19.728  131.51   19.62  162.45    23.5  270.75   23.67
  487.34   17.96  572.44   18.27  649.79   14.52  742.17  15.523  765.83   13.75
  796.77       5  827.71    2.22     841   -2.53     858   -3.43     943   -3.73
     977   -1.03   979.5    2.36 1007.19   2.754 1611.19     .28 1839.51     1.5
 1892.78    6.79 1923.23    6.75 2029.78   13.84 2114.45  14.231 2136.33    16.1
 2256.47  14.084 2973.52    8.05 3080.07    9.82 3209.46   16.01 3524.09   20.66
BR U #Mann= 8
       0     .06  104.67     .06  742.17     .08  827.71    .032   979.5     .06
 1007.19     .06 2114.45      .1 2256.47     .06
BR D #Sta/Elev= 30
       0    11.9     189   16.48     448   18.24     476   17.23     511    8.73
  543.94   6.445  602.01    5.96  658.01    9.52  728.01    8.25  777.01    2.77
  798.01    2.65     848   -3.43     933   -3.73     950   -3.33  979.71    2.51
 1047.49   2.362  1479.2    1.74 1565.05       0  1650.9    2.29 2033.33    1.31
 2098.12    3.08 2267.75     .84 2769.25    1.16 2820.87    5.62 2894.62    7.94
 2938.87     4.4    3079    6.75 3160.12   14.05 3381.37   15.07 3543.62   20.67
BR D #Mann= 5
       0     .08  543.94     .08  798.01    .032  979.71     .06 1047.49     .06
BC Design=,, 0 ,, 0 ,,,,,,
BC Use User HTab Curves=0
BC User HTab FreeFlow(D)= 0

Type RM Length L Ch R = 1 ,2123.127,210.55,118.57,99.08
BEGIN DESCRIPTION:
underwater portion from hec2 section 202.1
END DESCRIPTION:
XS GIS Cut Line= 5
1639473.16207594705822.2646146861638664.81242943705818.824828938
1638551.29950035705712.1914713231637560.64121014705223.741897702
1636160.64841814704759.370824173
#Sta/Elev= 30
       0    11.9     189   16.48     448   18.24     476   17.23     511    8.73
  543.946.445371  602.01    5.96  658.01    9.52  728.01    8.25  777.01    2.77
  798.01    2.65     848   -3.43     933   -3.73     950   -3.33  979.71    2.51
 1047.49   2.362  1479.2    1.74 1565.05       0  1650.9    2.29 2033.33    1.31
 2098.12    3.08 2267.75     .84 2769.25    1.16 2820.87    5.62 2894.62    7.94
 2938.87     4.4    3079    6.75 3160.12   14.05 3381.37   15.07 3543.62   20.67
#Mann= 5 ,-1 , 0
       0     .08       0  543.94     .08       0  798.01    .035       0
  979.71     .06       0 1047.49     .06       0
#XS Ineff= 2 , 0
       0   714.2   10.07    1071       0    4.93
Permanent Ineff=
       F       F
Bank Sta=798.01,979.71
XS Rating Curve= 0 ,0
Exp/Cntr=0.5,0.3

Type RM Length L Ch R = 1 ,2004.561,749.32,729.65,672.04
BEGIN DESCRIPTION:
underwater portion from hec2 section 202.1
END DESCRIPTION:
XS GIS Cut Line= 4
1639524.75886185705746.5893286321638778.32535852705719.071042776
1637605.35842465705117.1085400881636153.76884665  704738.7321098
#Sta/Elev= 30
       0   11.13  175.12   15.32  376.1615.32291   441.3      16  515.568.754869
  560.38    6.34  707.48    5.29  728.49    3.35  729.12    2.67     798   -3.43
     849   -2.43     883   -3.73     900   -3.33  951.51    2.61 1035.762.026162
 1337.04     .91 1478.67    1.95 1604.56       0 1683.24     1.9 2369.18    1.22
 2398.12       0 2658.54    1.73 2875.56     .94 2911.73    1.76 2976.83    7.91
  3078.1    6.08 3186.61    8.28 3237.25    14.2 3389.16   14.44 3565.45   21.26
#Mann= 6 ,-1 , 0
       0     .06       0  376.16     .06       0  515.56      .1       0
  728.49    .035       0  951.51     .06       0 1035.76     .06       0
#XS Ineff= 1 ,-1
 2222.67 3565.45  6.4152
Permanent Ineff=
       F
Bank Sta=729.12,951.51
XS Rating Curve= 0 ,0
Exp/Cntr=0.3,0.1

Type RM Length L Ch R = 1 ,1274.915,970.2,965.13,955.33
BEGIN DESCRIPTION:
underwater portion from hec2 section 201
END DESCRIPTION:
XS GIS Cut Line= 4
1639569.47607636705708.7516856041639083.58220801705003.932511747
1638758.93201643704994.3839767131636146.88927519704714.653609693
#Sta/Elev= 30
       0   10.86  255.07   15.05  807.71   11.96  863.08    8.84  923.0211.72591
  954.12   11.57  996.13    4.74 1031.15    2.27    1033    -.23    1050   -3.53
    1086   -4.33 1209.03    1.27 1300.55     1.6 1610.31    2.19 1659.59    1.54
    1697   -2.53    1717     .77 1870.79    2.37    2918     .97    2922   -2.83
    2935   -4.23    2948   -2.33    2951     .97  3243.6    1.47 3264.72    2.33
 3292.88    9.23 3342.16    7.31 3539.28   10.88 3581.52   14.06 3807.85   21.64
#Mann= 4 ,-1 , 0
       0     .06       0  923.02      .1       0 1031.15    .035       0
 1300.55     .06       0
#XS Ineff= 1 ,-1
    2600 3811.46   5.802
Permanent Ineff=
       F
Bank Sta=1031.15,1300.55
XS Rating Curve= 0 ,0
Exp/Cntr=0.3,0.1

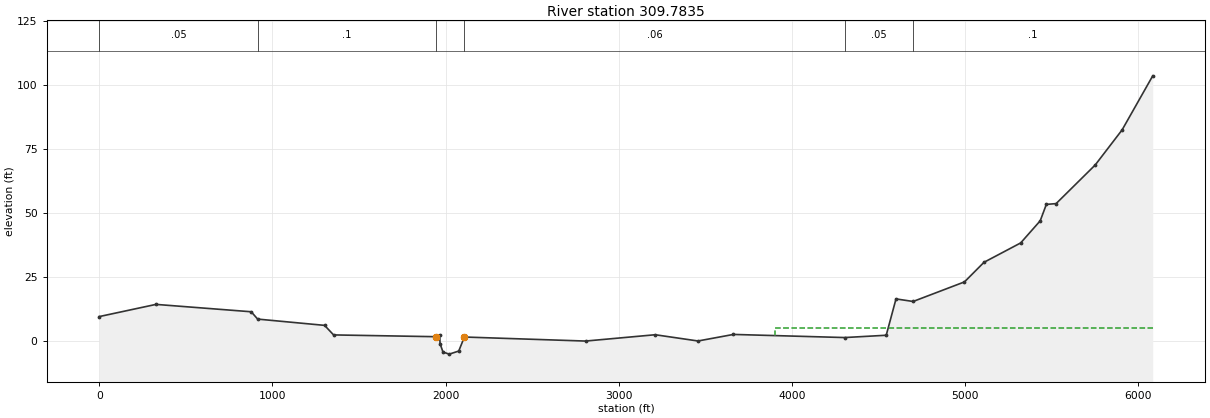
Type RM Length L Ch R = 1 ,309.7835,387.27,309.78,243.58
BEGIN DESCRIPTION:
No channel invert information available.  Copied underwater portion of channel from xsec 1274 w/ -0.772 ft adjustment for 0.0008 percent slope at downstream end.
END DESCRIPTION:
XS GIS Cut Line= 4
1639773.94805296705739.1837111261639165.20711069704037.476077035
1638404.28093284704051.3110984561634917.85553613704507.866805166
#Sta/Elev= 30
       0    9.57  327.11   14.32  877.26   11.44  914.43    8.58 1301.02    6.13
 1353.06     2.4 1947.34     1.7 1966.15  2.2514    1968  -1.002    1985  -4.302
    2021  -5.102    2076  -3.902 2108.36    1.58  2808.4       0 3210.81    2.47
 3457.91     .03 3662.64    2.59 4305.08    1.37  4545.1    2.27 4601.58   16.46
 4700.41   15.46 4996.92    23.1 5109.87   30.76 5321.66   38.32 5434.61   46.97
 5469.91   53.37 5526.38   53.68 5752.29   68.77  5907.6   82.47 6084.52  103.58
#Mann= 6 ,-1 , 0
       0     .05       0  914.43      .1       0 1947.34     .04       0
 2108.36     .06       0 4305.08     .05       0 4700.41      .1       0
#XS Ineff= 2 , 0
       0                    3900       0     5.2
Permanent Ineff=
       F       F
Bank Sta=1947.34,2108.36
XS Rating Curve= 0 ,0
Exp/Cntr=0.3,0.1

Chan Stop Cuts=-1
Use User Specified Reach Order=0
User Specified Reach Order=LittleElkCreek  ,One

--- LittleElkCreek.g02 (geometry) ---

Geom Title=LOMR
Program Version=4.00