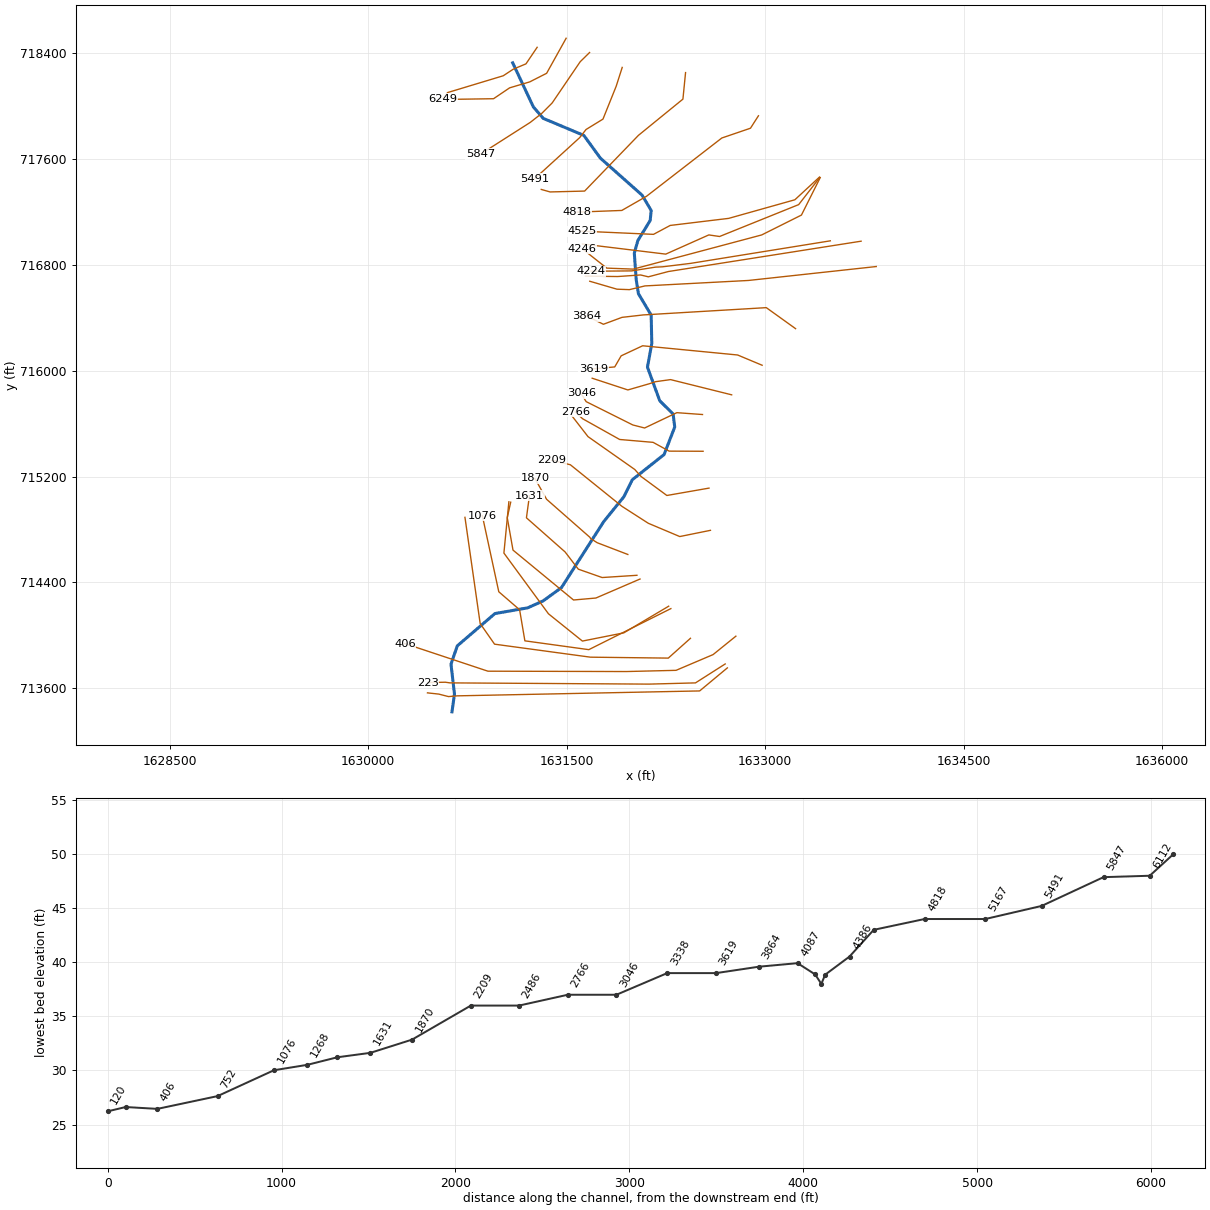
HEC-RAS study LittleElkCreek.prj: Little Elk Creek

--- LittleElkCreek.g02 (geometry) --- (continued)

River Reach=Little Elk Creek,Herron
Reach XY= 30
     1631092.629      718324.982     1631249.055      717991.319
     1631324.014      717905.116      1631630.41      717776.748
      1631755.03      717605.279     1632069.859      717326.056
     1632139.196      717209.869       1632131.7      717133.972
     1632038.938      716983.117     1632011.765      716887.544
      1632025.82      716688.902     1632042.686      716581.148
     1632139.196      716419.048     1632143.881      716204.478
     1632111.086      716026.449     1632203.848      715772.525
     1632305.043      715672.267     1632317.224      715573.883
     1632236.928      715365.889     1631996.773      715175.662
     1631933.058      715047.294     1631780.328      714858.959
      1631461.33      714361.025     1631322.836      714260.427
     1631206.391      714208.061     1630958.341      714164.653
     1630673.773      713920.737     1630626.231      713782.243
     1630652.482      713556.587     1630633.741       713422.64

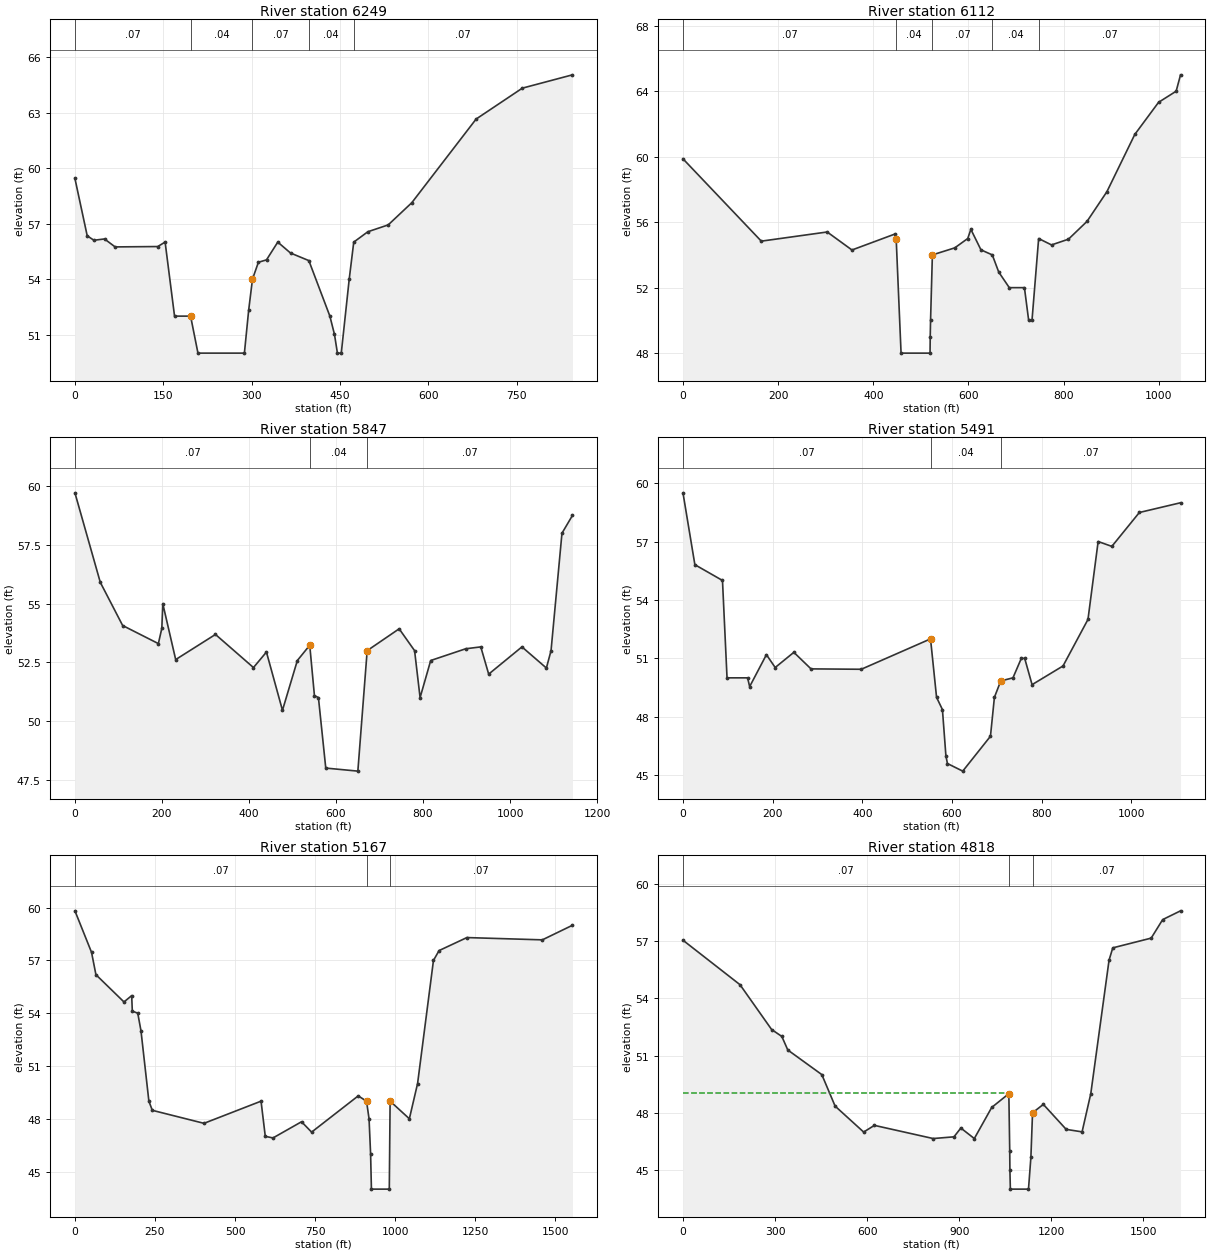
Type RM Length L Ch R = 1 ,6249    ,142.64,136.5,107.46
XS GIS Cut Line= 6
     1631277.439       718442.29     1631192.862      718317.182
     1631097.306      718277.201      1631020.97      718227.194
     1630600.115      718100.189     1630565.582      718053.013
#Sta/Elev= 30
       0   59.44   20.87   56.34   32.21    56.1   50.22   56.17   68.22   55.74
  140.49   55.76  153.06      56  169.06      52  196.28      52  208.79      50
  287.61      50  294.89   52.33  301.34      54  311.37   54.91  325.11   55.04
  344.25      56  365.86   55.41  396.98      55  432.65      52  440.48   51.01
  445.46      50     452      50  465.49      54  473.18      56  497.12   56.56
  531.67   56.93  571.72   58.13  680.83   62.65  759.26   64.32  844.37   65.04
#Mann= 5 ,-1 , 0
       0     .07       0  196.28     .04       0  301.34     .07       0
  396.98     .04       0  473.18     .07       0
#XS Ineff= 2 , 0
       0  153.06      56  344.25       0      56
Permanent Ineff=
       F       F
Bank Sta=196.28,301.34
XS Rating Curve= 0 ,0
Exp/Cntr=0.3,0.1

Type RM Length L Ch R = 1 ,6112    ,230.99,265.65,304.32
XS GIS Cut Line= 6
     1631496.499      718510.598     1631348.959      718245.834
     1631221.104       718180.96      1631069.34      718135.969
     1630947.832      718053.894     1630653.897      718049.445
#Sta/Elev= 30
       0   59.87   164.6   54.84   303.1    55.4  355.17    54.3     445   55.27
  448.06      55  458.35      48  519.26      48  519.63      49  520.34      50
  524.17      54  571.17   54.43  598.46      55  605.06   55.56  626.23   54.31
  650.06      54  663.65   52.95   685.8      52  717.62      52  726.53      50
  733.52      50  747.49      55  774.56   54.61  810.14   54.96  849.23   56.05
  890.93   57.86  949.58   61.36   999.5   63.32 1036.49      64 1045.69      65
#Mann= 5 ,-1 , 0
       0     .07       0  448.06     .04       0  524.17     .07       0
  650.06     .04       0  747.49     .07       0
#XS Ineff= 2 , 0
       0     445   55.27  605.06       0   55.56
Permanent Ineff=
       F       F
Bank Sta=448.06,524.17
XS Rating Curve= 0 ,0
Exp/Cntr=0.3,0.1

Type RM Length L Ch R = 1 ,5847    ,360.31,355.63,364.43
XS GIS Cut Line= 6
     1631673.788      718403.042     1631602.486      718333.004
     1631390.876      718021.815     1631312.682      717943.387
     1631225.113      717874.848     1630850.272      717635.845
#Sta/Elev= 30
       0   59.72   58.28   55.91   109.7   54.07  191.77    53.3  199.72   53.95
  201.92      55  231.57   52.62  322.98   53.69   410.3   52.28  440.13   52.94
  476.96   50.46  511.16   52.58  539.64   53.23  550.39   51.09  559.61      51
  576.46      48  650.21   47.87  671.62      53  745.12   53.93  780.57      53
  793.22      51  817.63   52.58  898.03   53.08   932.7   53.16  950.87      52
 1027.28   53.16 1083.48   52.26 1094.16      53 1119.28      58 1143.45   58.76
#Mann= 3 , 0 , 0
       0     .07       0  539.64     .04       0  671.62     .07       0
#XS Ineff= 2 , 0
       0  539.64   53.23  745.12       0   53.93
Permanent Ineff=
       F       F
Bank Sta=539.64,671.62
XS Rating Curve= 0 ,0
Exp/Cntr=0.3,0.1

Type RM Length L Ch R = 1 ,5491    ,308.37,324.23,328.87
XS GIS Cut Line= 6
     1631920.323      718290.397     1631874.879      718148.434
        1631775.         717900.     1631646.921      717821.345
     1631599.483      717760.527     1631257.091      717448.408
#Sta/Elev= 30
       0    59.5   26.56   55.81   88.15      55    98.3      50  144.16      50
  148.76   49.55  186.15   51.19  205.72   50.53  247.35   51.31  285.62   50.46
  397.69   50.44  552.26      52  565.69      49  578.81   48.37  586.54      46
  589.94    45.6  624.11   45.21  685.93      47  694.76      49  708.88   49.84
  736.14      50  754.79      51  762.32      51  778.78   49.65  847.83   50.61
  903.48      53  926.16      57  956.72   56.75 1018.07   58.49 1109.96   58.99
#Mann= 3 , 0 , 0
       0     .07       0  552.26     .04       0  708.88     .07       0
#XS Ineff= 2 , 0
       0  552.26      52  754.79       0      51
Permanent Ineff=
       F       F
Bank Sta=552.26,708.88
XS Rating Curve= 0 ,0
Exp/Cntr=0.3,0.1

Type RM Length L Ch R = 1 ,5167    ,366.9,349.12,320.86
XS GIS Cut Line= 6
     1632399.085      718251.231     1632379.167      718050.807
     1632043.069      717777.235     1631636.205      717356.219
     1631375.377      717349.628     1631308.499      717368.565
#Sta/Elev= 30
       0   59.82   51.91   57.46   65.58   56.19  153.17   54.64  177.22      55
   179.2   54.12  196.21      54  206.27      53  230.92      49  241.65   48.48
  402.96   47.74  581.13      49  594.37      47  618.51   46.91  707.54   47.83
  739.02   47.24  884.51    49.3  910.48      49  918.36      48   923.2      46
  925.76      44  981.58      44  984.13      49 1044.22      48 1069.86      50
 1119.47      57 1136.94   57.56 1223.83    58.3 1459.42   58.17 1553.55      59
#Mann= 3 , 0 , 0
       0     .07       0  910.48     .04       0  984.13     .07       0
#XS Ineff= 2 , 0
       0  884.51    49.3  984.13       0      49
Permanent Ineff=
       F       F
Bank Sta=910.48,984.13
XS Rating Curve= 0 ,0
Exp/Cntr=0.3,0.1

Type RM Length L Ch R = 1 ,4818    ,339.81,292.46,218.74
XS GIS Cut Line= 6
        1632950.         717925.     1632889.757      717831.076
      1632673.09      717757.118     1632103.695      717316.699
     1631917.265      717209.898     1631579.429      717197.193
#Sta/Elev= 30
       0   57.04  185.78   54.71  288.86   52.36  322.03      52  341.44   51.29
   452.3      50  495.58   48.35  588.59   46.99   623.6   47.34  815.08   46.65
  882.82   46.74  905.21    47.2  949.09   46.65 1005.76   48.28 1061.57      49
 1064.43      46    1065      45 1066.49      44 1125.55      44 1133.37   45.66
 1138.75      48 1173.92   48.44 1248.42   47.13 1300.14      47 1328.48      49
 1388.06      56 1400.13   56.64 1525.22   57.15 1562.66   58.12 1620.86   58.58
#Mann= 3 , 0 , 0
       0     .07       0 1061.57     .04       0 1138.75     .07       0
#XS Ineff= 2 , 0
       0 1059.42   49.01 1173.92       0   48.44
Permanent Ineff=
       F       F
Bank Sta=1061.57,1138.75
XS Rating Curve= 0 ,0
Exp/Cntr=0.3,0.1

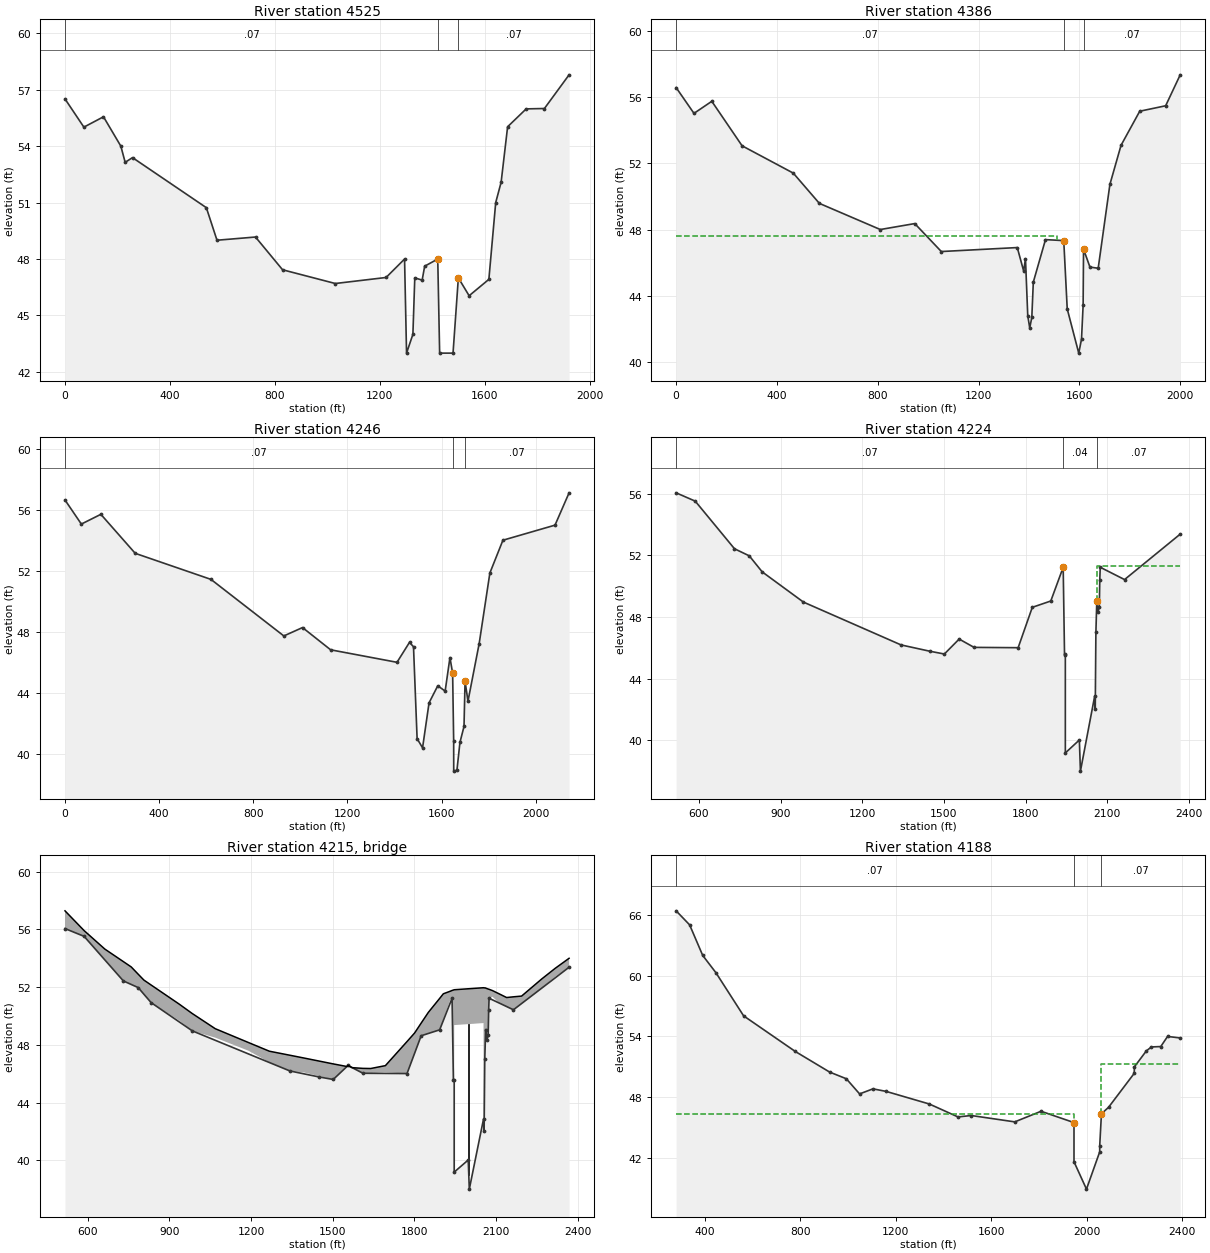
Type RM Length L Ch R = 1 ,4525    ,171.56,139.13,144.41
XS GIS Cut Line= 6
     1633410.681      717461.467      1633225.24      717290.515
        1632725.         717150.      1632282.93      717096.594
     1632156.736      717029.226     1631616.338      717053.326
#Sta/Elev= 30
       0   56.51   71.95   55.01  146.65   55.56  212.78      54  229.25   53.14
  257.26   53.39  538.52   50.73  579.12      49  725.84   49.17  828.96   47.43
 1029.86    46.7 1223.31   47.02 1293.78      48 1301.36      43 1325.56      44
 1332.74      47 1360.82   46.88 1370.39   47.62 1420.22      48 1427.46      43
 1478.47      43 1498.73      47 1539.76   46.05    1615   46.92 1641.05      51
 1661.69   52.08 1686.42   55.03 1757.14   55.98 1826.64      56 1920.62   57.79
#Mann= 3 , 0 , 0
       0     .07       0 1420.22     .04       0 1498.73     .07       0
#XS Ineff= 2 , 0
       0 1420.22      48 1498.73       0      47
Permanent Ineff=
       F       F
Bank Sta=1420.22,1498.73
XS Rating Curve= 0 ,0
Exp/Cntr=0.3,0.1

Type RM Length L Ch R = 1 ,4386    ,100.01,140.35,150.43
XS GIS Cut Line= 6
     1633413.864      717459.223     1633253.892      717253.894
     1632656.163      717013.108        1632575.         717025.
     1632249.376      716879.954     1631619.767      716956.463
#Sta/Elev= 30
       0   56.58   70.84   55.02  141.55   55.75  261.78   53.06  464.85   51.41
   568.4   49.58  810.12      48   946.8   48.36 1052.18   46.67  1353.6   46.91
 1378.97   45.49 1386.12   46.24 1395.16   42.79 1403.04   42.05 1411.27   42.69
 1417.22   44.82 1465.49   47.39 1537.97   47.33 1551.79    43.2 1597.47   40.53
 1608.43   41.37 1614.86   43.42 1616.52   46.81 1641.94   45.73 1674.65   45.66
 1721.13   50.73 1765.28   53.09 1839.47   55.15  1942.3   55.48 2000.07   57.35
#Mann= 3 , 0 , 0
       0     .07       0 1537.97     .04       0 1616.52     .07       0
#XS Ineff= 2 , 0
       0 1510.41    47.6 1616.52       0   46.81
Permanent Ineff=
       F       F
Bank Sta=1537.97,1616.52
XS Rating Curve= 0 ,0
Exp/Cntr=0.3,0.1

Type RM Length L Ch R = 1 ,4246    ,35.53,21.57,30.29
XS GIS Cut Line= 6
     1633417.014      717458.074        1633275.         717175.
     1632974.624      717024.875     1632004.153      716766.631
     1631803.474       716774.23     1631618.769       716919.82
#Sta/Elev= 30
       0   56.64   69.48   55.06  152.31    55.7  298.34   53.14  620.09   51.43
  929.61   47.72 1009.01   48.27 1128.41   46.81 1410.33   45.99 1463.43    47.3
 1480.44   47.01 1495.75   40.98 1518.92   40.38 1546.47   43.33 1583.52   44.45
 1614.85    44.1 1635.23    46.3 1646.64   45.28 1651.06   40.81 1651.26   38.85
 1664.95   38.91 1677.66   40.73 1694.97   41.78  1699.4   44.74 1711.86   43.44
 1759.41   47.22 1804.85   51.85 1860.26      54 2081.56   54.99 2141.31   57.11
#Mann= 3 , 0 , 0
       0     .07       0 1646.64     .04       0  1699.4     .07       0
#XS Ineff= 2 , 0
       0 1635.23    46.3  1699.4       0   44.74
Permanent Ineff=
       F       F
Bank Sta=1646.64,1699.4
XS Rating Curve= 0 ,0
Exp/Cntr=0.5,0.3

Type RM Length L Ch R = 1 ,4224    ,61.71,35.77,32.77
BEGIN DESCRIPTION:
Zeitler Road --- Upstream face
END DESCRIPTION:
XS GIS Cut Line= 6
     1633493.228      716980.371     1632436.981      716810.041
     1632224.666      716784.026     1632171.837      716781.739
     1631992.454      716753.241     1631684.078      716750.724
#Sta/Elev= 30
  516.37   56.06  586.59   55.52  730.79   52.43  785.13   51.97  832.59   50.93
  983.98   48.97 1342.66   46.19 1448.51   45.78 1501.75    45.6 1556.14   46.57
 1610.88   46.03 1772.81   46.01 1824.79   48.63  1892.7   49.04 1938.26   51.23
 1943.15   45.58 1946.13   45.56 1946.14   39.18 1997.62   40.02 2001.62      38
 2053.86   42.86 2056.02   42.01 2058.39      47 2061.75   49.06 2066.54   48.34
 2070.93   48.66 2072.73   50.42 2074.35   51.23  2163.7   50.43 2368.13   53.38
#Mann= 3 , 0 , 0
  516.37     .07       0 1938.26     .04       0 2061.75     .07       0
#XS Ineff= 2 , 0
       0 1938.26   46.36 2061.75       0   51.28
Permanent Ineff=
       F       F
Bank Sta=1938.26,2061.75
XS Rating Curve= 0 ,0
Exp/Cntr=0.5,0.3

Type RM Length L Ch R = 3 ,4215    ,,,
BEGIN DESCRIPTION:
Zeitler Road
END DESCRIPTION:
Bridge Culvert--1,0,-1,-1, 0
Deck Dist Width WeirC Skew NumUp NumDn MinLoCord MaxHiCord MaxSubmerge Is_Ogee
7.88,15.67,2.6,0, 60, 57, 46.36, , 0.95, 0, 0,0,,
  516.37  586.59  662.64  730.79  759.71  785.13  806.22  832.59  935.44  983.98
 1068.37 1190.51 1267.05 1342.66 1393.66 1501.75 1551.93 1556.14 1570.93 1610.88
  1639.3 1693.34 1772.81 1800.58 1824.79 1851.05 1877.67  1892.7 1906.21  1931.9
 1938.26 1943.15 1946.13 1946.14 2053.86 2053.87  2055.6 2056.02 2056.08 2056.17
 2056.49 2056.81 2057.93 2058.39 2061.75 2062.71 2063.39 2066.54 2070.93 2072.73
 2073.71 2074.35  2086.8 2111.92 2138.66  2163.7 2193.63 2267.83 2317.49 2368.13
   57.29   55.92   54.64   53.77    53.4    52.9   52.49   52.15   50.83   50.17
   49.12   48.16   47.56   47.28   47.09   46.68    46.5   46.57   46.42   46.37
   46.36   46.56   48.23   48.82   49.51   50.25   50.87   51.22   51.54   51.72
   51.77    51.8   51.82   51.82   51.96   51.96   51.95   51.95   51.95   51.95
   51.95   51.95   51.95   51.95   51.94   51.93   51.92    51.9   51.87   51.86
   51.85   51.85   51.76   51.53   51.28   51.33   51.38   52.57   53.31      54
   56.06   55.52   53.94   52.43   52.19   51.97   51.51   50.93   49.69   48.97
    48.5   47.59   46.79   46.19   46.09    45.6    46.5   46.57   46.42   46.03
   46.05    46.1   46.01   47.41   48.63    48.7   48.77   49.04   49.76   51.13
   51.23   45.58   45.56   49.37   49.51   42.76   42.01   42.01   42.03   42.23
      43    43.9      46      47   49.06   48.94   48.73   48.34   48.66   50.42
   50.64   51.23   51.33   50.64   50.65   50.43    50.8    51.7   52.73   53.38
  279.35   335.9  390.78  445.84  501.81  515.92  534.53  562.09  608.21  662.64
  759.71  806.22  922.57  992.39 1047.93 1103.93 1158.84 1217.95 1272.55 1340.09
 1401.63 1460.15 1515.83 1571.26  1639.3 1693.34 1697.99 1754.55 1808.16 1851.05
 1906.21 1946.14 1946.15 1955.54 2012.22 2035.22 2053.85 2053.86 2061.09 2090.78
 2138.66 2193.63 2198.25 2199.49 2230.05 2236.33 2241.84  2249.7 2264.23 2270.46
 2277.69  2287.7 2309.66 2322.61 2338.15 2367.88 2391.09
   69.83   68.72   67.65   66.58   65.49   57.54   56.94    56.4    55.5   54.64
    53.4   52.49   50.99   50.05   49.35   48.84   48.56   48.18   47.57   47.31
   47.06   46.84   46.63   46.42   46.36   46.56   46.66   47.85   49.03   50.25
   51.54   51.82   51.82   51.89   51.87      52   51.93   51.93   51.94   51.73
   51.28   51.38   51.45   51.47      52   52.06   52.38   52.58   52.78   52.96
   52.87   52.89    53.2   53.38      54      54   54.32
   66.44   65.05   62.02   60.32      58   57.54   56.94   56.04   55.18   54.35
   52.84   52.12   50.47   49.81   48.31   48.81   48.56   48.18   47.57   47.31
   46.45   46.03   46.17   45.92   45.87   45.57   45.54   46.24   46.59   46.16
   45.75   45.47   49.37   49.44   49.42   49.55   49.48   43.16   46.34   46.98
   48.48    50.2   50.34      51      52   52.06   52.38   52.58   52.78   52.96
   52.87   52.89      53   53.38      54      54   53.85
Pier Skew, UpSta & Num, DnSta & Num=  ,1999.62, 3 ,2000.38, 3 , 0 , 0 , 0 ,,
       4       4     2.5
   37.99   42.97   49.44
    3.98    3.98     2.5
   38.89   42.96   49.43
BR Coef=-1 , 1 , 1 ,1.25, 0 ,,,0.8,-1,2,0,
WSPro=,,,, 1 ,,,, 0 ,,,, 0 ,,,,-1 ,-1 ,-1 , 0 , 0 , 0 , 0 , 0
BC Design=,, 0 ,, 0 ,,,,,,
BC Use User HTab Curves=0
BC User HTab FreeFlow(D)= 0

Type RM Length L Ch R = 1 ,4188    ,72.6,101.17,106.85
BEGIN DESCRIPTION:
Zeitler Road --- Downstream face
END DESCRIPTION:
XS GIS Cut Line= 6
     1633726.161      716977.704     1632269.837      716748.564
      1632117.64      716708.447     1632059.184      716722.589
      1631886.69      716710.591     1631642.402      716713.749
#Sta/Elev= 30
  279.35   66.44   335.9   65.05  390.78   62.02  445.84   60.32  562.09   56.04
  778.74   52.51  922.57   50.47  992.39   49.81 1047.93   48.31 1103.93   48.81
 1158.84   48.56 1340.09   47.31 1460.15   46.03 1515.83   46.17 1697.99   45.54
 1808.16   46.59 1946.14   45.47 1946.15   41.59 1998.39   38.88 2053.85   42.57
 2053.86   43.16 2061.09   46.34 2090.78   46.98 2198.25   50.34 2199.49      51
 2249.23   52.57 2270.46   52.96 2309.66      53 2338.15      54 2391.09   53.85
#Mann= 3 , 0 , 0
  279.35     .07       0 1946.14     .04       0 2061.09     .07       0
#XS Ineff= 2 , 0
       0 1946.14   46.36 2061.09       0   51.28
Permanent Ineff=
       F       F
Bank Sta=1946.14,2061.09
XS Rating Curve= 0 ,0
Exp/Cntr=0.5,0.3

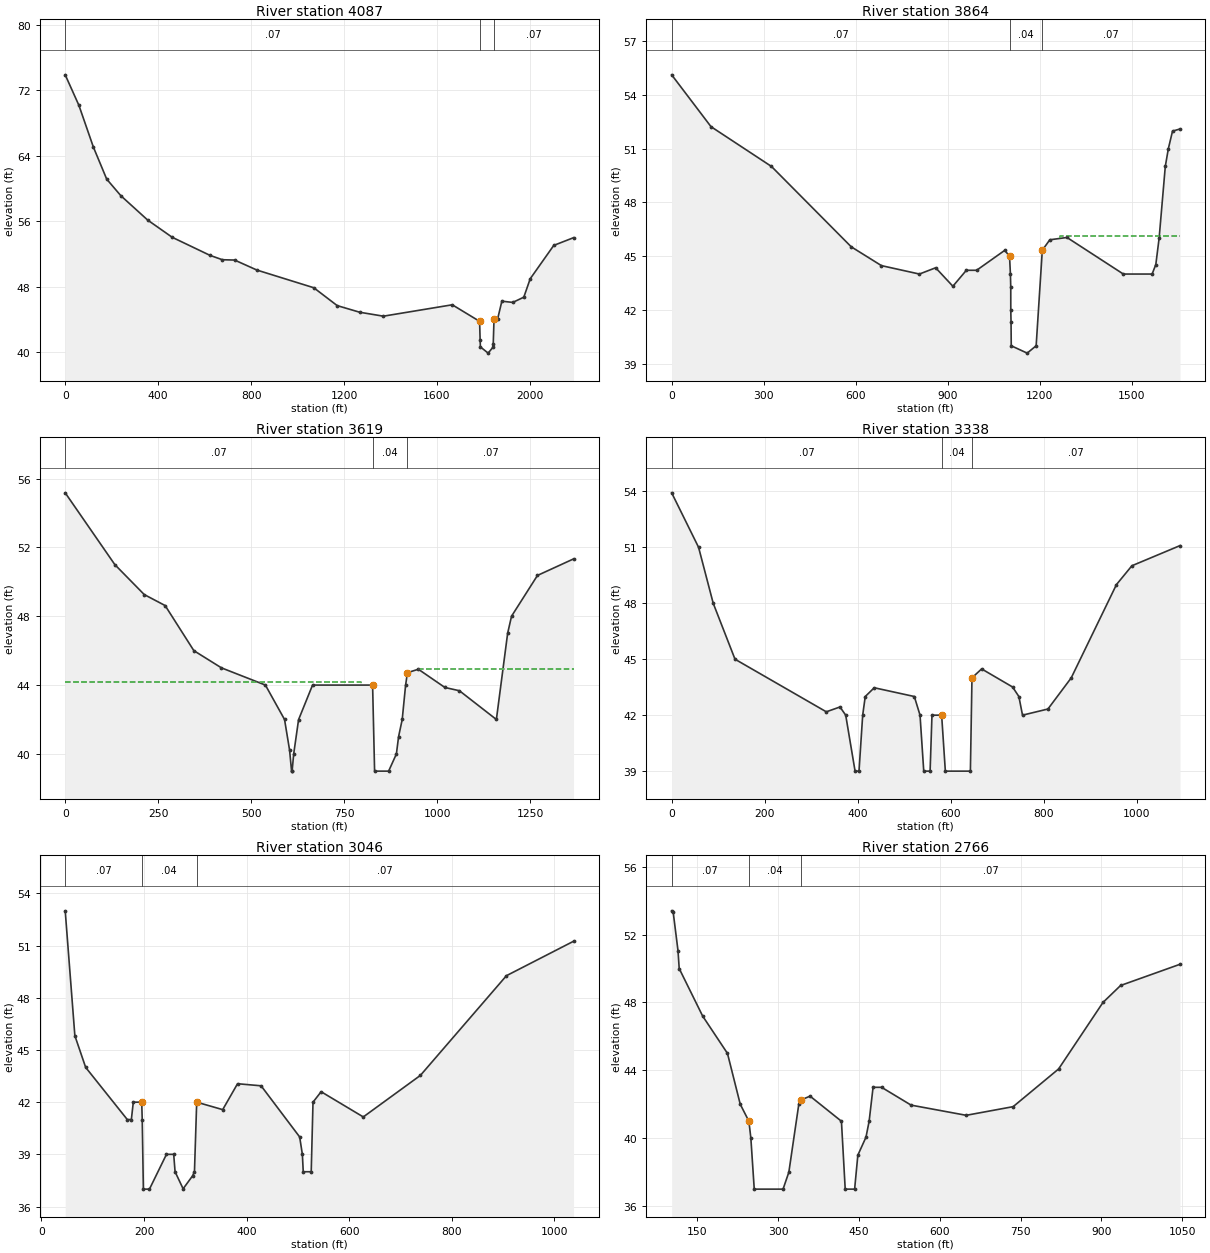
Type RM Length L Ch R = 1 ,4087    ,233.79,223.17,221.04
XS GIS Cut Line= 6
     1633840.408      716786.129      1632874.38      716680.962
     1632092.091      716639.781     1631974.834      716611.617
     1631880.411        716615.1        1631675.      716675.022
#Sta/Elev= 30
       0   73.89   58.89   70.17  121.25   65.07  178.57   61.16  239.61   59.13
     355   56.16  460.48   54.06  623.47   51.85  676.38   51.32  729.14   51.28
  825.01   50.06 1069.88    47.9 1170.59   45.72 1267.59   44.91 1369.42   44.43
  1665.9   45.82 1783.47    43.8 1785.77   41.47 1786.89   40.68 1820.23   39.92
 1841.03   40.64 1842.16      41 1845.49   44.03 1861.16    44.1 1879.29   46.26
 1926.27   46.11 1973.78   46.75 2001.35      49  2102.7   53.07 2187.76   54.01
#Mann= 3 , 0 , 0
       0     .07       0 1783.47     .04       0 1845.49     .07       0
#XS Ineff= 2 , 0
       0  1665.9   45.82               0
Permanent Ineff=
       F       F
Bank Sta=1783.47,1845.49
XS Rating Curve= 0 ,0
Exp/Cntr=0.3,0.1

Type RM Length L Ch R = 1 ,3864    ,260.91,245.32,249.76
XS GIS Cut Line= 6
     1633230.609      716316.878     1633009.318      716475.635
     1632079.577      716420.626     1631918.692      716402.236
     1631778.114      716350.086     1631653.408      716411.305
#Sta/Elev= 30
       0   55.11  128.22   52.22  325.57      50  585.65   45.52  684.18   44.47
  808.09      44  861.07   44.35  917.26   43.32  961.19   44.21  994.74   44.21
 1086.33   45.32 1102.04      45 1104.95      44 1106.04   43.25 1106.13      42
 1106.98   41.34 1107.65      40 1159.62   39.59  1188.9      40 1208.96   45.33
 1233.45   45.91 1289.41   46.04 1473.32      44 1567.14      44 1579.23   44.53
 1590.02      46 1610.13      50  1620.2      51 1633.73   51.97 1658.11   52.09
#Mann= 3 , 0 , 0
       0     .07       0 1102.04     .04       0 1208.96     .07       0
#XS Ineff= 2 , 0
       0 1086.33   45.32 1265.85       0    46.1
Permanent Ineff=
       F       F
Bank Sta=1102.04,1208.96
XS Rating Curve= 0 ,0
Exp/Cntr=0.3,0.1

Type RM Length L Ch R = 1 ,3619    ,252.28,280.91,297.94
XS GIS Cut Line= 6
     1632977.785      716040.524     1632792.659      716117.916
     1632074.854      716187.606     1631912.483      716111.673
       1631863.7      716027.827     1631702.523      716013.852
#Sta/Elev= 30
       0   55.17  133.36      51  212.39   49.26  268.62   48.62  345.79      46
     420      45  538.12      44  589.57      42  603.11   40.22  608.45      39
   609.9      39  614.17      40  627.26   41.99  664.86      44  826.26      44
  831.62      39  869.36      39  890.25      40  896.06      41  905.86      42
  914.98      44   919.9   44.72  949.27   44.92 1020.63   43.86 1059.68   43.67
 1158.97      42 1189.25   47.01  1199.7      48 1269.39   50.37 1366.35   51.33
#Mann= 3 , 0 , 0
       0     .07       0  826.26     .04       0   919.9     .07       0
#XS Ineff= 2 , 0
       0  795.99   44.16   949.2       0   44.92
Permanent Ineff=
       F       F
Bank Sta=826.26,919.9
XS Rating Curve= 0 ,0
Exp/Cntr=0.3,0.1

Type RM Length L Ch R = 1 ,3338    ,300.08,291.98,303.84
XS GIS Cut Line= 6
     1632747.523      715817.072     1632285.572      715932.002
     1632172.874       715916.38     1632123.866      715900.379
       1631963.1      715853.894     1631693.428      715942.461
#Sta/Elev= 30
       0   53.92   57.81      51   89.27      48  136.13      45  332.35   42.18
  361.74   42.44  374.06      42  394.19      39  402.66      39  410.55      42
  416.05      43   435.4   43.47  521.54      43   533.8      42  541.78      39
  555.46      39  559.47      42  580.26      42   588.2      39  642.04      39
  645.45      44  666.21   44.48  732.73   43.51  746.24      43  754.07      42
  808.71   42.33  858.78      44  955.96      49  989.17   50.01 1092.56   51.09
#Mann= 3 , 0 , 0
       0     .07       0  580.26     .04       0  645.45     .07       0
#XS Ineff= 2 , 0
       0   435.4   43.47  666.21       0   44.48
Permanent Ineff=
       F       F
Bank Sta=580.26,645.45
XS Rating Curve= 0 ,0
Exp/Cntr=0.3,0.1

Type RM Length L Ch R = 1 ,3046    ,291.13,279.68,184.55
XS GIS Cut Line= 6
      1632527.19      715668.237     1632333.056      715682.205
     1632089.714      715566.456     1632000.387      715589.426
     1631647.733      715765.612     1631609.831      715827.282
#Sta/Elev= 30
   46.39      53   65.22   45.82   86.25      44  167.42      41  175.34      41
  179.14      42  195.54      42  196.54      41  198.77      37  210.63      37
  243.79      39  257.88      39  260.55      38  276.26   37.02   294.6   37.76
  298.36      38  302.72      42   353.4   41.57  382.35   43.06  428.27   42.94
  503.44      40  508.72      39  510.42      38  525.97      38  529.45      42
  545.31    42.6  627.47   41.15  738.84   43.54  906.52   49.27 1037.33   51.25
#Mann= 3 , 0 , 0
   46.39     .07       0  195.54     .04       0  302.72     .07       0
#XS Ineff= 2 , 0
       0  195.54      42  382.35       0   43.06
Permanent Ineff=
       F       F
Bank Sta=195.54,302.72
XS Rating Curve= 0 ,0
Exp/Cntr=0.3,0.1

Type RM Length L Ch R = 1 ,2766    ,341.94,280.22,258.4
XS GIS Cut Line= 6
     1632531.798      715390.703     1632274.999      715391.679
     1632153.887      715457.997     1631901.034      715479.725
      1631620.53      715636.601     1631565.246      715687.954
#Sta/Elev= 30
  102.28    53.4  105.09   53.32     114   51.06  116.25      50  159.76    47.2
  205.83      45  229.59      42  245.63      41  249.28      40  255.56      37
  309.06      37   319.8      38  338.24      42  342.06   42.25  359.15   42.48
   417.4      41   424.4      37  441.89      37  447.85      39  462.96   40.06
  468.81      41  476.13      43  491.94      43  546.72   41.95  649.01   41.35
  736.13   41.86  820.48   44.08  902.86      48  935.59      49 1045.86   50.25
#Mann= 3 , 0 , 0
  102.28     .07       0  245.63     .04       0  342.06     .07       0
#XS Ineff= 2 , 0
       0                  359.15       0   42.48
Permanent Ineff=
       F       F
Bank Sta=245.63,342.06
XS Rating Curve= 0 ,0
Exp/Cntr=0.3,0.1

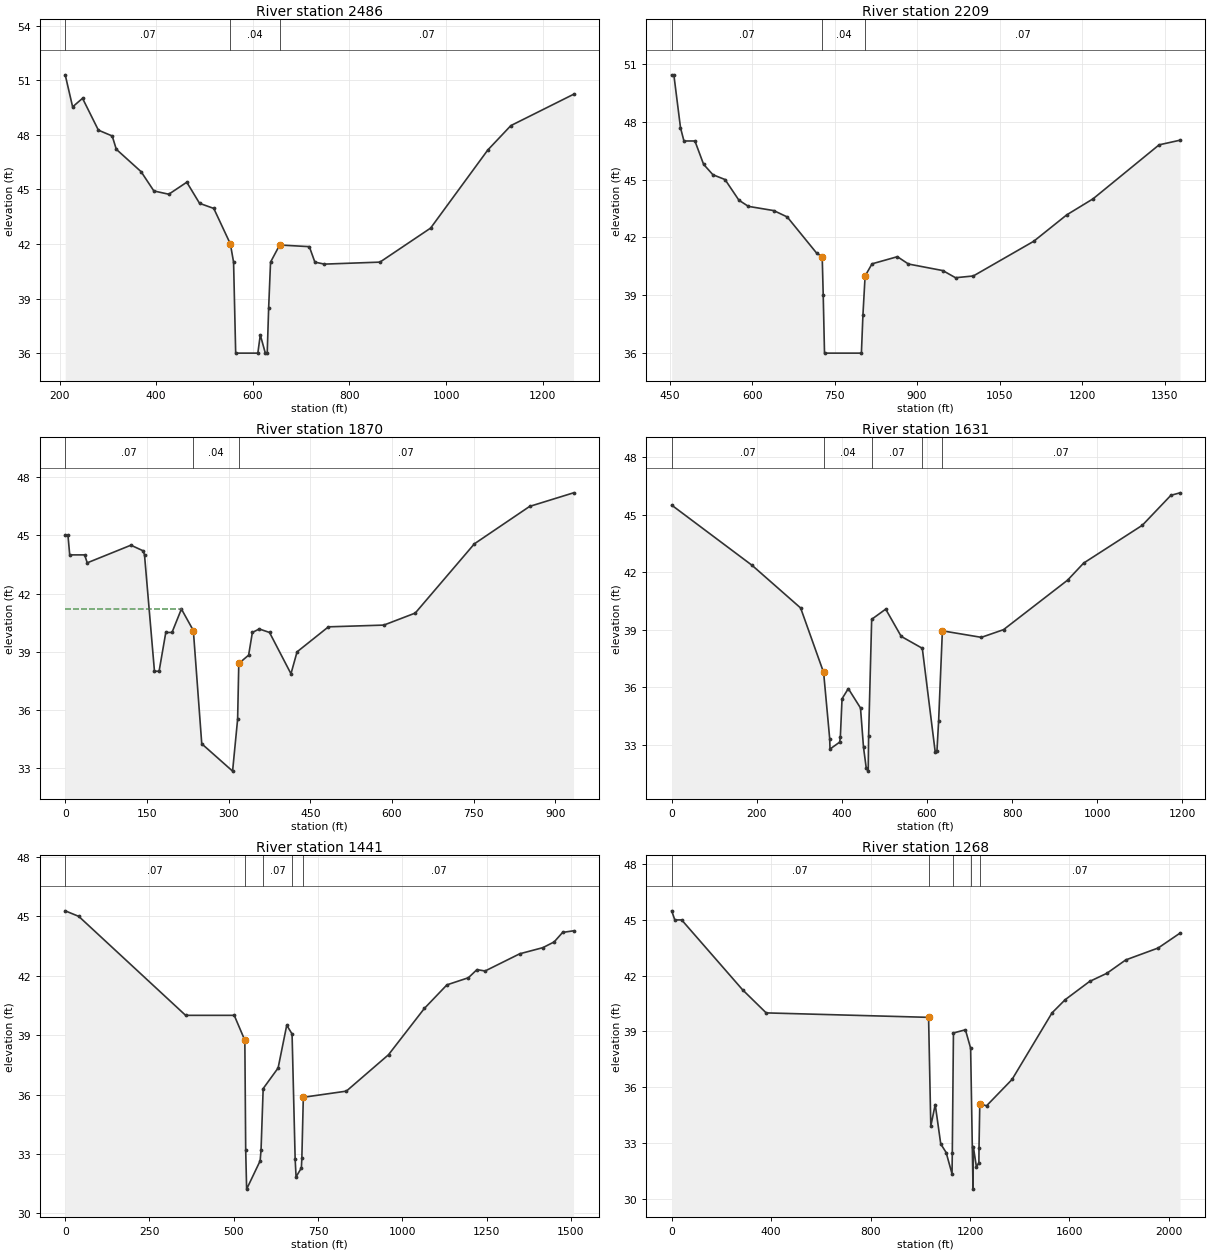
Type RM Length L Ch R = 1 ,2486    ,269.18,277.29,281.71
XS GIS Cut Line= 6
     1632576.308       715112.32     1632257.807      715056.665
     1632063.258      715199.778     1632014.796      715253.368
     1631661.912      715501.141     1631542.954      715654.515
#Sta/Elev= 30
  211.81   51.29  227.15   49.53  247.66      50  280.49   48.25  309.08   47.93
  317.54    47.2  368.83   45.97   395.3   44.91  426.13   44.73  463.41   45.39
  489.85   44.23  519.28   43.95  553.59      42  560.24      41  564.59      36
  610.46      36  615.54      37  625.96      36  629.86      36  632.84   38.49
  636.75      41  655.63   41.94  716.99   41.85   728.5      41  748.17   40.89
  863.15      41  968.01   42.87 1086.32   47.16 1134.05    48.5 1263.76   50.22
#Mann= 3 , 0 , 0
  211.81     .07       0  553.59     .04       0  655.63     .07       0
#XS Ineff= 2 , 0
       0  463.41   45.39  655.63       0   41.94
Permanent Ineff=
       F       F
Bank Sta=553.59,655.63
XS Rating Curve= 0 ,0
Exp/Cntr=0.3,0.1

Type RM Length L Ch R = 1 ,2209    ,319.91,338.34,332.61
XS GIS Cut Line= 6
     1632587.213      714793.368     1632355.306      714746.446
      1632117.68      714846.589     1631917.774      714975.048
     1631528.236      715288.824     1631387.191      715322.763
#Sta/Elev= 30
  453.83   50.43  457.84   50.42  469.87   47.69  476.13      47  496.08      47
  511.86   45.79  528.79   45.25  550.84      45  576.05   43.93  593.27   43.61
  639.52   43.39  663.94   43.06  717.83   41.17  727.49   41.01  729.34      39
  731.68      36  798.76      36  801.57      38   805.5      40  818.07   40.63
  864.17      41  884.29   40.62  946.81   40.28  969.84   39.91 1002.19      40
 1112.07    41.8  1172.1   43.17 1219.86      44 1339.97    46.8 1377.96   47.04
#Mann= 3 , 0 , 0
  453.83     .07       0  727.49     .04       0   805.5     .07       0
#XS Ineff= 2 , 0
       0                  864.17       0      41
Permanent Ineff=
       F       F
Bank Sta=727.49,805.5
XS Rating Curve= 0 ,0
Exp/Cntr=0.3,0.1

Type RM Length L Ch R = 1 ,1870    ,235.11,239.3,213.08
XS GIS Cut Line= 6
     1631962.692      714611.096     1631730.703      714700.027
     1631681.403      714731.917     1631675.154      714741.433
      1631348.51      715028.174     1631260.664      715185.234
#Sta/Elev= 30
       0      45    5.09      45    8.28      44   35.72      44   40.42   43.59
  120.66    44.5  143.07   44.21  145.59      44  163.88      38  172.38      38
  184.68      40  196.07      40  213.36   41.21  235.26    40.1  250.71   34.26
  307.31   32.85  316.57   35.53   318.7    38.4  336.76   38.83  343.64      40
  356.22   40.18  375.12      40   414.5   37.87  425.68      39  483.26   40.29
  585.03   40.38  642.68      41  751.21   44.57  852.72    46.5   933.3    47.2
#Mann= 3 , 0 , 0
       0     .07       0  235.26     .04       0   318.7     .07       0
#XS Ineff= 2 , 0
       0  213.52   41.21  356.22       0   40.18
Permanent Ineff=
       F       F
Bank Sta=235.26,318.7
XS Rating Curve= 0 ,0
Exp/Cntr=0.3,0.1

Type RM Length L Ch R = 1 ,1631    ,236.29,190.02,258.5
XS GIS Cut Line= 6
     1632031.712       714453.72     1631768.744      714436.791
     1631588.344      714500.038     1631488.434      714630.296
     1631196.426      714888.025     1631219.171      715055.428
#Sta/Elev= 30
       0   45.49   189.1   42.35  303.06   40.13  357.07   36.77  371.37   33.32
   372.1   32.78  394.76   33.14  396.36   33.39  400.38    35.4  415.08   35.93
  443.76   34.92  450.83   32.87  457.37   31.77  461.89   31.63  462.82   33.47
  470.02   39.54  502.99   40.07  539.42   38.65  588.99   38.03  619.33   32.63
  623.45   32.69  627.36   34.24  636.19   38.94  727.76    38.6  779.85      39
  930.42   41.58   968.2   42.47 1106.11   44.44 1173.17      46 1194.61   46.13
#Mann= 5 ,-1 , 0
       0     .07       0  357.07     .04       0  470.02     .07       0
  588.99     .04       0  636.19     .07       0
Bank Sta=357.07,636.19
XS Rating Curve= 0 ,0
Exp/Cntr=0.3,0.1

Type RM Length L Ch R = 1 ,1441    ,233.77,172.96,71.31
XS GIS Cut Line= 6
     1632055.022      714425.567     1631721.481      714282.018
     1631552.428      714267.099     1631094.921      714643.968
     1631051.398      714888.936     1631077.497      715006.022
#Sta/Elev= 30
       0   45.28   40.18      45  357.17      40  501.37      40  532.83   38.74
  535.37    33.2  538.15   31.22  578.25   32.65  580.92   33.21  587.21    36.3
  631.53   37.34  657.12    39.5  672.93   39.06  682.08   32.73  684.81   31.84
  700.56   32.29  701.95   32.79  706.29   35.86  833.88   36.17     959   38.01
  1065.4   40.35  1132.3   41.54 1195.96    41.9 1221.36   42.31 1245.41   42.24
 1348.31   43.11  1416.9   43.42 1450.42   43.71 1475.43   44.19 1507.82   44.27
#Mann= 5 ,-1 , 0
       0     .07       0  532.83     .04       0  587.21     .07       0
  672.93     .04       0  706.29     .07       0
Bank Sta=532.83,706.29
XS Rating Curve= 0 ,0
Exp/Cntr=0.3,0.1

Type RM Length L Ch R = 1 ,1268    ,263.08,191.9,312.68
XS GIS Cut Line= 6
     1632271.471      714220.218      1631932.26      714018.942
     1631619.401      713956.852     1631362.883      714162.892
       1631026.1      714621.656      1631063.72      715008.947
#Sta/Elev= 30
       0   45.49   12.66      45   40.28      45  285.44   41.24  380.23      40
 1033.55   39.76 1042.47   33.91 1060.26   35.07  1082.5   32.95 1104.17   32.49
  1127.9   31.34 1128.97   32.48 1133.57   38.92 1181.76   39.09 1202.69    38.1
 1212.37   30.52 1213.54   32.81 1226.01   31.71 1235.94   31.94 1236.42   32.74
 1239.61   35.12 1266.56      35 1369.37   36.42 1530.14      40 1583.07   40.71
 1681.11   41.69 1750.79   42.13 1826.86   42.85 1957.13   43.49 2045.01   44.29
#Mann= 5 ,-1 , 0
       0     .07       0 1033.55     .04       0 1133.57     .07       0
 1202.69     .04       0 1239.61     .07       0
Bank Sta=1033.55,1239.61
XS Rating Curve= 0 ,0
Exp/Cntr=0.3,0.1

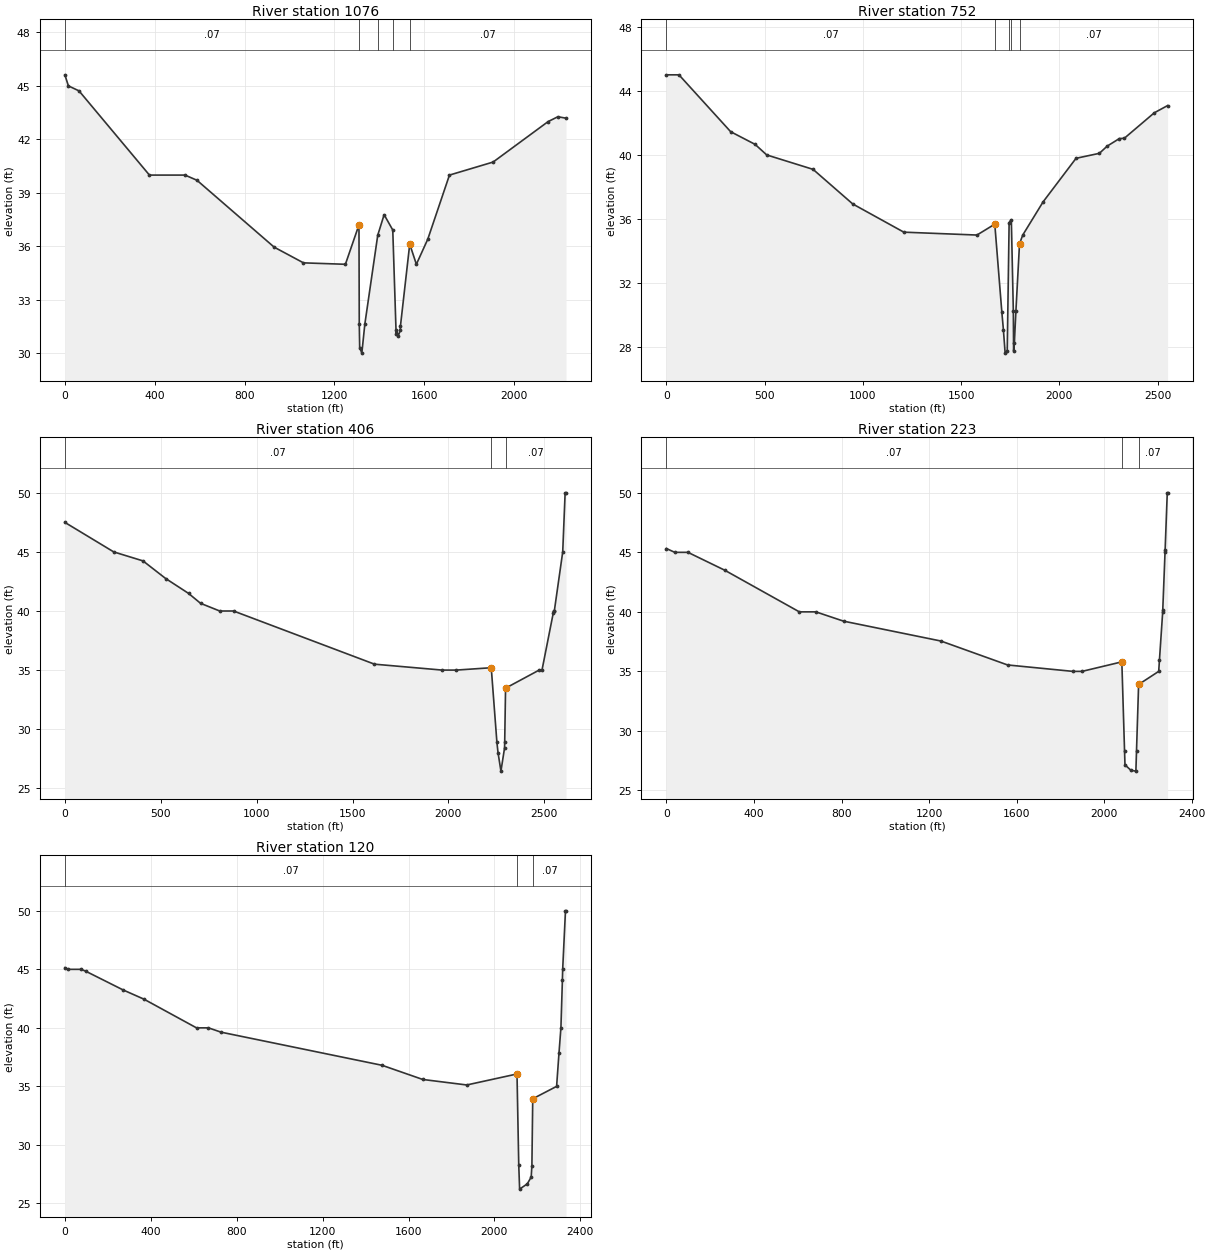
Type RM Length L Ch R = 1 ,1076    ,269.19,324.1,200.98
XS GIS Cut Line= 6
      1632288.08      714202.101     1631667.878      713892.001
     1631184.654      713958.587     1631144.865       714193.29
     1630987.459      714329.321     1630863.138      714904.109
#Sta/Elev= 30
       0   45.62   15.88      45   63.11   44.72   376.5      40  534.93      40
  588.05   39.71  931.78   35.96 1062.29   35.08 1248.87      35 1309.22   37.21
 1310.57   31.65 1312.43   30.33 1322.02   30.02 1335.28   31.64 1392.83   36.63
 1421.19   37.78 1459.69   36.92  1474.7   31.08 1475.16   31.31 1484.48      31
  1493.1    31.3 1493.88   31.54  1535.2   36.13 1564.75      35 1615.61   36.41
    1712      40 1906.26   40.73 2151.34      43 2194.58   43.27 2230.78   43.19
#Mann= 5 ,-1 , 0
       0     .07       0 1309.22     .04       0 1392.83     .07       0
 1459.69     .04       0  1535.2     .07       0
#XS Ineff= 2 , 0
       0 1309.22   37.21  1535.2       0   36.13
Permanent Ineff=
       F       F
Bank Sta=1309.22,1535.2
XS Rating Curve= 0 ,0
Exp/Cntr=0.3,0.1

Type RM Length L Ch R = 1 ,752     ,278.4,345.91,467.18
XS GIS Cut Line= 6
     1632436.119      713977.848     1632268.622      713828.177
      1631680.17       713835.19     1630955.462      713933.418
     1630846.785      714089.054     1630731.748      714891.515
#Sta/Elev= 30
       0      45   63.77      45  327.02   41.45  451.34   40.66  510.53      40
  746.41    39.1  948.38   36.94 1208.37   35.18 1580.67      35 1671.35   35.68
 1707.31   30.18 1715.18    29.1 1724.02   27.63 1734.75   27.79 1744.36   35.78
 1755.55   35.96 1765.74   30.27 1767.14   27.76 1770.92   28.24 1778.96   30.28
 1797.22   34.45 1813.65      35  1917.2   37.07 2084.93   39.79  2203.6    40.1
 2243.42   40.55 2305.24   41.02  2330.7   41.04 2483.21   42.63  2550.8   43.08
#Mann= 5 ,-1 , 0
       0     .07       0 1671.35     .04       0 1744.36     .07       0
 1755.55     .04       0 1797.22     .07       0
#XS Ineff= 2 , 0
       0 1671.35   35.68               0
Permanent Ineff=
       F       F
Bank Sta=1671.35,1797.22
XS Rating Curve= 0 ,0
Exp/Cntr=0.3,0.1

Type RM Length L Ch R = 1 ,406     ,159.29,182.92,217.98
XS GIS Cut Line= 6
     1632779.521      713993.894     1632607.205      713854.698
     1632327.259      713735.767     1631950.337      713726.618
     1630905.256      713729.345     1630277.294      713937.893
#Sta/Elev= 26
       0    47.5  254.93      45  407.47   44.24  525.68   42.75  645.07   41.49
   707.7   40.65  807.65      40  879.69      40  1614.7    35.5 1967.85      35
 2041.23      35 2223.56    35.2 2252.89   28.92 2258.82   28.02 2274.07   26.45
 2292.82    28.4 2293.67    28.9  2298.2   33.47 2473.31      35 2488.17      35
  2547.4   39.87  2549.1      40 2552.42      40 2596.23      45  2608.8      50
 2613.32      50
#Mann= 3 , 0 , 0
       0     .07       0 2223.56     .04       0  2298.2     .07       0
Bank Sta=2223.56,2298.2
XS Rating Curve= 0 ,0
Exp/Cntr=0.3,0.1

Type RM Length L Ch R = 1 ,223     ,99.49,103.21,97.82
XS GIS Cut Line= 6
     1632698.675      713783.957     1632474.074        713640.9
     1632123.054      713631.701     1630618.681      713640.971
     1630584.077      713645.995     1630451.812      713643.522
#Sta/Elev= 26
       0   45.32   38.22      45    98.4      45  266.29    43.5  607.26      40
  682.71      40  809.08   39.22 1254.07   37.55 1558.54   35.54 1857.21      35
 1898.78      35 2080.72    35.8 2093.07   28.32 2095.03   27.15 2122.05   26.69
 2144.88   26.62 2147.77   28.34 2157.34    33.9 2249.14      35 2252.53   35.95
 2267.38      40 2267.76   40.19 2278.02      45 2278.52   45.22 2288.25      50
 2289.63      50
#Mann= 3 , 0 , 0
       0     .07       0 2080.72     .04       0 2157.34     .07       0
Bank Sta=2080.72,2157.34
XS Rating Curve= 0 ,0
Exp/Cntr=0.3,0.1

Type RM Length L Ch R = 1 ,120     ,119.03,120.11,126.07
XS GIS Cut Line= 6
     1632715.089      713754.361     1632505.613       713580.18
     1630673.292      713543.088      1630607.48      713537.456
     1630533.845      713556.245     1630448.387      713565.604
#Sta/Elev= 26
       0   45.14   15.19      45   76.01      45   98.34   44.83  272.43   43.23
  368.55   42.45  612.98      40  668.61      40  727.67   39.63 1477.15    36.8
 1666.41   35.59  1871.3   35.12 2105.13   36.06 2113.22    28.3 2117.31   26.22
 2152.94   26.67 2171.19   27.25 2174.48   28.23 2178.38   33.94 2289.49      35
 2300.43   37.81 2309.57      40 2316.41   44.05 2317.77      45 2330.75      50
 2333.22      50
#Mann= 3 , 0 , 0
       0     .07       0 2105.13     .04       0 2178.38     .07       0
Bank Sta=2105.13,2178.38
XS Rating Curve= 0 ,0
Exp/Cntr=0.3,0.1

Chan Stop Cuts=-1
Use User Specified Reach Order=0