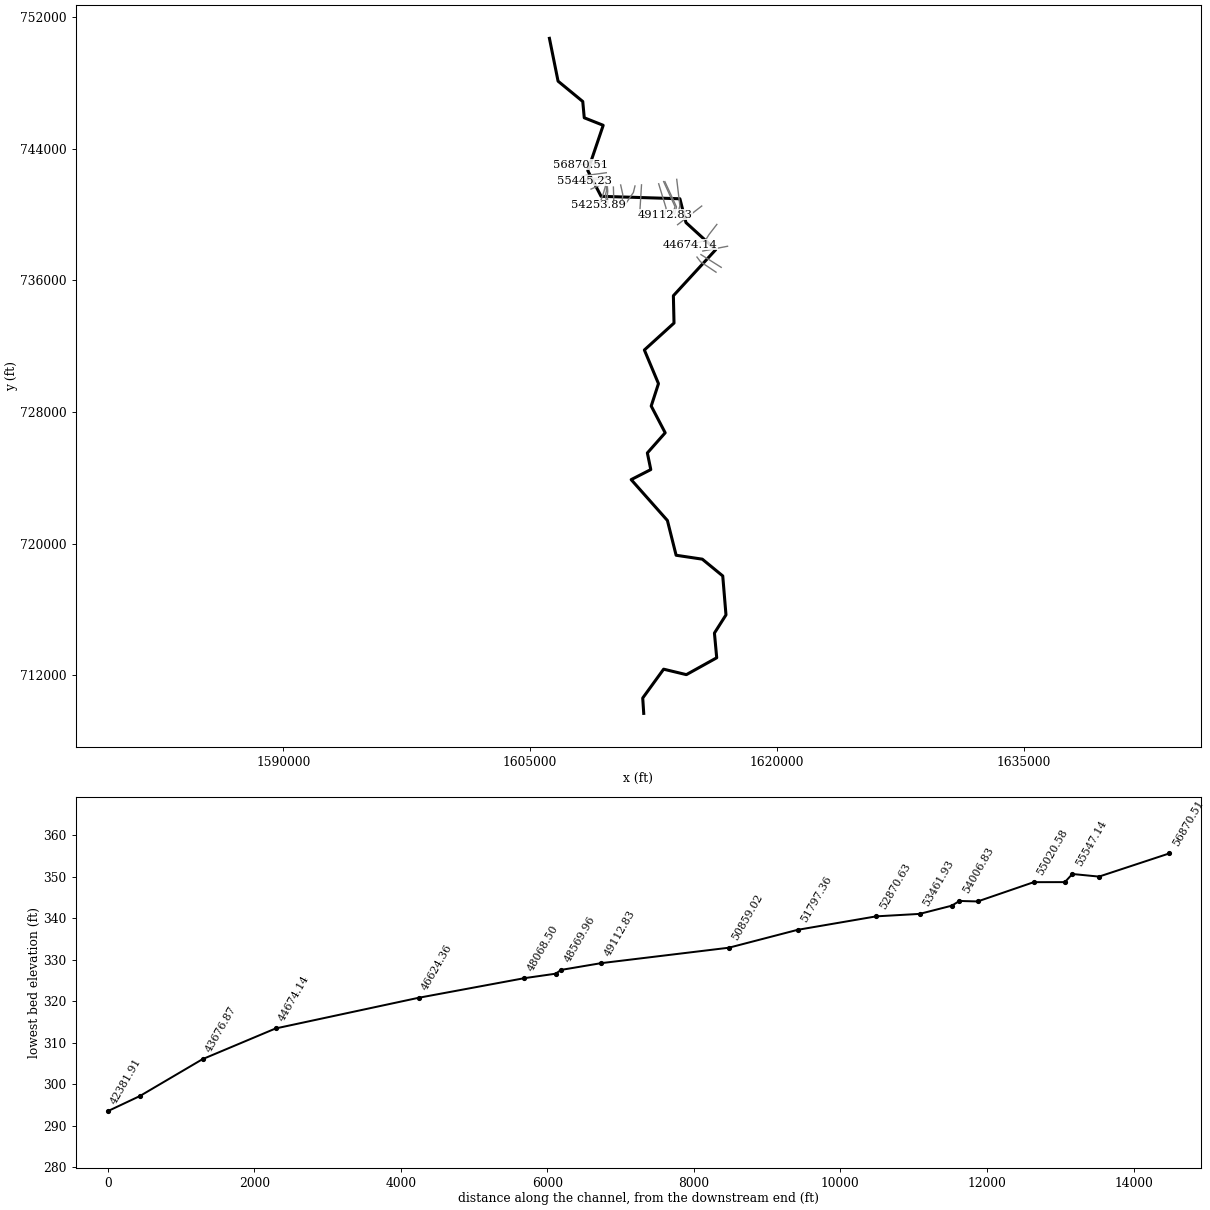
--- LittleNortheast.prj (project) ---

Proj Title=Little Northeast Creek
Current Plan=p01
Default Exp/Contr=0.3,0.1
English Units
Geom File=g03
Flow File=f01
Flow File=f02
Plan File=p01
Plan File=p02
Y Axis Title=Elevation
X Axis Title(PF)=Main Channel Distance
X Axis Title(XS)=Station
BEGIN DESCRIPTION:
Little NE Ck, Cecil Co., MD. Geo-referenced HEC-RAS model. Vertical datum NAVD88 Created by Pat Wheeler, Seattle District, For MDE Map Modernization
END DESCRIPTION:
DSS Export Rating Curves= 0
DSS Export Rating Curve Sorted= 0
DSS Export Volume Flow Curves= 0
DXF OffsetX= 0
DXF OffsetY= 0
DXF ScaleX= 1
DXF ScaleY= 10

--- LittleNortheast.p01 (plan) ---

Plan Title=Little Northeast Creek Frequency Profile
Program Version=4.00
Short Identifier=frequency
Geom File=g03
Flow File=f01
Subcritical Flow
K Sum by GR= 0
Std Step Tol= 0.01
Critical Tol= 0.01
Num of Std Step Trials= 20
Max Error Tol= 0.3
Flow Tol Ratio= 0.001
Split Flow NTrial= 30
Split Flow Tol= 0.02
Split Flow Ratio= 0.02
Log Output Level= 0
Friction Slope Method= 1
Unsteady Friction Slope Method= 2
Unsteady Bridges Friction Slope Method= 1
Parabolic Critical Depth
Global Vel Dist= 0 , 0 , 0
Global Log Level= 0
CheckData=True
Encroach Param=-1 ,0,0, 0
Computation Interval=1HOUR
Output Interval=1HOUR
Run HTab= 0
Run UNet= 0
Run PostProcess= 0
Run WQNet= 0
UNET Theta= 1
UNET Theta Warmup= 1
UNET ZTol= 0.02
UNET ZSATol= 0.05
UNET MxIter= 20
UNET MaxInSteps= 0
UNET DtIC= 0
UNET DtMin= 0
UNET MaxCRTS= 20
UNET WFStab= 2
UNET SFStab= 1
UNET WFX= 1
UNET SFX= 1
UNET DSS MLevel= 4
UNET DZMax Abort= 100
UNET Convert EG Bridges=-1
UNET Use Existing IB Tables=-1
UNET Froude Reduction=False
UNET Froude Limit= 1
UNET Froude Power= 10
UNET Time Slicing=0,0, 5
Instantaneous Interval=1HOUR
Write IC File= 0
Echo Input=False
Echo Output=False
Write Detailed= 0
Detailed Automatic Start=False, 10
WQ ULTIMATE=-1
WQ Max Comp Step=1HOUR
WQ Output Interval=15MIN
WQ Output Selected Increments= 0
WQ Output face flow=0
WQ Output face velocity=0
WQ Output face area=0
WQ Output face dispersion=0
WQ Output cell volume=0
WQ Output cell surface area=0
WQ Output cell continuity=0
WQ Output face conc=0
WQ Output face dconc_dx=0
WQ Output face courant=0
WQ Output face peclet=0
WQ Output face adv mass=0
WQ Output face disp mass=0
WQ Output cell mass=0
WQ Output cell source sink temp=0
WQ Output cell source sink nsm=0
WQ Output MaxMinRange=-1
WQ Daily Max Min Mean=-1
WQ Daily Range=0
WQ Daily Time=0
WQ Create Restart=0
WQ Fixed Restart=0
WQ System Summary=False
Sorting and Armoring Iterations= 10
XS Update Threshold= 0.02
Hydraulics Update Threshold= 0.02
Energy Slope Method= 1
Volume Change Method= 0
XS Weighting Method= 0
Number of US Weighted Cross Sections= 1
Number of DS Weighted Cross Sections= 1
Upstream XS Weight=0.25
Main XS Weight=0.5
Downstream XS Weight=0.25
Number of DS XS's Weighted with US Boundary= 1
Upstream Boundary Weight= 1
Weight of XSs Associated with US Boundary= 0
Number of US XS's Weighted with DS Boundary= 1
Downstream Boundary Weight= 0.5
Weight of XSs Associated with DS Boundary= 0.5
Sediment Output Level= 4
Mass or Volume Output= 0
Output Increment Type= 1
Profile and TS Output Increment= 10
XS Output Flag= 0
XS Output Increment= 10
Disregard all LS=0
Disregard all Conn=0
Disregard all Breaches=0
Disregard all Pumps=0

--- LittleNortheast.p02 (plan) ---

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Plan Title=Little Northeast Creek Floodway
Short Identifier=floodway
Geom File=g03
Flow File=f02
Encroach Param=-1 ,0,0, 2
Encroach River=Little NE Creek
Encroach Reach=Upper
Encroach Node=9253.031
       1    1250 1371.01
Encroach Node=8563.015
       1    1101    1210
Encroach Node=7013.623
       1    1800    2400
Encroach Node=5760.531
       1 1718.38    2060
Encroach Node=4350.856
       1    1240    1420
Encroach Node=4034.633
       1     905    1205
Encroach Node=3939.975
       1     848    1125
Encroach Node=3350.859
       1    1123    1228
Encroach Node=2260.004
       1     900    1030
Encroach Node=1586.992
       1 1097.94    1340
Encroach Node=753.6617
       1 1511.42 1611.17
Encroach Node=527.3250
       1 1562.37 1659.67
Encroach Node=219.2820
       1    1285

--- LittleNortheast.f01 (steady flow) ---

Flow Title=Little Northeast Creek Frequency Flows
Program Version=4.00
Number of Profiles= 5
Profile Names=10-YR,50-YR,100-YR,500-YR,100-ULT
River Rch & RM=Little NE Creek,Upper           ,56870.51
     760    1600    2130    3950    2220
River Rch & RM=Little NE Creek,Upper           ,49112.83
     990    2050    2720    5000    2920
River Rch & RM=Little NE Creek,Upper           ,48068.50
    1160    2390    3160    5770    3440
River Rch & RM=Little NE Creek,Upper           ,43676.87
    1340    2740    3620    6560    3820
River Rch & RM=Little NE Creek,Upper           ,36851.42
    1630    3320    4360    7840    4530
River Rch & RM=Little NE Creek,Upper           ,32404.68
    1670    3390    4450    7990    4600
River Rch & RM=Little NE Creek,Upper           ,31989.48
    2400    4810    6280   11100    6490
River Rch & RM=Little NE Creek,Upper           ,26452.43
    2490    4980    6490   11500    6660
River Rch & RM=Little NE Creek,Upper           ,18657.62
    2610    5190    6750   11900    6920
River Rch & RM=Little NE Creek,Upper           ,13091.96
    2680    5370    7000   12310    7200
River Rch & RM=Little NE Creek,Upper           ,7013.623
    2760    5620    7340   13030    7770
River Rch & RM=Little NE Creek,Upper           ,4034.633
    2860    5890    7710   13710    9290
River Rch & RM=Little NE Creek,Upper           ,753.6617
    2890    5980    7840   13920    9480
Boundary for River Rch & Prof#=Little NE Creek,Upper           , 1
Up Type= 0
Dn Type= 3
Dn Slope=0.002
Boundary for River Rch & Prof#=Little NE Creek,Upper           , 2
Up Type= 0
Dn Type= 3
Dn Slope=0.002
Boundary for River Rch & Prof#=Little NE Creek,Upper           , 3
Up Type= 0
Dn Type= 3
Dn Slope=0.002
Boundary for River Rch & Prof#=Little NE Creek,Upper           , 4
Up Type= 0
Dn Type= 3
Dn Slope=0.002
Boundary for River Rch & Prof#=Little NE Creek,Upper           , 5
Up Type= 0
Dn Type= 3
Dn Slope=0.002
DSS Import GetInterval= 0
DSS Import GetPeak= 0
DSS Import FillOption= 0

--- LittleNortheast.f02 (steady flow) ---

Flow Title=Little Northeast Floodway Flows
Program Version=4.00
Number of Profiles= 2
Profile Names=100-yr,Floodway
River Rch & RM=Little NE Creek,Upper           ,56870.51
    2130    2130
River Rch & RM=Little NE Creek,Upper           ,49112.83
    2720    2720
River Rch & RM=Little NE Creek,Upper           ,48068.50
    3160    3160
River Rch & RM=Little NE Creek,Upper           ,43676.87
    3620    3620
River Rch & RM=Little NE Creek,Upper           ,36851.42
    4360    4360
River Rch & RM=Little NE Creek,Upper           ,32404.68
    4450    4450
River Rch & RM=Little NE Creek,Upper           ,31989.48
    6280    6280
River Rch & RM=Little NE Creek,Upper           ,26452.43
    6490    6490
River Rch & RM=Little NE Creek,Upper           ,18657.62
    6750    6750
River Rch & RM=Little NE Creek,Upper           ,13091.96
    7000    7000
River Rch & RM=Little NE Creek,Upper           ,7013.623
    7340    7340
River Rch & RM=Little NE Creek,Upper           ,4034.633
    7710    7710
River Rch & RM=Little NE Creek,Upper           ,753.6617
    7840    7840
Boundary for River Rch & Prof#=Little NE Creek,Upper           , 1
Up Type= 0
Dn Type= 1
Dn Known WS=35.26
Boundary for River Rch & Prof#=Little NE Creek,Upper           , 2
Up Type= 0
Dn Type= 1
Dn Known WS=36.26
DSS Import GetInterval= 0
DSS Import GetPeak= 0
DSS Import FillOption= 0

--- LittleNortheast.g03 (geometry) ---

Geom Title=Little Northeast Creek Geometry
Program Version=4.00

River Reach=Little NE Creek ,Upper
Reach XY= 30
 1606176.6227056  750719.8351419 1606701.8737785  748116.0223234
 1608202.4436975  746880.8271417 1608293.8620303  745889.9127764
 1609446.0718837   745432.944343 1608510.1699721  742672.9887055
 1609317.1466205   741115.380524  1614107.913906  740967.3552216
 1614477.4996609  739519.0947634 1616284.3633516  737870.2838956
 1613712.0655974  735071.6506792 1613750.7326797  733410.1915667
 1611948.1769945  731773.0739416 1612805.7523122  729728.3263964
 1612364.7075776  728365.6956494 1613214.0320801  726739.3483265
 1612130.1048662  725513.1258219 1612338.7727924   724503.211259
 1611146.6446866  723891.8819657 1613348.6873552  721407.5724359
 1613878.7134378  719294.1531191 1615470.7016896  719056.8351344
 1616713.4112624  718036.2072511 1616909.8896293  715667.5332114
 1616207.9631955  714563.0734555 1616346.4384784   713061.332888
 1614501.3747097   712036.138294  1613119.675878   712368.440269
 1611848.3792907  710615.0953914 1611909.4994155  709681.5809847

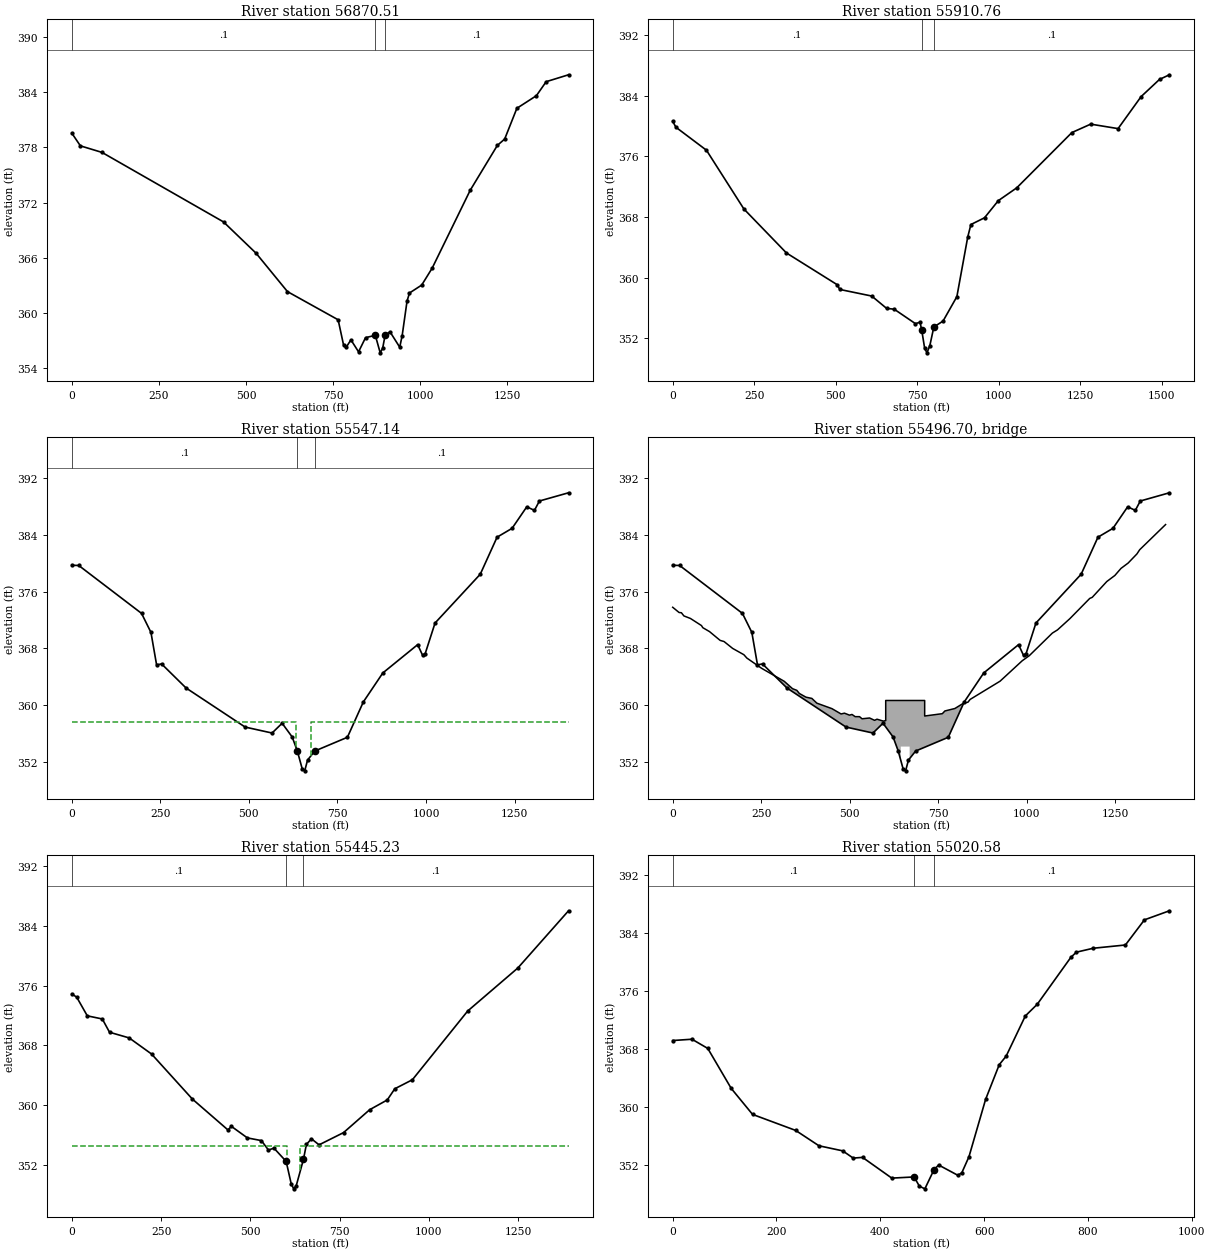
Type RM Length L Ch R = 1 ,56870.51,801.15,959.75,853.62
XS GIS Cut Line= 2
 1609501.0294675  743104.4434167  1608076.337979  743045.4325267
#Sta/Elev= 30
       0  379.54   24.63  378.16    86.6  377.45  435.44   369.9  528.93   366.5
  619.06  362.33  764.53  359.27   780.2  356.51   787.2  356.26  801.22  357.09
  823.11  355.79   843.2  357.33  871.28  357.58  885.29  355.68  892.29  356.17
   899.3  357.58  913.31  357.97  941.34  356.29  948.34  357.55  962.35  361.31
  969.36  362.18 1004.39  363.04 1034.46  364.88  1143.7  373.34 1221.58  378.21
 1242.59   378.9 1277.62  382.24 1333.67  383.61  1361.7  385.13 1425.91  385.88
#Mann= 3 , 0 , 0
       0      .1       0  871.28    .045       0   899.3      .1       0
Bank Sta=871.28,899.3
XS Rating Curve= 0 ,0
Exp/Cntr=0.3,0.1

Type RM Length L Ch R = 1 ,55910.76,300.57,363.62,333.67
XS GIS Cut Line= 2
 1609634.2756335  742549.6621191 1608124.3923655  742343.8858645
#Sta/Elev= 30
       0  380.62    9.87  379.84  103.54  376.81  218.44  369.06  348.97  363.26
   504.4  359.08  512.52  358.45  610.51  357.58     656  355.96  679.69  355.84
   744.6  353.94  758.72  354.13  763.95  353.09  772.85  350.71  779.92  350.09
  788.82  351.04  801.11   353.5  829.37  354.28  871.76   357.5  905.13  365.37
  914.79  367.01  956.54   367.9  998.92  370.16 1055.44  371.85 1224.59  379.14
 1282.32  380.25 1366.29  379.66 1436.94  383.88 1493.45  386.15 1523.84  386.76
#Mann= 3 , 0 , 0
       0      .1       0  763.95    .045       0  801.11      .1       0
Bank Sta=763.95,801.11
XS Rating Curve= 0 ,0
Exp/Cntr=0.5,0.3

Type RM Length L Ch R = 1 ,55547.14,103.14,101.91,112.11
XS GIS Cut Line= 3
 1609671.8888811  742332.7032735 1608715.3893348  742181.1624595
 1608282.4541112  742153.1864188
#Sta/Elev= 30
       0   379.7   19.63  379.67  196.81  372.92  223.39  370.24  239.34  365.66
  253.51  365.79  322.49   362.4   489.3  356.89  565.35  356.05   593.7  357.43
  622.05   355.5  636.45  353.55   650.4  351.01  657.49  350.72  665.53  352.24
  685.84  353.51  777.97  355.45  822.95  360.43  878.02  364.52  976.34  368.51
  990.36     367  997.38  367.21 1025.44  371.56 1153.08  378.44  1200.5  383.66
 1242.89  384.91 1284.33  387.94 1306.02  387.44 1320.05  388.76 1402.27  389.92
#Mann= 3 , 0 , 0
       0      .1       0  636.45     .04       0  685.84      .1       0
#XS Ineff= 2 , 0
          632.33  357.63  674.96          357.63
Permanent Ineff=
       F       F
Bank Sta=636.45,685.84
XS Rating Curve= 0 ,0
Exp/Cntr=0.5,0.3

Type RM Length L Ch R = 3 ,55496.70,,,
BEGIN DESCRIPTION:
Hw 273 Telegraph Rd
END DESCRIPTION:
Bridge Culvert--1,0,-1,-1, 0
Deck Dist Width WeirC Skew NumUp NumDn MinLoCord MaxHiCord MaxSubmerge Is_Ogee
35,45,2.6,0, 60, 60, , , 0.95, 0, 0,0,,
       0   18.04   24.51   31.59   50.11   81.18   85.01  103.92   133.9  144.92
  169.21  200.93  209.31  251.15  314.92  338.31  350.34  357.42  376.08  392.84
     407   449.5  475.23  484.92  499.08  506.17  515.06  527.42   534.5  555.75
  569.92  576.74  594.68  601.33  601.33  643.83  668.83  711.33  711.33  761.22
   768.3  796.65  819.72  833.54  839.67  924.19  986.72 1006.51  1071.8 1086.26
 1121.31 1177.37 1184.38 1225.48 1248.15 1265.56 1285.61 1310.53  1318.3 1391.42
  373.78  373.04  373.01  372.56   372.2   371.2   370.9  370.35  369.11  368.95
  367.98  367.09  366.62  365.17  363.34   362.3  362.07  361.63  361.11  360.93
  360.26  359.49  358.74  358.85  358.57  358.67  358.36  358.36  358.06  358.17
  357.84     358  357.73   357.8  360.64  360.64  360.64  360.64  358.45  358.78
  359.16  359.51  360.22   360.4  360.79  363.36  366.24  366.95  370.14  370.59
  372.18  375.03  375.18  377.41  378.26  379.26  380.01   381.3  381.89  385.44
                                                                                
                                                                                
                                                                                
                                          354.14  354.14
                                                                                
                                                                                
       0   18.04   24.51   31.59   50.11   81.18   85.01  103.92   133.9  144.92
  169.21  200.93  209.31  251.15  314.92  338.31  350.34  357.42  376.08  392.84
     407   449.5  475.23  484.92  499.08  506.17  515.06  527.42   534.5  546.27
  562.83  566.43  566.43  608.93  633.93  676.43  676.43  707.98  725.79  761.22
   768.3  796.65  819.72  833.54  839.67  924.19  986.72 1006.51  1071.8 1086.26
 1121.31 1177.37 1184.38 1225.48 1248.15 1265.56 1285.61 1310.53  1318.3 1391.42
  373.78  373.04  373.01  372.56   372.2   371.2   370.9  370.35  369.11  368.95
  367.98  367.09  366.62  365.17  363.34   362.3  362.07  361.63  361.11  360.93
  360.26  359.49  358.74  358.85  358.57  358.67  358.36  358.36  358.06   358.2
  357.99  357.99  360.64  360.64  360.64  360.64  358.09  358.08  358.51  358.78
  359.16  359.51  360.22   360.4  360.79  363.36  366.24  366.95  370.14  370.59
  372.18  375.03  375.18  377.41  378.26  379.26  380.01   381.3  381.89  385.44
                                                                                
                                                                                
                                                                                
                          354.14  354.14
                                                                                
                                                                                
BR Coef=-1 , 0 , 0 ,, 0 ,,,0.8,0,,0,
WSPro=,,,, 1 ,,,, 0 ,,,, 0 ,,,,-1 ,-1 ,-1 , 0 , 0 , 0 , 0 , 0
BC Design=,, 0 ,, 0 ,,,,,,
BC Use User HTab Curves=0
BC User HTab FreeFlow(D)= 0

Type RM Length L Ch R = 1 ,55445.23,414.26,424.65,424.3
XS GIS Cut Line= 4
 1609678.4067655  742233.3055353 1608858.7827931  742104.5773169
 1608521.4822717  742068.7289523 1608299.8741996  742055.6931834
#Sta/Elev= 30
       0   374.9   13.75  374.46   43.35  371.96   85.38  371.54  105.61  369.76
  160.62     369  223.29  366.84  337.56   360.8   437.2  356.66  446.84  357.14
  491.59  355.59   530.9  355.23  550.57  353.96  565.92  354.22  600.17  352.44
  614.35  349.43  621.43  348.76  628.52   349.2  648.59  352.71  656.86  354.72
  671.03  355.47  692.29  354.66  760.87   356.3  833.98  359.37  883.25  360.68
  904.37  362.18  953.65  363.39 1108.52  372.61 1248.99  378.38 1390.86  386.05
#Mann= 3 , 0 , 0
       0      .1       0  600.17     .04       0  648.59      .1       0
#XS Ineff= 2 , 0
          603.02   354.5  640.32           354.5
Permanent Ineff=
       F       F
Bank Sta=600.17,648.59
XS Rating Curve= 0 ,0
Exp/Cntr=0.5,0.3

Type RM Length L Ch R = 1 ,55020.58,701.11,766.69,766.76
XS GIS Cut Line= 3
 1609558.8994417   741982.323658 1609286.1708028  741810.2966044
 1608705.4244844  741554.2194875
#Sta/Elev= 30
       0  369.21   37.14  369.39   67.59  368.12  112.79   362.6  153.86  359.02
  236.93  356.81  281.81  354.69  327.56  353.99  347.83  352.99  365.81  353.09
  422.16  350.23  465.26  350.39  475.26  349.12  485.87  348.75  503.51  351.39
  512.42  352.04  549.41  350.62  557.06  350.96  570.82  353.17  602.97   361.1
  629.22  365.88  642.49  367.05  679.47   372.6  702.42  374.21  767.26  380.69
  777.88   381.4  810.22  381.94  872.33  382.39  908.98  385.86  957.15  387.11
#Mann= 3 , 0 , 0
       0      .1       0  465.26    .045       0  503.51      .1       0
Bank Sta=465.26,503.51
XS Rating Curve= 0 ,0
Exp/Cntr=0.3,0.1

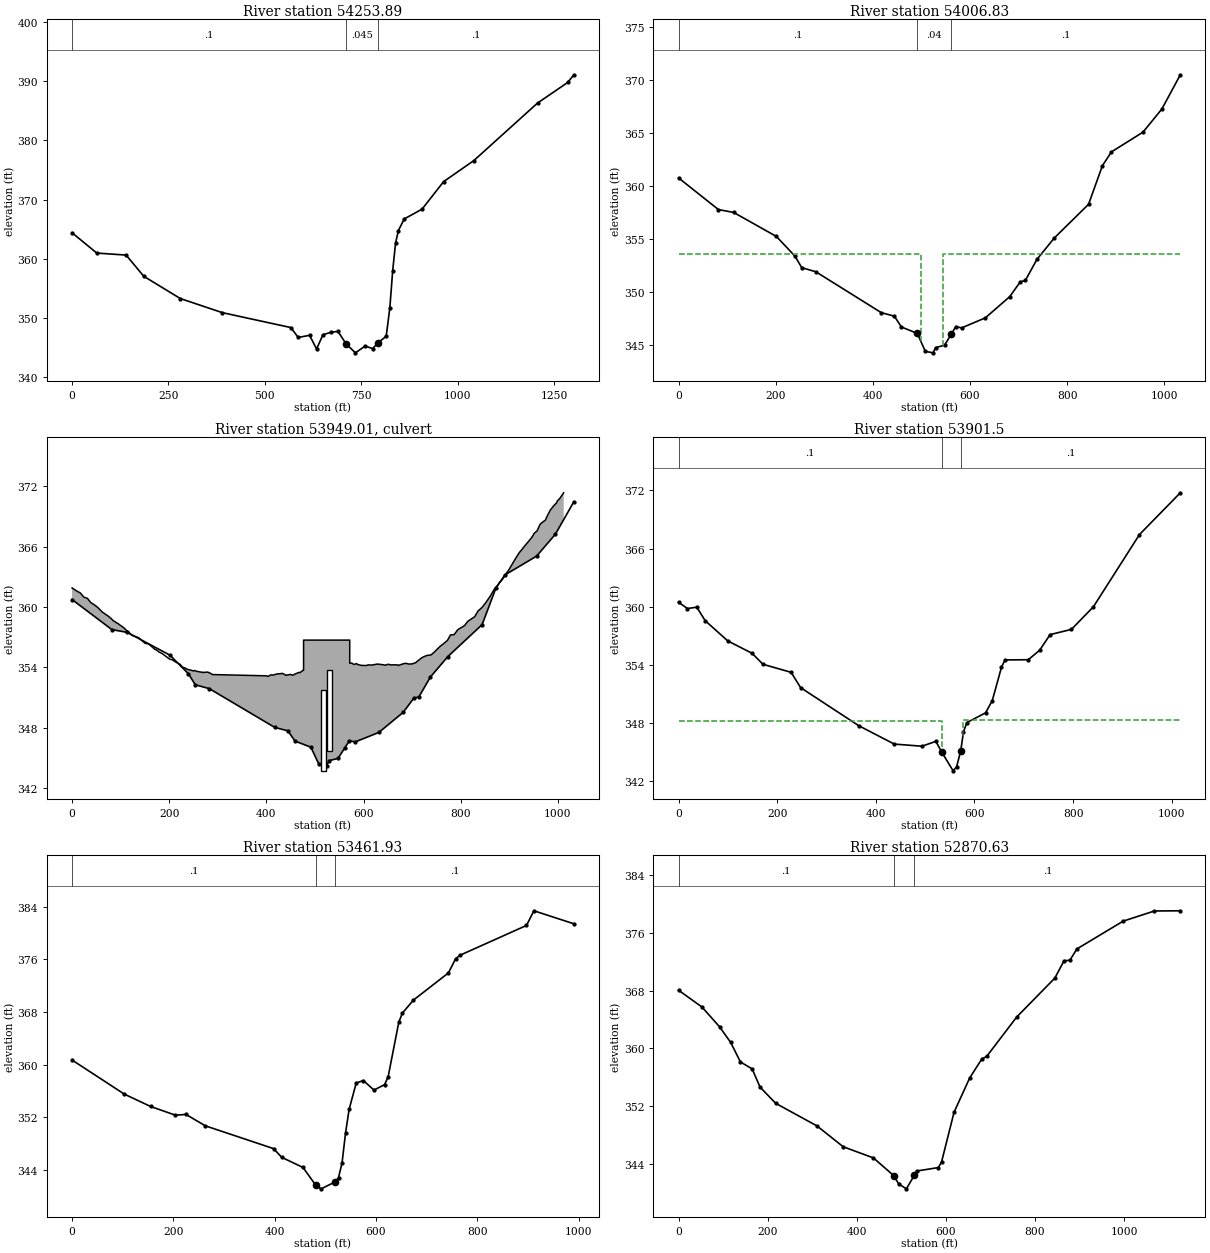
Type RM Length L Ch R = 1 ,54253.89,187.12,247.06,239.07
XS GIS Cut Line= 4
 1609602.1909933  741806.2038355 1609437.0733895  741231.8366887
 1609323.8964495  740916.3130983 1609179.8530713  740576.7822783
#Sta/Elev= 30
       0  364.39   64.16  360.96  140.21  360.62  185.94  357.04  280.63  353.28
  389.88  350.89  567.66  348.37  586.53   346.7  616.05  347.06  634.31  344.75
  650.73  347.15  672.62   347.6  689.86  347.71  710.94   345.6  735.04   344.1
   760.2  345.25  779.66  344.82  794.14  345.82  814.93  346.91  824.28  351.71
  831.71  357.99  839.15  362.66  846.59  364.77  861.46  366.72  907.98  368.39
  963.75  373.03 1042.18  376.59 1207.57  386.32 1285.67  389.79 1301.66  391.09
#Mann= 3 , 0 , 0
       0      .1       0  710.94    .045       0  794.14      .1       0
Bank Sta=710.94,794.14
XS Rating Curve= 0 ,0
Exp/Cntr=0.5,0.3

Type RM Length L Ch R = 1 ,54006.83,105.82,105.33,106.7
XS GIS Cut Line= 6
 1609634.4110453  741698.8390085 1609645.8173432  741446.2709852
 1609594.0770689  741258.8818066 1609594.0770689  741058.4568591
 1609639.2994587   740890.621334 1609595.3037385   740683.678502
#Sta/Elev= 30
       0  360.73   82.11  357.74  113.45  357.47  201.54   355.2  239.58  353.35
  253.63  352.26  282.67  351.87  417.51  348.01  444.29  347.68   458.9  346.66
  491.61  346.05  508.03  344.36  524.19  344.22  529.03  344.71  547.61  344.94
  561.61  345.99   570.9   346.7  582.61  346.57  631.61  347.52  681.78  349.52
  703.53  350.92  713.98  351.05  737.68  353.03   773.6  355.06  844.17  358.24
  872.53  361.87  891.12  363.18   956.3  365.05  995.03  367.23 1033.04  370.46
#Mann= 3 , 0 , 0
       0      .1       0  491.61     .04       0  561.61      .1       0
#XS Ineff= 2 , 0
          499.82  353.54  543.52          353.54
Permanent Ineff=
       F       F
Bank Sta=491.61,561.61
XS Rating Curve= 0 ,0
Exp/Cntr=0.5,0.3

Type RM Length L Ch R = 2 ,53949.01,,,
BEGIN DESCRIPTION:
Springfield Dr
END DESCRIPTION:
Bridge Culvert--1,0,-1,-1, 0
Deck Dist Width WeirC Skew NumUp NumDn MinLoCord MaxHiCord MaxSubmerge Is_Ogee
30,42,2.6,0, 190, 194, , , 0.95, 0, 0,0,,
       0     .44    9.56   10.32   16.97   17.66   23.72   24.31   24.38   31.35
   31.79   38.36   44.26   46.61   52.38   62.24    66.4   74.89   80.42   84.17
   91.08   94.44   97.47   105.9  108.47  118.74  122.49  124.07  135.54  136.51
  137.37  143.52  144.02  150.53  153.41  157.33  157.77  170.63  171.56  177.28
  178.57     180  185.58  189.48   199.6  202.24  206.61  210.53  220.63  222.27
  227.64   233.3  234.65  237.13  248.67  250.44  252.03  257.09  265.73  268.93
  269.33  270.28  271.56  279.09  283.92  289.56   293.3  390.71  399.56  403.19
   409.2  412.97  424.43   425.9  426.55  433.28  437.96  440.39  449.37  454.62
  455.57  456.13  466.85  468.64  473.68  475.64  476.62  476.62  571.62  571.62
  575.98  580.68  585.58  587.68  589.67  594.21  594.68  604.94  607.75  610.55
  615.68  628.98  641.81  643.68  648.81  650.68  655.81  657.68  659.55  669.81
  671.68  673.55  683.81  687.55  692.68  695.25  699.97  703.73  706.98  710.09
  719.96  721.59  723.73   728.9  729.35  730.84  738.76  745.75  757.46  762.53
  772.75  776.13  779.02  779.89  786.62   786.9  787.43  793.91  794.17   800.8
  807.92  814.38  815.21  816.15  828.93  834.59  835.94  841.32   844.7  849.95
     852  859.29  861.53  867.38  870.45  876.88  877.98  880.01  884.99   896.6
  898.45     899  912.62  913.02  920.01  920.03  920.06  920.66  927.04  928.16
  940.41  945.93  948.32  951.59  955.55  957.32  962.79  963.05  964.04  970.03
  974.51  977.27  981.99  984.51  991.55  997.44  998.98 1003.17 1011.46 1012.07
  361.89  361.87  361.59  361.56  361.39  361.35  361.01  360.98  360.97  360.86
  360.84  360.44  360.26  360.18  359.97  359.49  359.35  359.07  358.85  358.66
  358.44  358.35  358.24  357.95  357.83  357.39  357.21  357.16  356.97  356.95
  356.92  356.67  356.64  356.37  356.36  356.33  356.31  355.77  355.77   355.6
  355.52   355.5  355.36  355.22  354.85  354.79  354.74   354.6  354.33  354.29
     354  353.92  353.86   353.8  353.65  353.63  353.68  353.59  353.52  353.49
  353.47  353.49  353.49  353.52  353.42  353.27  353.27  353.15  353.15  353.09
  353.24  353.22  353.36  353.35  353.35  353.39  353.27   353.2  353.29   353.2
  353.24  353.26  353.49  353.45  353.64   353.7   353.7   356.7   356.7  354.41
  354.41  354.27  354.37  354.28  354.26   354.2  354.19  354.17   354.2  354.24
  354.21  354.32  354.24   354.2  354.26   354.3  354.24  354.23  354.24  354.24
  354.17  354.22  354.37  354.39  354.32  354.32  354.33   354.4  354.44  354.57
  354.95  354.98  355.04  355.14  355.14  355.18  355.22  355.51  356.07  356.26
  356.67  356.97  357.21  357.22  357.24  357.25   357.3  357.73  357.74  357.93
  358.14  358.55  358.58  358.62  359.03   359.5  359.61  359.83  359.99  360.31
  360.45  360.97  361.12  361.61  361.84   362.2  362.29  362.43  362.68  363.52
  363.63  363.67   364.8  364.82  365.36  365.36  365.37   365.4  365.76  365.85
  366.55  366.88  367.06  367.33  367.48  367.56  368.15  368.17  368.24  368.48
  368.63  368.95   369.4  369.63  370.06  370.35  370.54  370.73   371.3  371.35
                                                                                
                                                                                
                                                                                
                                                                                
                                                                                
                                                                                
                                                                                
                                                                                
                                                                                
                                                                                
                                                                                
                                                                                
                                                                                
                                                                                
                                                                                
                                                                                
                                                                                
                                                                                
                                                                                
       0     .44    9.56   10.32   16.97   17.66   23.72   24.31   24.38   31.35
   31.79   38.36   44.26   46.61   52.38   62.24    66.4   74.89   80.42   84.17
   91.08   94.44   97.47   105.9  108.47  118.74  122.49  124.07  135.54  136.51
  137.37  143.52  144.02  150.53  153.41  157.33  157.77  170.63  171.56  177.28
  178.57     180  185.58  189.48   199.6  202.24  206.61  210.53  220.63  222.27
  227.64   233.3  234.65  237.13  248.67  250.44  252.03  257.09  265.73  268.93
  269.33  270.28  271.56  279.09  283.92  289.56   293.3  294.79  389.79   390.6
  399.56  403.19   409.2  412.97  424.43   425.9  426.55  433.28  437.96  440.39
  449.37  454.62  455.57  456.13  466.85  468.64  473.68  475.64  477.71  482.64
   484.9  489.64  492.09  496.65  500.97  503.65  507.79  509.26  509.26  604.26
  604.26  604.94  607.75  610.55  615.68  628.98  641.81  643.68  648.81  650.68
  655.81  657.68  659.55  669.81  671.68  673.55  683.81  687.55  692.68  695.25
  699.97  703.73  706.98  710.09  719.96  721.59  723.73   728.9  729.35  730.84
  738.76  745.75  757.46  762.53  772.75  776.13  779.02  779.89  786.62   786.9
  787.43  793.91  794.17   800.8  807.92  814.38  815.21  816.15  828.93  834.59
  835.94  841.32   844.7  849.95     852  859.29  861.53  867.38  870.45  876.88
  877.98  880.01  884.99   896.6  898.45     899  912.62  913.02  920.01  920.03
  920.06  920.66  927.04  928.16  940.41  945.93  948.32  951.59  955.55  957.32
  962.79  963.05  964.04  970.03  974.51  977.27  981.99  984.51  991.55  997.44
  998.98 1003.17 1011.46 1012.07
  361.89  361.87  361.59  361.56  361.39  361.35  361.01  360.98  360.97  360.86
  360.84  360.44  360.26  360.18  359.97  359.49  359.35  359.07  358.85  358.66
  358.44  358.35  358.24  357.95  357.83  357.39  357.21  357.16  356.97  356.95
  356.92  356.67  356.64  356.37  356.36  356.33  356.31  355.77  355.77   355.6
  355.52   355.5  355.36  355.22  354.85  354.79  354.74   354.6  354.33  354.29
     354  353.92  353.86   353.8  353.65  353.63  353.68  353.59  353.52  353.49
  353.47  353.49  353.49  353.52  353.42  353.27  353.27  353.27  353.14  353.17
  353.15  353.09  353.24  353.22  353.36  353.35  353.35  353.39  353.27   353.2
  353.29   353.2  353.24  353.26  353.49  353.45  353.64   353.7  353.77  353.79
  353.83  353.89  353.88  353.85   353.9  354.03  354.05  354.05   356.7   356.7
  354.17  354.17   354.2  354.24  354.21  354.32  354.24   354.2  354.26   354.3
  354.24  354.23  354.24  354.24  354.17  354.22  354.37  354.39  354.32  354.32
  354.33   354.4  354.44  354.57  354.95  354.98  355.04  355.14  355.14  355.18
  355.22  355.51  356.07  356.26  356.67  356.97  357.21  357.22  357.24  357.25
   357.3  357.73  357.74  357.93  358.14  358.55  358.58  358.62  359.03   359.5
  359.61  359.83  359.99  360.31  360.45  360.97  361.12  361.61  361.84   362.2
  362.29  362.43  362.68  363.52  363.63  363.67   364.8  364.82  365.36  365.36
  365.37   365.4  365.76  365.85  366.55  366.88  367.06  367.33  367.48  367.56
  368.15  368.17  368.24  368.48  368.63  368.95   369.4  369.63  370.06  370.35
  370.54  370.73   371.3  371.35
                                                                                
                                                                                
                                                                                
                                                                                
                                                                                
                                                                                
                                                                                
                                                                                
                                                                                
                                                                                
                                                                                
                                                                                
                                                                                
                                                                                
                                                                                
                                                                                
                                                                                
                                                                                
                                                                                
                                
BR Coef=-1 , 0 , 0 ,, 0 ,,,0.8,0,,0,
WSPro=,,,, 1 ,,,, 0 ,,,, 0 ,,,,-1 ,-1 ,-1 , 0 , 0 , 0 , 0 , 0
Culvert=2,8,10,44,0.011,0.4,1,8,1,343.7,518.12,342.2,550.79,Culvert #1  , 0 ,30
Culvert Bottom n=0.011
Culvert=2,8,10,44,0.011,0.4,1,8,1,345.7,530.12,344.2,562.79,Culvert #2  , 0 ,30
Culvert Bottom n=0.011
BC Design=,, 0 ,, 0 ,,,,,,
BC Use User HTab Curves=0
BC User HTab FreeFlow(D)= 0

Type RM Length L Ch R = 1 ,53901.5 ,405.86,439.57,407.22
XS GIS Cut Line= 5
 1609701.2193612  741692.3211241 1609721.6399335  741433.1751276
 1609696.3309478  741156.2251262 1609699.5898901  741042.1621479
 1609737.0677258  740678.7900886
#Sta/Elev= 30
       0  360.46   18.17  359.82   36.94  359.96   54.02  358.57   99.85  356.48
  149.28   355.2  171.18  354.07  228.36  353.24  247.59  351.66  365.28  347.74
  437.36  345.84  493.59  345.62  521.71  346.12  533.52  345.03  556.79  343.08
  563.79  343.49   572.2  345.14  577.79  347.12   584.8  348.06  622.57  349.06
  636.19  350.33  654.84  353.77  661.88  354.52  709.16  354.54  732.25  355.52
  753.36  357.13  796.67  357.67  841.33  360.01   934.6  367.45 1017.46  371.76
#Mann= 3 , 0 , 0
       0      .1       0  533.52     .04       0   572.2      .1       0
#XS Ineff= 2 , 0
          534.99  348.24  576.55          348.28
Permanent Ineff=
       F       F
Bank Sta=533.52,572.2
XS Rating Curve= 0 ,0
Exp/Cntr=0.5,0.3

Type RM Length L Ch R = 1 ,53461.93,580.44,591.3,589.37
XS GIS Cut Line= 2
 1610065.2820534  741677.3202888 1610095.2908552  740687.0298316
#Sta/Elev= 30
       0   360.7  102.97  355.52  154.89  353.64  203.91  352.31  224.92  352.42
  263.07  350.69  397.83  347.22  414.01  345.89  456.03  344.35  480.75341.6845
  491.72   341.1  519.72342.1653  526.06  342.81  533.06  345.05  540.07  349.67
  547.07  353.22  561.08  357.21  575.08  357.58  596.09  356.13   617.1  356.96
  624.11  358.18  645.12  366.47  652.12  367.83  673.93  369.82  743.16  373.96
  757.17   376.1  766.67  376.67  897.23  381.18  911.84  383.41  990.74  381.43
#Mann= 3 , 0 , 0
       0      .1       0  480.75    .045       0  519.72      .1       0
Bank Sta=480.75,519.72
XS Rating Curve= 0 ,0
Exp/Cntr=0.3,0.1

Type RM Length L Ch R = 1 ,52870.63,873.82,1073.27,677.93
XS GIS Cut Line= 3
  1610507.911879  741804.8576962 1610635.4492864  741227.1882628
 1610590.4360838   740694.532032
#Sta/Elev= 30
       0  368.06   52.59  365.73   92.17  362.98  117.11  360.81  138.91  358.11
  165.21  357.15  182.83  354.63  218.06  352.37  310.66  349.24  369.51  346.35
  437.34   344.8  482.71  342.36  494.05   341.2  511.38  340.51  529.34  342.41
  534.14  342.98  583.07  343.46  590.24  344.23  618.36  351.14  653.49   355.9
  680.35  358.49  691.67  358.89  758.86  364.34  844.49  369.74  865.15  372.15
  878.29  372.21  893.85  373.78  997.71  377.64 1067.96  379.05 1126.14  379.08
#Mann= 3 , 0 , 0
       0      .1       0  482.71    .045       0  529.34      .1       0
Bank Sta=482.71,529.34
XS Rating Curve= 0 ,0
Exp/Cntr=0.3,0.1

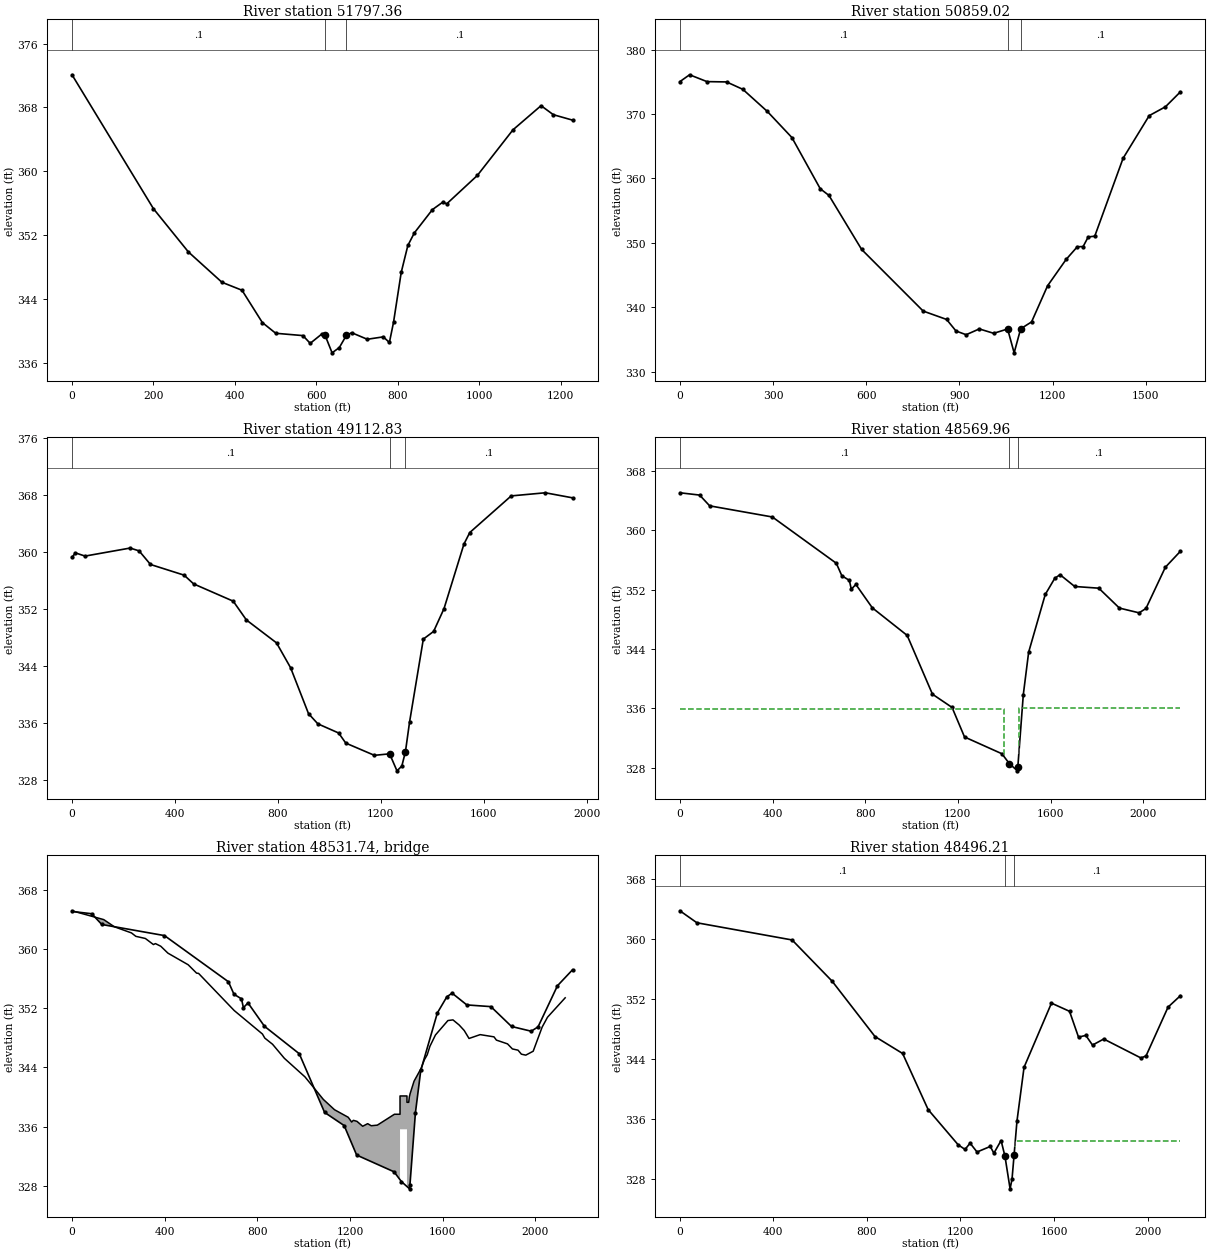
Type RM Length L Ch R = 1 ,51797.36,789.59,938.34,763.62
XS GIS Cut Line= 3
 1611378.1671293  741744.8400927 1611280.6385237  741347.2234697
 1610815.5020968  740672.0254307
#Sta/Elev= 30
       0  372.09   200.1  355.31  285.85   349.9  368.21   346.1  417.57   345.1
  467.54  341.05  500.36  339.71  567.14  339.42  585.08  338.45  614.12  339.64
  621.57  339.46   638.8  337.26  656.58  337.92   673.9  339.45  687.01  339.78
  725.17  338.96  764.49  339.26  779.59  338.56  789.66  341.07  808.58  347.33
  824.89  350.71  840.95  352.29  885.21   355.2  910.26  356.12  920.52  355.93
  995.58  359.48 1083.01  365.19 1152.04  368.22 1182.23  367.09 1229.31  366.41
#Mann= 3 , 0 , 0
       0      .1       0  621.57    .045       0   673.9      .1       0
Bank Sta=621.57,673.9
XS Rating Curve= 0 ,0
Exp/Cntr=0.3,0.1

Type RM Length L Ch R = 1 ,50859.02,1582.71,1746.19,1588.9
XS GIS Cut Line= 2
 1611775.0899565  741812.4659723 1611674.5824501  740204.3458709
#Sta/Elev= 30
       0  375.03   31.21  376.09   87.14  375.03  150.26  374.98  202.68  373.83
  281.54   370.4  360.62  366.35  451.85  358.41   479.9  357.37  585.11  348.99
  783.22  339.43  858.64  338.13  888.84  336.34  921.55  335.76  963.84  336.66
 1010.22  335.98 1055.02  336.65 1076.06  332.95  1097.1  336.68 1132.17  337.75
 1183.65  343.35 1243.36  347.44 1279.46  349.41 1298.11  349.44 1314.53  350.93
 1335.57  351.05 1426.74  363.13 1510.91  369.75 1563.29  371.13 1611.26  373.44
#Mann= 3 , 0 , 0
       0      .1       0 1055.02    .045       0  1097.1      .1       0
Bank Sta=1055.02,1097.1
XS Rating Curve= 0 ,0
Exp/Cntr=0.3,0.1

Type RM Length L Ch R = 1 ,49112.83,543.76,542.87,536.5
XS GIS Cut Line= 3
 1612818.7087437  741877.0942793 1613270.0576197  740387.6429887
 1613188.2401619   740007.700046
#Sta/Elev= 30
       0  359.23   13.14  359.86   50.81  359.41  225.99  360.54   260.8  360.14
  305.03  358.23  435.66  356.73  472.67   355.5  626.52  353.07  677.72  350.43
  794.75  347.21  849.53  343.71  919.09  337.26  955.27  335.83 1036.12  334.54
 1063.94  333.12 1175.09   331.4 1234.29  331.61 1262.87  329.22 1281.75  329.89
  1295.8  331.92 1311.73  336.07 1365.27  347.74 1405.25  348.82 1445.73  352.03
 1523.13   361.1 1545.77  362.72 1706.79  367.87 1839.31  368.31 1944.99   367.6
#Mann= 3 , 0 , 0
       0      .1       0 1234.29    .045       0  1295.8      .1       0
Bank Sta=1234.29,1295.8
XS Rating Curve= 0 ,0
Exp/Cntr=0.5,0.3

Type RM Length L Ch R = 1 ,48569.96,73.15,73.74,73.3
XS GIS Cut Line= 3
 1613120.3115923  742011.1399898 1613813.1830015  740486.8228898
 1613656.5904751  740026.4475847
#Sta/Elev= 30
       0  365.05   85.24  364.74  128.54  363.29   399.2  361.79  675.16  355.56
  699.24  353.87  731.65  353.25  739.96  352.06  759.74   352.7  830.81  349.55
  981.15  345.84 1090.37  337.92 1174.96  336.14 1228.78  332.16 1390.25   329.9
 1422.37  328.57 1457.34   327.6 1458.89  328.12 1482.52  337.86 1505.59  343.58
 1577.26  351.35 1618.09  353.52  1640.9  354.02 1704.38  352.43 1808.37   352.2
 1897.46  349.52 1982.38  348.88 2012.03  349.47 2095.75  355.02 2160.68  357.17
#Mann= 3 , 0 , 0
       0      .1       0 1422.37     .04       0 1458.89      .1       0
#XS Ineff= 2 , 0
         1400.98  335.99 1463.14          336.05
Permanent Ineff=
       F       F
Bank Sta=1422.37,1458.89
XS Rating Curve= 0 ,0
Exp/Cntr=0.5,0.3

Type RM Length L Ch R = 3 ,48531.74,,,
BEGIN DESCRIPTION:
Hw 545 Blue Ball Rd
END DESCRIPTION:
Bridge Culvert--1,0,-1,-1, 0
Deck Dist Width WeirC Skew NumUp NumDn MinLoCord MaxHiCord MaxSubmerge Is_Ogee
25,30,2.6,0, 60, 60, , , 0.95, 0, 0,0,,
       0   136.9  182.83  256.76  275.49  316.71  351.45  360.18  383.28  414.08
  501.61  537.88  546.29  700.33  822.15  832.34  865.75  916.83 1005.89 1085.05
 1133.34  1192.5 1207.12 1214.81 1230.21 1254.79 1276.41 1291.65 1318.16  1391.9
 1416.09 1416.09 1446.09 1446.09  1453.5 1456.48 1459.74 1476.55 1507.39 1520.77
 1533.46 1545.23 1568.99 1622.88 1644.64 1671.34 1693.09 1713.98 1762.02 1821.72
 1832.13 1880.17 1901.11  1925.5 1940.05 1958.96 1990.97  2029.7 2052.79 2129.06
  365.14  363.95  362.98  362.15  361.69   361.4  360.58  360.71  360.35  359.42
  357.85  356.72  356.69  351.67   348.5  347.95  347.12  345.22  342.71  339.67
  338.28  337.26  336.62  336.85  336.71  336.05   336.4  336.12   336.2  337.67
  337.67  340.14  340.14  339.28  339.28  340.04  340.46  342.13  343.88     345
   345.7  346.85  348.37  350.32  350.41  349.72  348.98   347.9  348.42  348.12
  347.68  347.17  346.49  346.32  345.78  345.65  346.18  349.44  350.77  353.39
                                                                                
                                                                                
                                                                                
          335.64  335.64
                                                                                
                                                                                
       0   136.9  182.83  256.76  275.49  316.71  351.45  360.18  383.28  414.08
  501.61  537.88  546.29  700.33  822.15  832.34  865.75  916.83  948.52  976.13
 1005.89 1085.05 1107.02 1133.34  1192.5 1207.12 1214.81 1230.21 1254.79 1276.41
 1291.65 1318.16  1397.2  1397.2  1427.2 1454.66 1468.89 1476.55 1507.39 1520.77
 1533.46 1545.23 1568.99 1622.88 1644.64 1671.34 1693.09 1713.98 1762.02 1821.72
 1832.13 1880.17 1901.11  1925.5 1940.05 1958.96 1990.97  2029.7 2052.79 2129.06
  365.14  363.95  362.98  362.15  361.69   361.4  360.58  360.71  360.35  359.42
  357.85  356.72  356.69  351.67   348.5  347.95  347.12  345.22  344.51  343.41
  342.71  339.67  339.22  338.28  337.26  336.62  336.85  336.71  336.05   336.4
  336.12   336.2  337.59  340.14  340.14  339.69  341.51  342.13  343.88     345
   345.7  346.85  348.37  350.32  350.41  349.72  348.98   347.9  348.42  348.12
  347.68  347.17  346.49  346.32  345.78  345.65  346.18  349.44  350.77  353.39
                                                                                
                                                                                
                                                                                
                          335.64  335.64
                                                                                
                                                                                
BR Coef=-1 , 0 , 0 ,, 0 ,,,0.8,0,,0,
WSPro=,,,, 1 ,,,, 0 ,,,, 0 ,,,,-1 ,-1 ,-1 , 0 , 0 , 0 , 0 , 0
BC Design=,, 0 ,, 0 ,,,,,,
BC Use User HTab Curves=0
BC User HTab FreeFlow(D)= 0

Type RM Length L Ch R = 1 ,48496.21,428.1,427.71,402.48
XS GIS Cut Line= 3
  1613195.485876  742007.5171328  1613901.942999  740471.4257473
 1613787.2502333  740036.4983354
#Sta/Elev= 30
       0  363.75   72.81  362.15  479.92  359.86  651.01  354.37  834.34  346.99
  952.56  344.73 1061.78  337.25 1190.17  332.56 1219.58  331.94 1241.02  332.78
 1270.87   331.6 1327.45  332.34 1342.86  331.44 1373.68  333.13 1390.29  331.03
  1412.2  326.69 1420.46  327.98 1429.39  331.23 1441.57  335.71 1471.91  342.89
 1589.18  351.44 1666.46  350.35 1704.85  346.91 1736.07  347.14 1764.71  345.85
 1812.71  346.66 1971.98  344.13  1993.7  344.41 2087.81  350.91 2140.55  352.43
#Mann= 3 , 0 , 0
       0      .1       0 1390.29     .04       0 1429.39      .1       0
#XS Ineff= 2 , 0
         1372.11  333.04 1432.06          333.04
Permanent Ineff=
       F       F
Bank Sta=1390.29,1429.39
XS Rating Curve= 0 ,0
Exp/Cntr=0.5,0.3

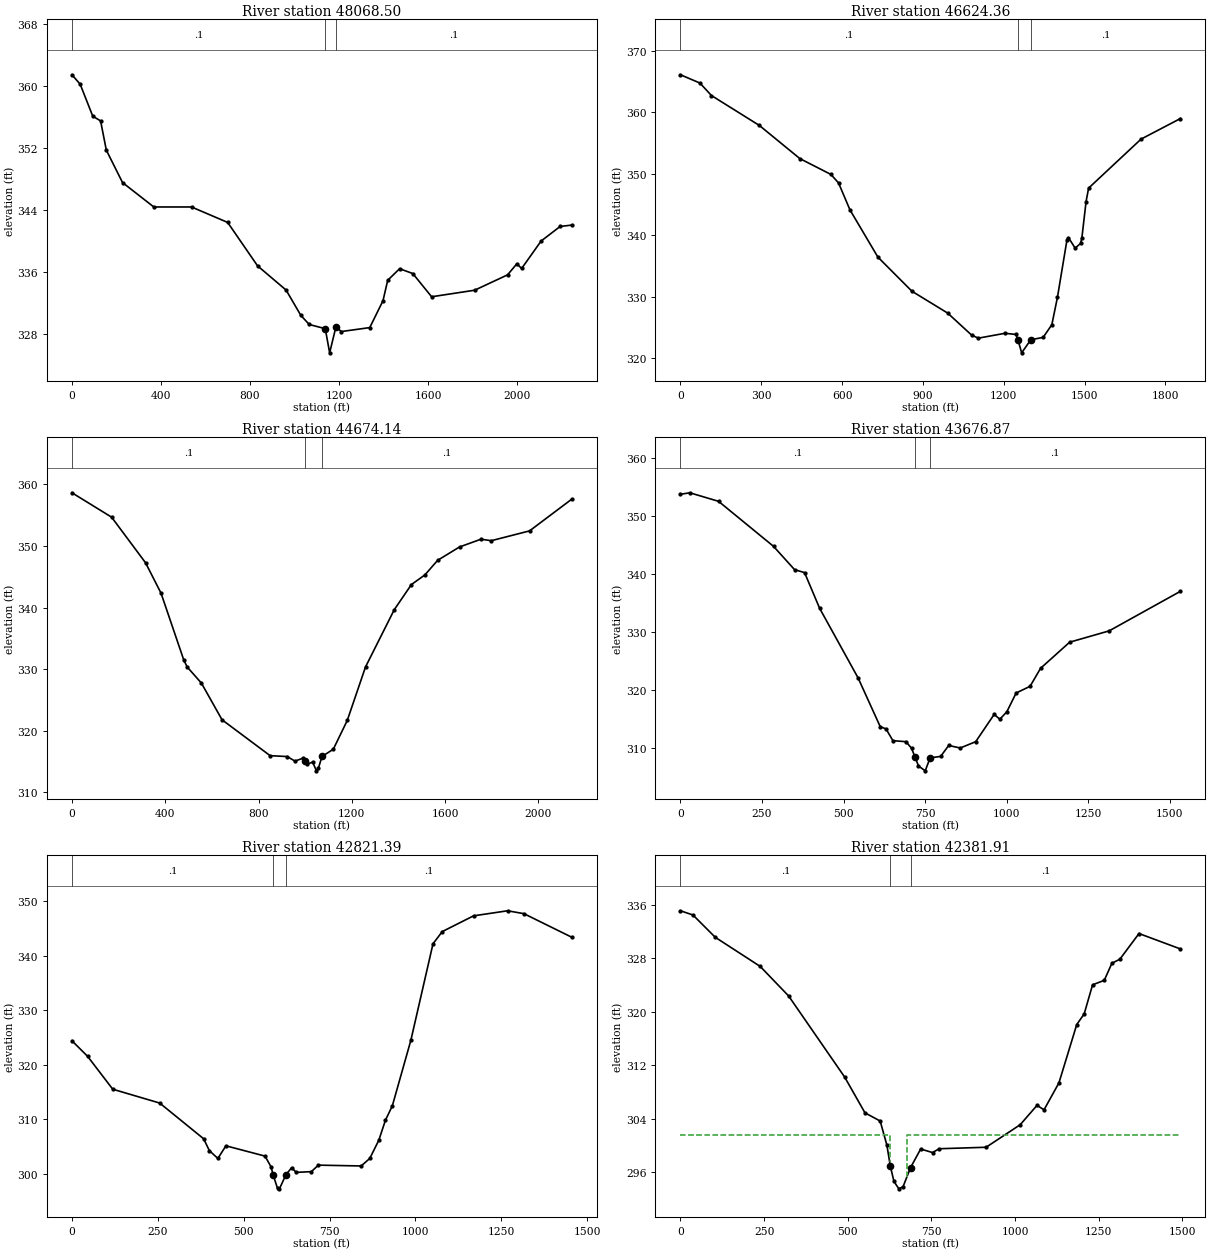
Type RM Length L Ch R = 1 ,48068.50,1430.05,1444.14,1363.2
XS GIS Cut Line= 3
 1613915.9362185  742147.1975907 1614106.8765669  740536.6572608
 1613952.6629976  739931.6200482
#Sta/Elev= 30
       0  361.41   36.95  360.19   93.35  356.08  128.59  355.47  154.38   351.7
  227.28  347.53  367.68  344.39   537.1  344.39  699.56   342.4   833.8  336.81
  962.09  333.69 1028.34  330.43 1066.06  329.26 1138.03  328.72 1157.75  325.61
 1186.01  328.96 1210.01  328.35 1337.96  328.86 1397.42  332.32 1418.56  334.95
 1472.06  336.44 1531.35  335.82 1615.94  332.83 1808.94  333.67 1957.14  335.65
  1998.9  337.08 2020.32  336.47 2107.71     340 2193.27  341.88  2246.2  342.06
#Mann= 3 , 0 , 0
       0      .1       0 1138.03    .045       0 1186.01      .1       0
Bank Sta=1138.03,1186.01
XS Rating Curve= 0 ,0
Exp/Cntr=0.3,0.1

Type RM Length L Ch R = 1 ,46624.36,1851.76,1950.22,1902.8
XS GIS Cut Line= 2
 1615434.9185343  740525.1360995 1613967.5089417  739389.4012779
#Sta/Elev= 30
       0  366.12   72.24  364.77  114.99  362.74  292.64  357.88  443.11  352.48
  558.19  349.91  586.69  348.52     629  344.14  732.77  336.45  859.14   330.9
  991.92  327.34 1080.68  323.76 1105.63  323.27 1204.36  324.06 1245.34  323.87
 1252.54     323 1266.32  320.88 1300.23  323.01 1345.99  323.39 1378.35  325.46
  1399.1  329.91 1434.51  339.26 1439.94  339.63 1464.89  337.91 1484.85  338.68
 1489.84  339.58 1505.32  345.47 1514.79  347.68 1709.39  355.65 1855.58     359
#Mann= 3 , 0 , 0
       0      .1       0 1252.54    .045       0 1300.23      .1       0
Bank Sta=1252.54,1300.23
XS Rating Curve= 0 ,0
Exp/Cntr=0.3,0.1

Type RM Length L Ch R = 1 ,44674.14,949.16,997.27,917.8
XS GIS Cut Line= 4
 1616354.2119452  739406.3162706 1615871.7759148  738783.1697313
 1615660.7101515  738441.4442097 1614746.0918438  738170.0739426
#Sta/Elev= 30
       0  358.64  169.94  354.68  315.37  347.28  381.77  342.35  479.39  331.49
  494.35  330.34  554.96  327.74  643.48  321.78  849.79  315.95  923.32  315.81
  955.92  315.07   992.2  315.56 1000.27  315.04 1007.44  314.56 1032.16  314.91
 1048.15  313.49 1056.84  313.93 1072.09  315.82 1120.62     317 1180.45  321.67
 1258.73  330.36  1382.1  339.66 1455.57  343.74  1513.3   345.3 1567.92  347.67
 1661.78  349.84 1753.74   351.1 1798.06  350.86 1962.09  352.45 2143.75  357.62
#Mann= 3 , 0 , 0
       0      .1       0 1000.27     .04       0 1072.09      .1       0
Bank Sta=1000.27,1072.09
XS Rating Curve= 0 ,0
Exp/Cntr=0.3,0.1

Type RM Length L Ch R = 1 ,43676.87,889.53,855.48,833.4
XS GIS Cut Line= 2
 1617005.0667525  738078.8871879 1615499.8981414  737789.1504936
#Sta/Elev= 30
       0  353.69   28.57  353.95  116.67  352.48  285.24  344.73  349.73  340.72
  380.42  340.21  426.48  334.08  544.56  322.08  612.26  313.71  630.19   313.3
  651.31  311.28  691.32  311.11  708.34  309.98  719.34  308.42  729.72  306.93
  750.37  306.09  765.36  308.33  797.57  308.57  822.39  310.46  857.66  310.02
  905.17  311.11  961.71   315.8  979.22  314.97 1000.61  316.26 1029.12  319.49
 1071.89  320.64 1103.91  323.73 1193.08  328.23 1314.26  330.18  1532.8  336.99
#Mann= 3 , 0 , 0
       0      .1       0  719.34     .04       0  765.36      .1       0
Bank Sta=719.34,765.36
XS Rating Curve= 0 ,0
Exp/Cntr=0.3,0.1

Type RM Length L Ch R = 1 ,42821.39,441.48,439.49,430.31
XS GIS Cut Line= 2
 1616619.9732446  736797.9168216   1615388.03831  737572.8012687
#Sta/Elev= 30
       0  324.38   45.58  321.52   118.7  315.49  255.32  312.95  383.32  306.39
  399.86  304.22  424.67  302.78  448.22   305.1  561.94  303.21  579.51  301.24
  585.93  299.71  598.33  297.29  603.99   297.2  623.14  299.83  639.68  301.09
  652.76  300.22  696.97  300.36  717.28  301.55  841.89   301.4  866.94  302.78
  893.23  306.12  912.58   309.8  932.67  312.45  986.59  324.48    1051  342.19
 1077.97  344.43 1169.09  347.32 1268.17  348.25 1315.65  347.72 1455.37  343.38
#Mann= 3 , 0 , 0
       0      .1       0  585.93    .045       0  623.14      .1       0
Bank Sta=585.93,623.14
XS Rating Curve= 0 ,0
Exp/Cntr=0.5,0.3

Type RM Length L Ch R = 1 ,42381.91,103.16,97.08,105.16
XS GIS Cut Line= 3
 1616304.7660119  736503.7234043 1615361.7710406  737136.7645968
 1615146.3794316  737423.0778332
#Sta/Elev= 30
       0  335.07   37.28  334.44   103.9  331.11  238.22  326.76  323.11  322.35
  490.79  310.22  551.33  304.89  596.73  303.67  616.91  300.05     627  296.95
  637.95  294.64  652.67  293.54  665.23  293.87  687.53  296.71   717.8  299.49
  753.14  298.96  773.29  299.53  913.28  299.75 1015.06  303.11 1065.56  306.01
 1086.43  305.34 1131.01  309.37 1184.25  318.08 1206.48  319.67 1231.47  324.01
 1266.46  324.68 1289.36  327.24 1312.98  327.83 1370.26  331.67 1494.06  329.37
#Mann= 3 , 0 , 0
       0      .1       0     627     .04       0  687.53      .1       0
#XS Ineff= 2 , 0
          625.22  301.51  676.38          301.51
Permanent Ineff=
       F       F
Bank Sta=627,687.53
XS Rating Curve= 0 ,0
Exp/Cntr=0.5,0.3