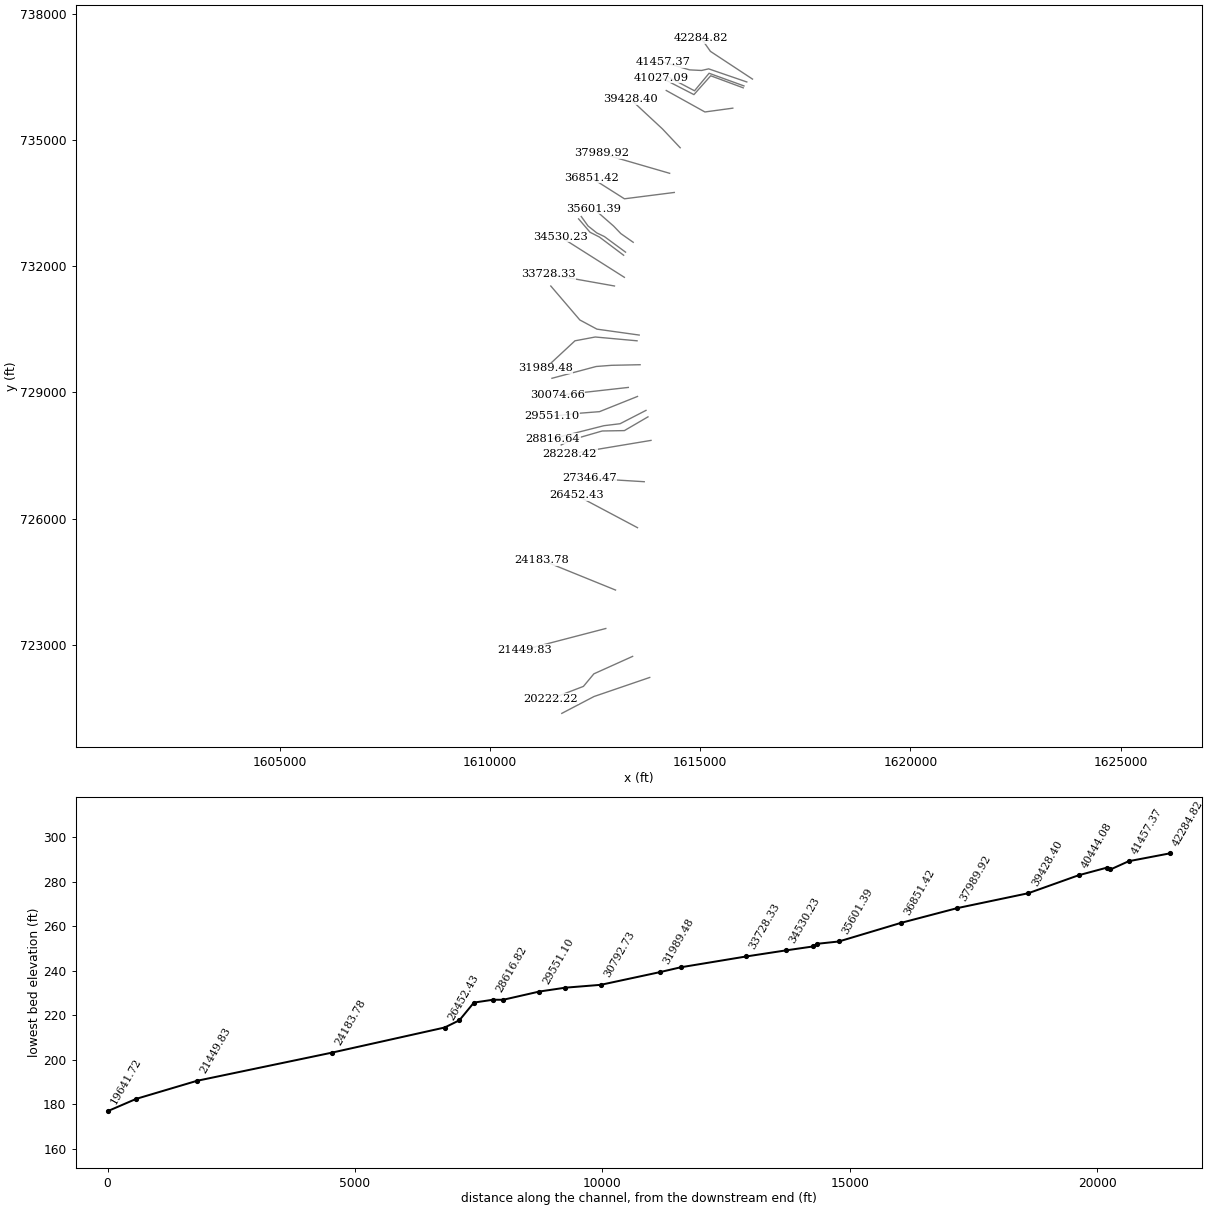
HEC-RAS study LittleNortheast.prj: Little Northeast Creek

--- LittleNortheast.g03 (geometry) --- (continued)

Type RM Length L Ch R = 3 ,42341.09,,,
BEGIN DESCRIPTION:
Hw 545 Blue Ball Rd
END DESCRIPTION:
Bridge Culvert--1,0,-1,-1, 0
Deck Dist Width WeirC Skew NumUp NumDn MinLoCord MaxHiCord MaxSubmerge Is_Ogee
35,30,2.6,0, 60, 60, , , 0.95, 0, 0,0,,
       0   31.54   36.58   56.76   87.02   98.07  107.19  114.68  131.81  175.82
  183.45  195.32  266.81   296.3  351.18  364.41  371.53  389.63   412.5  450.15
  464.09  488.74  519.93  528.36  559.61  570.55  584.69  593.06  639.42  639.42
  664.42  664.42  697.53  713.98  717.45  722.61  729.72  735.15  756.17   757.8
  789.25  808.62  826.73  864.59  911.22  925.64  946.82 1012.12 1047.73 1053.58
 1107.94 1168.79 1212.66 1361.93 1409.66 1423.39 1438.55 1446.97 1455.35 1490.46
  334.14     333  332.55     332  330.61   330.4  329.98  329.31  329.03  327.05
  326.97  326.23  323.18  321.59  318.12  316.72  316.54  314.83  313.55  310.77
  310.17  308.17  307.26   306.7  306.03  306.21  305.92  304.79     305     307
     307   304.5  304.18  303.38  302.93  302.94  302.35  302.61  302.72  302.49
  302.02  301.47  301.89  301.68  302.17  301.96  302.59  303.57  304.89  304.89
  307.28  311.17   312.8  320.75  322.71  322.95  323.77   323.7  324.25  325.01
                                                                                
                                                                                
                                                                           303.5
   303.5
                                                                                
                                                                                
       0   31.54   36.58   56.76   87.02   98.07  107.19  114.68  131.81  175.82
  183.45  195.32  266.81   296.3  351.18  364.41  371.53  389.63   412.5  450.15
  464.09  488.74  519.93  528.36  559.61  570.55  584.69  593.06  675.84  675.84
  700.84  700.84   757.8  789.25  808.62  813.38  826.73  864.59  911.22  925.64
  946.82 1012.12 1047.73 1053.58 1107.94 1168.79 1212.66 1288.65  1299.3 1308.64
 1318.03 1335.59 1361.93 1398.58 1409.66 1423.39 1438.55 1446.97 1455.35 1490.46
  334.14     333  332.55     332  330.61   330.4  329.98  329.31  329.03  327.05
  326.97  326.23  323.18  321.59  318.12  316.72  316.54  314.83  313.55  310.77
  310.17  308.17  307.26   306.7  306.03  306.21  305.92  304.79     305     307
     307     305  302.49  302.02  301.47  301.74  301.89  301.68  302.17  301.96
  302.59  303.57  304.89  304.89  307.28  311.17   312.8  316.74  317.48  317.77
  318.51  319.19  320.75   322.1  322.71  322.95  323.77   323.7  324.25  325.01
                                                                                
                                                                                
                                                                           303.5
   303.5
                                                                                
                                                                                
BR Coef=-1 , 0 , 0 ,, 0 ,,,0.8,0,,0,
WSPro=,,,, 1 ,,,, 0 ,,,, 0 ,,,,-1 ,-1 ,-1 , 0 , 0 , 0 , 0 , 0
BC Design=,, 0 ,, 0 ,,,,,,
BC Use User HTab Curves=0
BC User HTab FreeFlow(D)= 0

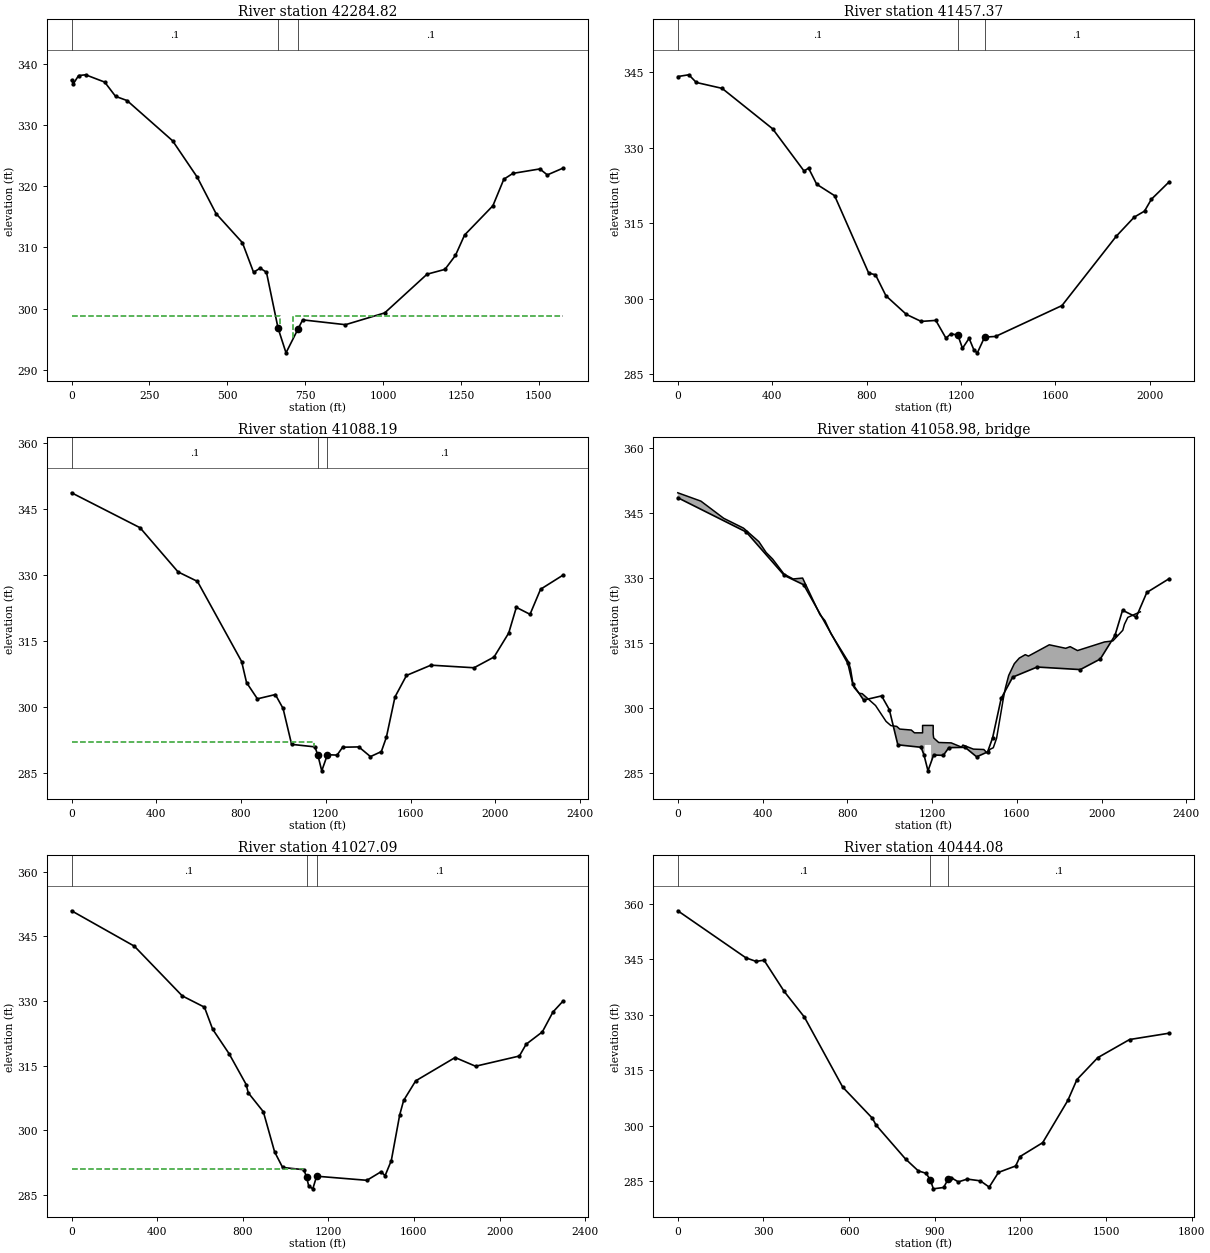
Type RM Length L Ch R = 1 ,42284.82,739.48,827.45,823.1
XS GIS Cut Line= 3
 1616244.3512923  736453.8155925 1615243.5683284  737113.1240543
 1615025.5499924  737423.0778332
#Sta/Elev= 30
       0  337.39    5.81  336.81   22.57  338.15   45.02  338.28   106.4  337.08
  141.21  334.75  178.08  334.06  324.34  327.47  403.21  321.52  463.85  315.54
  548.38  310.78   584.2  305.93  605.35  306.61  625.56  305.94  662.89  296.77
  688.34  292.74  726.71  296.63  741.79  298.14   879.2  297.35  1005.1  299.28
 1141.01  305.62 1198.44  306.41 1232.09  308.69 1261.54  312.04 1352.35  316.83
 1387.52  321.18 1416.62  322.13 1503.08  322.86    1527  321.88 1577.39  322.99
#Mann= 3 , 0 , 0
       0      .1       0  662.89     .04       0  726.71      .1       0
#XS Ineff= 2 , 0
          668.81  298.84  711.59          298.84
Permanent Ineff=
       F       F
Bank Sta=662.89,726.71
XS Rating Curve= 0 ,0
Exp/Cntr=0.5,0.3

Type RM Length L Ch R = 1 ,41457.37,287.35,369.18,386.67
XS GIS Cut Line= 5
 1616108.6370671  736385.5206921 1615201.5406973  736697.2256222
 1615033.4301732  736658.7002938 1614749.7436638  736672.7095041
 1614108.8222905  736858.3315412
#Sta/Elev= 30
       0  344.17   46.67  344.52   78.57  342.99   187.8  341.82  401.95  333.78
  535.19  325.38  554.16  325.97  588.77  322.75   664.6  320.48  809.05  305.09
  837.95  304.75  882.28  300.57  968.89  296.87 1031.58  295.48  1093.6  295.68
 1136.56  292.15 1157.59  293.03 1187.15  292.73 1206.65  290.13 1234.68  292.12
  1255.4  289.76 1269.72  289.23 1300.28  292.35 1346.82  292.49  1628.3  298.63
 1858.67  312.43 1934.38  316.21  1978.1  317.41 2007.25  319.77 2082.92  323.25
#Mann= 3 , 0 , 0
       0      .1       0 1187.15     .04       0 1300.28      .1       0
Bank Sta=1187.15,1300.28
XS Rating Curve= 0 ,0
Exp/Cntr=0.5,0.3

Type RM Length L Ch R = 1 ,41088.19,63.04,61.1,62.16
XS GIS Cut Line= 4
 1616042.0933179  736290.9585223 1615212.0476051  736592.1565446
 1614865.3196491  736175.3825369 1614073.7992647  736592.1565446
#Sta/Elev= 30
       0  348.61  323.26  340.68  502.81  330.65  594.23   328.5  802.74  310.32
  825.94  305.54   877.2  301.85  961.97  302.82  998.33  299.67 1038.66  291.52
 1148.44  290.95 1162.23  289.15 1180.94  285.51 1207.76  289.17 1253.29  289.08
 1279.45  290.87 1356.07  290.94 1410.79  288.74 1462.24  289.88 1485.97  293.13
 1526.53  302.27 1580.91  307.16  1696.3  309.49 1899.66   308.9 1994.18  311.34
 2063.48  316.79 2099.35  322.61 2163.96  321.03 2213.79  326.72 2319.69  329.92
#Mann= 3 , 0 , 0
       0      .1       0 1162.23     .04       0 1207.76      .1       0
#XS Ineff= 2 , 0
         1145.65  292.11
Permanent Ineff=
       F       F
Bank Sta=1162.23,1207.76
XS Rating Curve= 0 ,0
Exp/Cntr=0.5,0.3

Type RM Length L Ch R = 3 ,41058.98,,,
BEGIN DESCRIPTION:
Wheatley Rd
END DESCRIPTION:
Bridge Culvert--1,0,-1,-1, 0
Deck Dist Width WeirC Skew NumUp NumDn MinLoCord MaxHiCord MaxSubmerge Is_Ogee
30,22,2.6,0, 60, 60, , , 0.95, 0, 0,0,,
       0  109.18  216.54  310.23   382.7  417.07  447.56  501.43  544.45  589.16
  671.14  694.62  723.31  805.28  815.53  826.45  831.91  855.54  870.76  933.44
   983.1 1005.87 1033.41 1047.67 1101.96 1117.19 1155.44 1155.44 1165.44 1195.44
 1205.44 1205.44 1207.85 1231.42 1290.48 1338.86 1345.73 1395.31 1444.43 1461.72
 1473.68 1489.22 1504.76 1536.87 1546.34 1561.92 1588.51 1611.62  1640.2 1655.02
 1753.46 1831.01  1851.9 1886.66  2014.3 2053.34 2100.35 2108.26 2124.09 2183.34
  349.75  347.82  343.86  341.58  338.46  335.95  334.45  330.97  329.84  330.05
  321.58  320.22  317.18  310.71  309.04  305.77  304.76  303.44  303.33   300.6
  296.93  295.96  295.78  295.16  294.94  294.29  294.29     296     296     296
     296     294  293.11  292.06  291.97     291  291.47  290.53  290.44  289.55
  290.48  290.85  293.04  302.29  304.64  307.56  310.27  311.55  312.35  312.02
  314.63  313.82   314.2   313.3  315.29  315.52  317.98  319.36  320.96  322.25
                                                                                
                                                                                
                                                                   291.5   291.5
                                                                                
                                                                                
                                                                                
       0  109.18  216.54  310.23   382.7  417.07  447.56  501.43  544.45  589.16
  671.14  694.62  723.31  805.28  815.53  826.45  831.91  855.54  870.76  933.44
   967.1   983.1 1005.87 1092.65 1092.65 1102.65 1132.65 1142.65 1142.65 1183.46
 1231.42 1290.48 1315.85  1324.1 1338.86 1345.73 1395.31 1444.43 1461.72 1473.68
 1489.22 1504.76 1536.87 1546.34 1561.92 1588.51 1611.62  1640.2 1655.02 1753.46
 1831.01  1851.9 1886.66 1989.55  2014.3 2053.34 2100.35 2108.26 2124.09 2183.34
  349.75  347.82  343.86  341.58  338.46  335.95  334.45  330.97  329.84  330.05
  321.58  320.22  317.18  310.71  309.04  305.77  304.76  303.44  303.33   300.6
  298.39  296.93  295.96  294.77     296     296     296     296  294.13  294.23
  292.06  291.97  291.37  291.58     291  291.47  290.53  290.44  289.55  290.48
  290.85  293.04  302.29  304.64  307.56  310.27  311.55  312.35  312.02  314.63
  313.82   314.2   313.3  314.58  315.29  315.52  317.98  319.36  320.96  322.25
                                                                                
                                                                                
                                           291.5   291.5
                                                                                
                                                                                
                                                                                
BR Coef=-1 , 0 , 0 ,, 0 ,,,0.8,0,,0,
WSPro=,,,, 1 ,,,, 0 ,,,, 0 ,,,,-1 ,-1 ,-1 , 0 , 0 , 0 , 0 , 0
BC Design=,, 0 ,, 0 ,,,,,,
BC Use User HTab Curves=0
BC User HTab FreeFlow(D)= 0

Type RM Length L Ch R = 1 ,41027.09,637.84,583.01,550.96
XS GIS Cut Line= 4
  1616024.581805  736245.4285887 1615250.5729335  736532.6174007
 1614851.3104387  736084.3226697 1614077.3015672  736483.5851645
#Sta/Elev= 30
       0  350.92  293.41  342.71   517.4  331.17  621.13  328.55  659.26  323.45
  736.07  317.77  816.05  310.61  825.57   308.7  896.35  304.29  948.97  294.98
  986.42  291.36  1085.8  290.84 1098.91  289.05 1108.28  287.06 1127.44   286.4
 1145.42  289.33  1380.3  288.38 1447.05  290.38 1465.22  289.44 1494.31  292.95
 1533.69  303.58 1551.92   306.9 1608.38  311.46 1792.57  316.87 1888.13  314.85
 2092.92  317.22 2124.43  319.95  2200.1  322.81 2249.83  327.43 2296.81  329.96
#Mann= 3 , 0 , 0
       0      .1       0 1098.91     .04       0 1145.42      .1       0
#XS Ineff= 2 , 0
         1080.25  290.91
Permanent Ineff=
       F       F
Bank Sta=1098.91,1145.42
XS Rating Curve= 0 ,0
Exp/Cntr=0.5,0.3

Type RM Length L Ch R = 1 ,40444.08,1023.99,1015.68,1008.81
XS GIS Cut Line= 3
 1615775.9183214  735762.1108318 1615112.5462259  735671.6624992
 1614192.8775526  736182.3871421
#Sta/Elev= 30
       0  358.15  238.61  345.42  273.93  344.46  302.19  344.77  372.84  336.31
  443.48  329.38  577.71  310.43  681.53  302.02  694.43  300.17  797.67  290.99
  842.32  287.78  869.74  287.11  884.91  285.31   895.2  282.91  931.24  283.28
  946.68   285.5  957.81  285.93  982.72  284.79 1013.86  285.55 1059.94  285.07
 1090.83  283.38 1123.38  287.36  1183.5   289.1 1198.94  291.65 1278.09   295.4
 1366.17  306.82  1398.2  312.48 1471.19  318.41 1582.52  323.31 1721.47  325.03
#Mann= 3 , 0 , 0
       0      .1       0  884.91    .045       0  946.68      .1       0
Bank Sta=884.91,946.68
XS Rating Curve= 0 ,0
Exp/Cntr=0.3,0.1

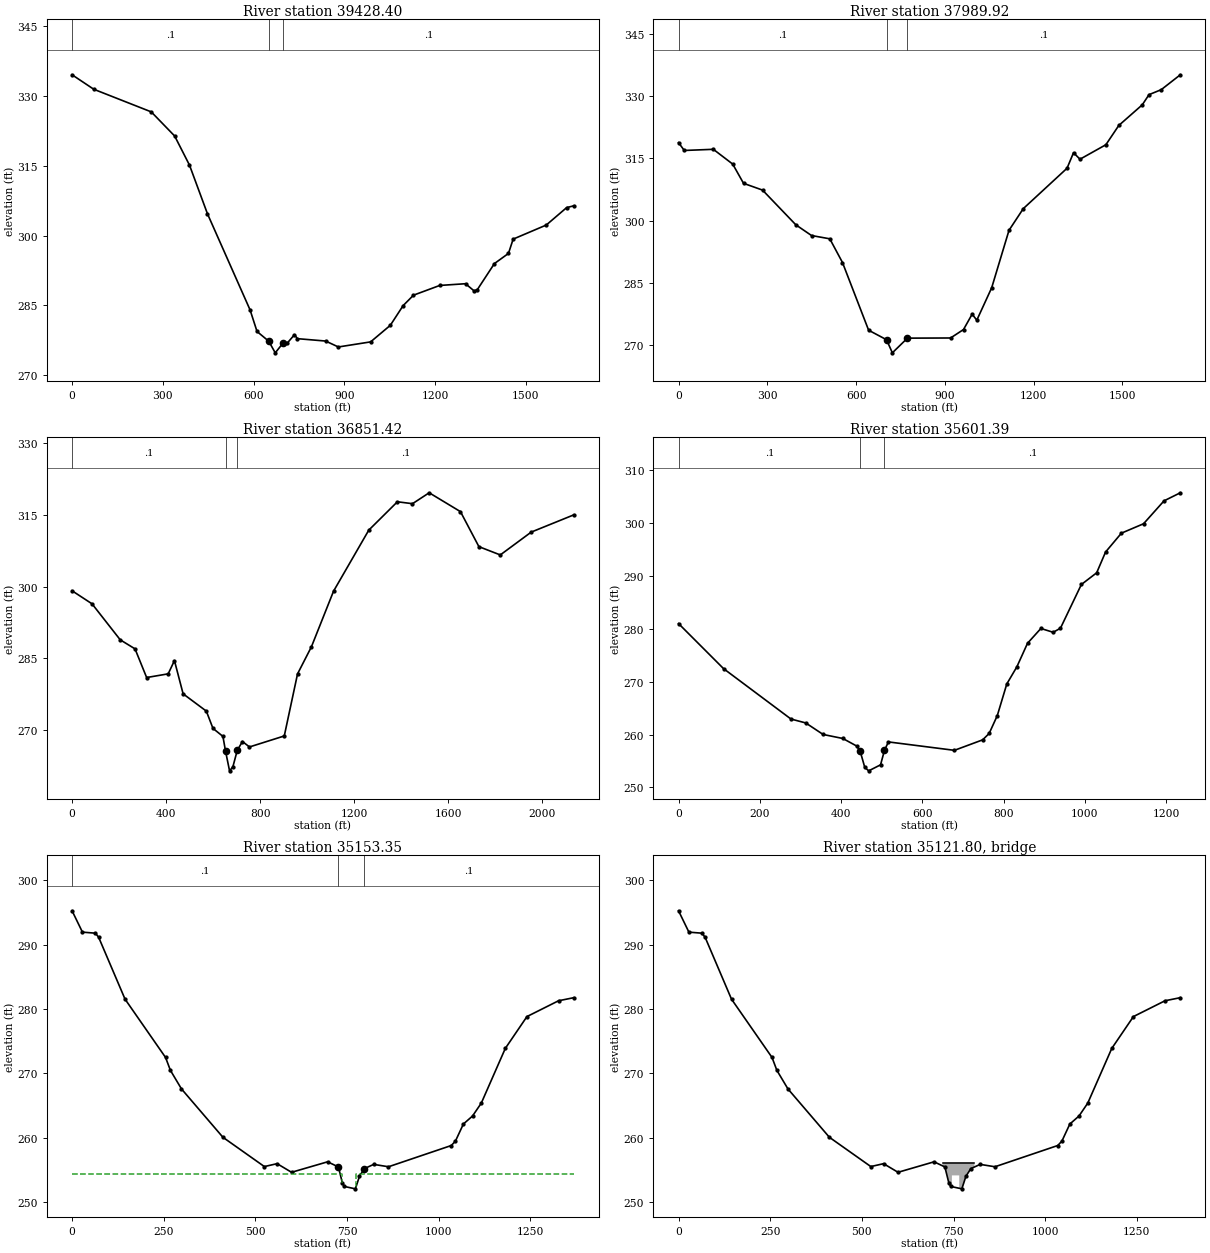
Type RM Length L Ch R = 1 ,39428.40,1240.9,1438.48,1293.09
XS GIS Cut Line= 3
 1614524.5679085  734819.9787092 1614103.4983865  735267.3650763
 1613338.0120658   735978.720817
#Sta/Elev= 30
       0   334.5   71.87  331.39  261.88  326.54  339.28  321.36  388.21  315.13
  447.81  304.66  588.71  284.04  611.64  279.42  650.35  277.34  671.86  274.84
  699.01  277.04   710.7  276.86  735.46  278.73  745.37  277.88  838.51  277.37
  880.57   276.1  987.26  277.19 1052.34  280.74 1094.91  284.98 1129.02  287.21
 1215.91   289.3 1301.03  289.67  1329.7  288.12 1340.26  288.41 1396.59  293.99
 1443.09  296.17 1458.61  299.24  1568.1  302.26 1635.49     306 1659.36  306.39
#Mann= 3 , 0 , 0
       0      .1       0  650.35    .045       0  699.01      .1       0
Bank Sta=650.35,699.01
XS Rating Curve= 0 ,0
Exp/Cntr=0.3,0.1

Type RM Length L Ch R = 1 ,37989.92,918.79,1138.49,1055.22
XS GIS Cut Line= 2
  1614273.430512  734212.3419375 1612644.8598096  734685.1527866
#Sta/Elev= 30
       0  318.79   19.44   316.9  117.59  317.18  183.19  313.61  219.64  308.98
  283.91  307.35  396.46  298.98  449.47   296.4   511.2  295.61  554.06   289.9
   642.4  273.58  702.97  271.29  722.58  268.13  773.61  271.67  919.39  271.71
  963.12  273.75  992.28  277.45 1008.02     276 1058.26   283.8 1116.83  297.66
 1165.09  302.88    1313  312.62 1334.86  316.36 1356.73  314.79  1444.2  318.28
 1487.93  322.93 1567.27   327.9 1589.98  330.35 1631.27  331.55 1695.82  335.14
#Mann= 3 , 0 , 0
       0      .1       0  702.97    .045       0  773.61      .1       0
Bank Sta=702.97,773.61
XS Rating Curve= 0 ,0
Exp/Cntr=0.3,0.1

Type RM Length L Ch R = 1 ,36851.42,1235.49,1250.03,1153.64
XS GIS Cut Line= 3
  1614384.264821  733756.7893393 1613198.2762462  733606.0280798
 1612404.2669461  734108.5656115
#Sta/Elev= 30
       0  299.11   85.01  296.38  204.96  288.86   267.9  286.97   317.3  280.98
  409.03  281.75   435.6  284.52  472.54  277.57  571.33  273.96  599.55  270.35
  641.89  268.68  653.01  265.61  670.11  261.48  684.23  262.31  702.91  265.76
  724.99  267.61  754.89  266.47  902.97  268.77  959.42  281.74 1018.47   287.4
 1112.66  299.03 1262.54  311.78 1384.32  317.71 1448.53  317.31 1519.62  319.59
 1652.66  315.65  1731.2  308.33 1822.16   306.6 1953.71  311.37 2135.21  314.98
#Mann= 3 , 0 , 0
       0      .1       0  653.01    .045       0  702.91      .1       0
Bank Sta=653.01,702.91
XS Rating Curve= 0 ,0
Exp/Cntr=0.3,0.1

Type RM Length L Ch R = 1 ,35601.39,416.3,448.05,453.15
XS GIS Cut Line= 4
 1613406.9608523   732571.513176  1613112.767435  732778.1490286
 1612941.1546083  732956.7664604 1612468.3437592  733370.0381656
#Sta/Elev= 30
       0  281.01  110.87  272.48  276.74  262.95  313.15  262.21  355.92  260.03
  404.46  259.27  439.04  257.82  447.08  256.87  458.46   253.8  468.17  253.15
  497.29  254.29  506.99  257.06   516.7  258.62  679.06  257.03  748.52  259.01
  764.59  260.22  784.59  263.59  808.05  269.59  832.85  272.83  859.04  277.28
  891.93  280.08  922.15  279.36  940.12  280.13   991.6   288.4 1029.23  290.61
 1051.13  294.54 1090.14  298.11 1144.66  299.89    1195  304.22 1235.18  305.75
#Mann= 3 , 0 , 0
       0      .1       0  447.08    .045       0  506.99      .1       0
Bank Sta=447.08,506.99
XS Rating Curve= 0 ,0
Exp/Cntr=0.5,0.3

Type RM Length L Ch R = 1 ,35153.35,77.38,71.12,68.56
XS GIS Cut Line= 5
 1613224.8411178  732336.8589027 1612720.5095454  732708.1029768
  1612538.389811  732795.6605415 1612331.7539584   732960.268763
 1612170.6480394  733184.4161285
#Sta/Elev= 30
       0  295.28   28.28  291.96   63.75   291.8   72.44  291.17  144.46  281.55
  254.98  272.49   268.2  270.49  298.44   267.6  411.43  260.09  524.43  255.54
   559.2  255.99  598.63  254.65  696.98  256.28  726.39  255.48   737.2     253
  742.55  252.45  772.68  252.08  783.81  254.03  797.17  255.22  822.64  255.88
  862.99  255.51 1034.18  258.81 1045.52  259.49 1067.22  262.15 1092.13  263.39
 1116.11   265.4  1181.6   273.9 1240.56  278.84 1326.77   281.3 1368.54  281.78
#Mann= 3 , 0 , 0
       0      .1       0  726.39     .04       0  797.17      .1       0
#XS Ineff= 2 , 0
           737.3  254.39   774.6          254.33
Permanent Ineff=
       F       F
Bank Sta=726.39,797.17
XS Rating Curve= 0 ,0
Exp/Cntr=0.5,0.3

Type RM Length L Ch R = 3 ,35121.80,,,
BEGIN DESCRIPTION:
Unamed Road
END DESCRIPTION:
Bridge Culvert--1,0,-1,-1, 0
Deck Dist Width WeirC Skew NumUp NumDn MinLoCord MaxHiCord MaxSubmerge Is_Ogee
15,15,2.6,0, 6, 6, , , 0.95, 0, 0,0,,
     720  745.56  745.56  765.56  765.56     807
  256.17  256.17  256.17  256.17  256.17  256.17
                  254.17  254.17
     756  789.51  789.51  809.51  809.51     840
  256.17  256.17  256.17  256.17  256.17  256.17
                  254.17  254.17
BR Coef=-1 , 0 , 0 ,, 0 ,,,0.8,0,,0,
WSPro=,,,, 1 ,,,, 0 ,,,, 0 ,,,,-1 ,-1 ,-1 , 0 , 0 , 0 , 0 , 0
BC Design=,, 0 ,, 0 ,,,,,,
BC Use User HTab Curves=0
BC User HTab FreeFlow(D)= 0

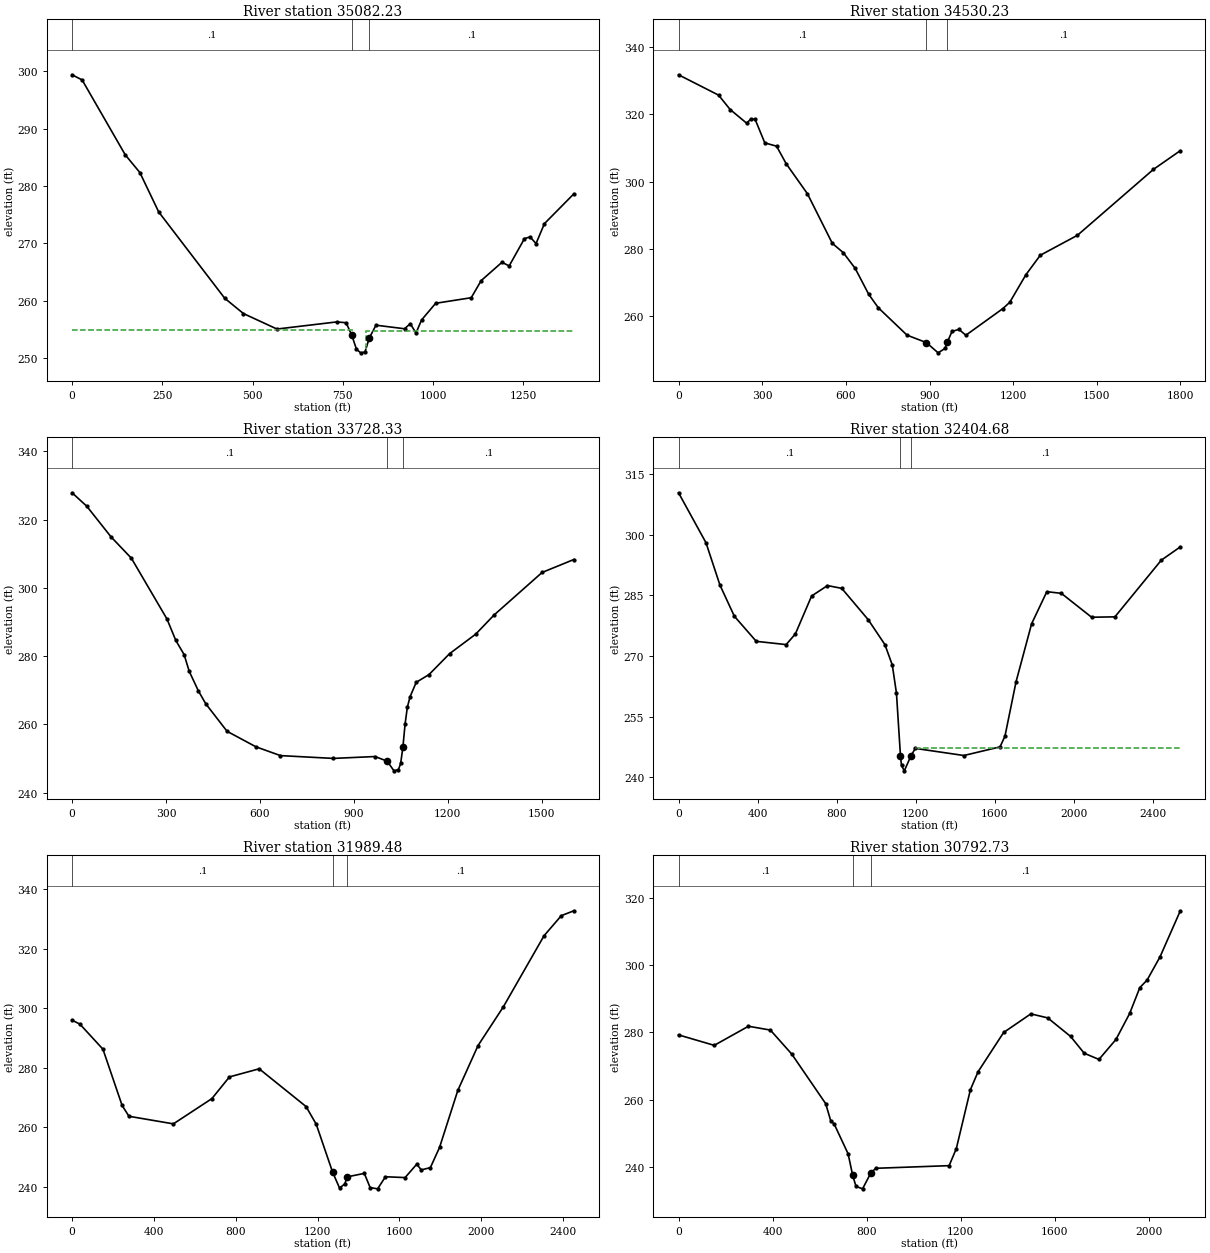
Type RM Length L Ch R = 1 ,35082.23,546.27,551.99,546.21
XS GIS Cut Line= 4
 1613179.3111842  732263.3105484 1612601.4312575  732697.5960691
 1612380.7861946  732809.6697518 1612107.6065929  733128.3792872
#Sta/Elev= 30
       0   299.4   27.85   298.5  147.37  285.44  187.83  282.35  239.96  275.49
   422.8  260.44   474.7  257.77  567.68  255.07  733.06  256.31   759.2  256.17
  774.82     254  787.85  251.56  799.51  250.92  811.41  251.05  823.23  253.48
   841.9  255.74  921.01  255.12  937.03     256  952.73  254.38  968.43  256.67
 1007.31  259.56 1105.79  260.53 1133.45  263.52    1191  266.71 1210.85  266.07
  1253.3  270.84 1268.89  271.13 1285.32  269.97 1308.62  273.45 1390.12  278.64
#Mann= 3 , 0 , 0
       0      .1       0  774.82     .04       0  823.23      .1       0
#XS Ineff= 2 , 0
          778.33  254.83  814.39          254.71
Permanent Ineff=
       F       F
Bank Sta=774.82,823.23
XS Rating Curve= 0 ,0
Exp/Cntr=0.5,0.3

Type RM Length L Ch R = 1 ,34530.23,736.63,801.91,806.63
XS GIS Cut Line= 2
 1613196.8226972  731737.9651605 1611676.8233748  732701.0983717
#Sta/Elev= 30
       0  331.78  143.63  325.73  185.06  321.46  244.11   317.4  259.65  318.65
  274.55  318.55  309.37  311.54  351.54  310.56  386.15  305.33  462.24  296.42
  551.59  281.67  591.12  278.89  633.32  274.26  682.28   266.5  716.57  262.52
  819.54  254.39  888.76  252.19  930.89  249.14  955.75  250.45  964.15  252.35
  980.61   255.5 1005.47  256.11 1030.33  254.37 1162.92  262.28 1187.78  264.16
 1245.79  272.37 1297.21  278.14 1430.57  284.08 1703.13  303.67 1799.45  309.23
#Mann= 3 , 0 , 0
       0      .1       0  888.76    .045       0  964.15      .1       0
Bank Sta=888.76,964.15
XS Rating Curve= 0 ,0
Exp/Cntr=0.3,0.1

Type RM Length L Ch R = 1 ,33728.33,1314.42,1323.64,1278.25
XS GIS Cut Line= 2
 1612960.9565228  731531.8553086 1611382.7328856  731812.4283997
#Sta/Elev= 30
       0  327.84   46.71  323.93  124.53  314.92  189.38  308.69  303.14  290.88
  331.39   284.6     358  280.44  374.23  275.56  403.68  269.79  427.18  266.04
   495.1  257.99  587.53  253.44  665.73  250.87   834.5  250.05  967.77   250.6
 1006.53  249.25 1028.33  246.41 1042.55  246.77 1049.66  248.56 1056.77  253.29
 1063.88  260.16 1070.99  265.01 1079.77  268.12 1099.43  272.34 1140.14  274.59
 1206.07  280.73 1289.15  286.42 1348.27  292.06  1501.4   304.5 1602.97   308.3
#Mann= 3 , 0 , 0
       0      .1       0 1006.53    .045       0 1056.77      .1       0
Bank Sta=1006.53,1056.77
XS Rating Curve= 0 ,0
Exp/Cntr=0.3,0.1

Type RM Length L Ch R = 1 ,32404.68,382.39,415.2,432.86
XS GIS Cut Line= 4
 1613549.0474433  730364.6610004 1612543.9723799  730505.3715093
 1612137.4929083  730723.4648448 1611446.3718647  731531.3293079
#Sta/Elev= 30
       0  310.46  138.89  298.08  209.57  287.58  282.44  279.86  393.35  273.64
  544.65  272.83  591.26  275.48  673.51  284.88  753.83  287.46  825.97  286.77
  959.32  279.04 1044.25  272.84 1081.79  267.76  1102.8  260.79 1123.15  245.23
 1128.32  242.89 1142.52  241.54 1175.96  245.24 1198.12   247.1 1443.97  245.34
 1626.91  247.48 1651.79  250.12 1708.11  263.64 1786.79     278 1863.81  285.95
 1937.34  285.53  2090.4  279.61 2208.39  279.71 2442.89  293.75 2539.32  297.05
#Mann= 3 , 0 , 0
       0      .1       0 1123.15    .045       0 1175.96      .1       0
#XS Ineff= 2 , 0
                         1198.93          247.23
Permanent Ineff=
       F       F
Bank Sta=1123.15,1175.96
XS Rating Curve= 0 ,0
Exp/Cntr=0.3,0.1

Type RM Length L Ch R = 1 ,31989.48,1172.82,1196.75,1095.34
XS GIS Cut Line= 4
 1613498.7936902  730227.9707918 1612503.7693774  730318.4275475
  1612021.333347  730227.9707918 1611315.6192348  729572.3747282
#Sta/Elev= 30
       0  296.04   38.45  294.69  150.91  286.29  244.68  267.39  278.08  263.76
  495.33  261.21  683.55  269.69  769.45  276.98  914.76   279.7 1143.88  267.03
 1193.73  261.08 1273.71     245 1307.68  239.66 1333.44  241.05 1344.85  243.41
 1428.75  244.58 1457.24  239.81 1493.84  239.39 1532.05  243.45 1628.16  243.17
 1684.93  247.66 1707.41  245.75 1751.81  246.52 1796.57   253.3 1885.89  272.44
 1984.79  287.51 2108.61  300.53 2307.57   324.4 2391.95  331.13 2453.21  332.77
#Mann= 3 , 0 , 0
       0      .1       0 1273.71    .045       0 1344.85      .1       0
Bank Sta=1273.71,1344.85
XS Rating Curve= 0 ,0
Exp/Cntr=0.3,0.1

Type RM Length L Ch R = 1 ,30792.73,724.91,718.07,672.85
XS GIS Cut Line= 4
 1613571.2029959  729659.0299258 1612890.8132501  729645.0012712
 1612526.0682317  729616.9439621 1611473.9191402  729336.3708711
#Sta/Elev= 30
       0  279.29  151.93  276.19  297.47  281.85  390.79  280.72  481.81   273.6
  626.22  258.91  647.66  253.83  661.96  252.93  721.62  244.04  741.03  237.68
  755.07  234.41  783.15  233.67  818.25  238.38  839.32  239.76 1151.47  240.54
    1182  245.58 1242.02  263.06 1274.63  268.37  1383.3     280 1499.22  285.52
 1570.92  284.33 1668.15  278.84 1726.35  273.85    1789  272.02 1861.45  277.94
 1919.81  285.66 1962.87  293.29 1994.16  295.57 2048.68  302.39 2135.27  316.07
#Mann= 3 , 0 , 0
       0      .1       0  741.03    .045       0  818.25      .1       0
Bank Sta=741.03,818.25
XS Rating Curve= 0 ,0
Exp/Cntr=0.3,0.1

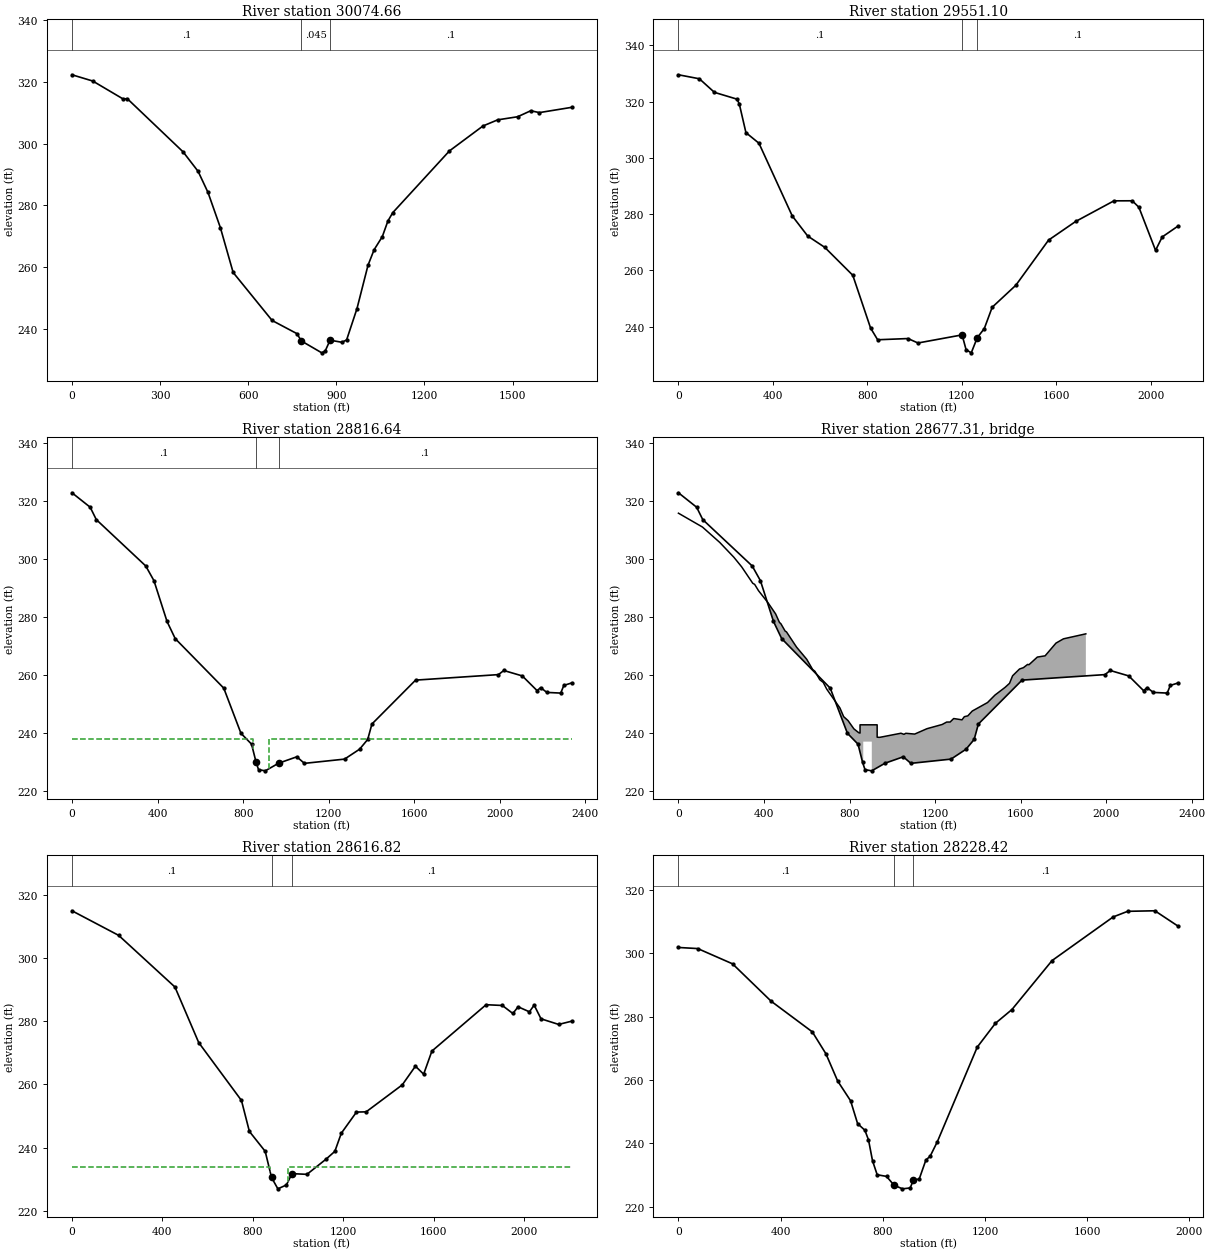
Type RM Length L Ch R = 1 ,30074.66,520.83,523.56,520.59
XS GIS Cut Line= 2
 1613290.6299048  729118.9267255 1611600.1770312   728929.539889
#Sta/Elev= 30
       0  322.21   70.75  320.19  174.21  314.39   188.3  314.49  378.48  297.29
  429.42  291.01  463.01  284.22  505.27  272.81  548.71  258.34  681.37  242.83
  765.49   238.6  781.27   236.2  850.42  232.38  862.04  232.96  878.59  236.47
   918.9  235.79  934.94  236.55  970.16  246.64  1007.8  260.68 1028.62   265.7
  1056.5  269.92  1075.5  274.97 1092.08  277.67 1284.94  297.61 1399.15  305.67
 1449.22  307.65 1517.07  308.65 1561.84  310.59 1591.18  309.99 1701.03  311.69
#Mann= 3 , 0 , 0
       0      .1       0  781.27    .045       0  878.59      .1       0
Bank Sta=781.27,878.59
XS Rating Curve= 0 ,0
Exp/Cntr=0.3,0.1

Type RM Length L Ch R = 1 ,29551.10,731.31,734.45,472.9
XS GIS Cut Line= 4
 1613508.8444408  728904.2869333 1612604.2768837  728542.4599105
 1612091.6886014  728502.2569079 1611468.5420621  728431.9016535
#Sta/Elev= 30
       0  329.51   88.62  328.09  152.42  323.26  248.09  320.84  257.69  319.14
  285.78  308.94  340.91  305.17   481.8  279.34  547.26  272.18  619.51  268.16
  738.14  258.23  813.53  239.46  843.37   235.3  971.85  235.73 1014.15  234.15
 1200.98  237.03 1217.77  231.78 1239.74  230.65 1265.08  236.02 1295.01  239.29
 1328.38  246.86 1428.42  254.67 1567.03  270.73 1681.82  277.36 1843.84  284.69
 1921.42  284.71 1949.51   282.4 2019.96  267.09 2048.13  271.85 2115.52  275.74
#Mann= 3 , 0 , 0
       0      .1       0 1200.98    .044       0 1265.08      .1       0
Bank Sta=1200.98,1265.08
XS Rating Curve= 0 ,0
Exp/Cntr=0.5,0.3

Type RM Length L Ch R = 1 ,28816.64,173.64,199.82,455.53
XS GIS Cut Line= 4
 1613711.1942035   728573.051057 1613094.7889485  728255.5089559
 1612711.8705324  728208.8115881 1611493.0692325  727900.6089605
#Sta/Elev= 30
       0  322.81   85.15  317.83  113.77  313.56     345  297.57  383.34   292.5
  444.48  278.44  482.76  272.52  709.77  255.44  790.09  239.88  839.75  236.12
  860.91  229.89  872.34  227.34  903.77  226.93  966.07  229.56 1051.31  231.77
 1086.75  229.51 1274.48  230.97 1344.81  234.39 1382.78  237.76 1402.44  243.07
 1606.61  258.21 1994.12  260.11 2019.08  261.53 2105.52  259.66 2174.68  254.59
 2191.46  255.63 2220.34  253.97 2285.32  253.74 2299.76  256.39 2336.31  257.23
#Mann= 3 , 0 , 0
       0      .1       0  860.91    .043       0  966.07      .1       0
#XS Ineff= 2 , 0
          845.91  237.86   921.4          237.86
Permanent Ineff=
       F       F
Bank Sta=860.91,966.07
XS Rating Curve= 0 ,0
Exp/Cntr=0.5,0.3

Type RM Length L Ch R = 3 ,28677.31,,,
BEGIN DESCRIPTION:
Warburton Rd
END DESCRIPTION:
Bridge Culvert--1,0,-1,-1, 0
Deck Dist Width WeirC Skew NumUp NumDn MinLoCord MaxHiCord MaxSubmerge Is_Ogee
40,34,2.6,0, 60, 60, , , 0.95, 0, 0,0,,
       0  112.28  193.13  259.19  295.62  347.54  356.46  374.29  418.89  454.54
  472.32   479.1  498.99  505.21  552.32  599.96  627.28  638.35   660.7  677.09
  693.47  755.28  772.61  792.84  820.32  842.82  849.12  849.12  864.12  904.12
  929.12  929.12  941.12 1040.34 1054.51 1063.25 1104.51 1162.28 1233.28 1254.14
 1270.19 1286.96 1325.77 1336.89 1353.04 1373.77 1445.21 1480.06 1526.98 1548.01
 1562.41 1594.76 1612.79 1632.66 1638.92 1678.04  1714.4  1765.3 1800.23 1904.86
  315.77     311  305.69  300.58  297.27   291.6  291.22  289.06  284.89  281.03
  278.11  277.65  275.11  274.84  269.59  265.39   261.9  261.24  258.36  257.42
   255.1  248.58  245.61  244.27  241.41  240.09  239.95   242.8   242.8   242.8
   242.8  238.52  238.48   239.9  239.52  239.88  239.61  241.47  242.92  243.75
  243.76  244.97  244.52  245.61  245.89  247.55  250.48  253.06   255.7  257.11
  259.71  262.05   262.5  263.63  263.52  266.16  266.59  270.98  272.45  274.17
                                                                                
                                                                                
                                                                     237     237
                                                                                
                                                                                
                                                                                
       0  112.28  193.13  278.27  320.68  338.62  347.54  356.46  374.29  440.39
  454.54  472.32  498.99  505.21   529.7  599.96  627.28  638.35   660.7  677.09
  693.47  755.28  772.61  792.84  820.32  862.74   870.8   870.8   885.8   935.8
   950.8   950.8  962.16 1040.34 1054.51 1063.25 1104.51 1162.28 1233.28 1254.14
 1270.19 1286.96 1325.77 1336.89 1353.04 1373.77 1445.21 1480.06 1526.98 1548.01
 1562.41 1594.76 1612.79 1632.66 1638.92 1678.04  1714.4  1765.3 1800.23 1904.86
  315.77     311  305.69  298.92  294.29  292.83   291.6  291.22  289.06  282.63
  281.03  278.11  275.11  274.84  271.88  265.39   261.9  261.24  258.36  257.42
   255.1  248.58  245.61  244.27  241.41   238.8   238.8   242.8   242.8   242.8
   242.8  238.82  238.84   239.9  239.52  239.88  239.61  241.47  242.92  243.75
  243.76  244.97  244.52  245.61  245.89  247.55  250.48  253.06   255.7  257.11
  259.71  262.05   262.5  263.63  263.52  266.16  266.59  270.98  272.45  274.17
                                                                                
                                                                                
                                                                     237     237
                                                                                
                                                                                
                                                                                
BR Coef=-1 , 0 , 0 ,, 0 ,,,0.8,0,,0,
WSPro=,,,, 1 ,,,, 0 ,,,, 0 ,,,,-1 ,-1 ,-1 , 0 , 0 , 0 , 0 , 0
BC Design=,, 0 ,, 0 ,,,,,,
BC Use User HTab Curves=0
BC User HTab FreeFlow(D)= 0

Type RM Length L Ch R = 1 ,28616.82,389.71,388.4,389.21
XS GIS Cut Line= 5
 1613757.8915714  728418.9497433 1613197.5231576  728092.0681686
 1612669.8429013   728082.728695 1611941.3639635  727872.5905398
 1611693.8679141  727751.1773835
#Sta/Elev= 30
       0  314.98  206.52   307.2  455.51  290.85   560.7  273.26  749.78  254.94
  784.78  245.15   854.8  238.84   882.8  230.57   910.8  226.97  948.55   228.2
  973.44  231.78 1039.48  231.56 1123.18  236.32 1162.84  238.83 1191.43  244.57
 1258.58  251.27 1301.36  251.34 1460.99  259.87 1519.27  265.79  1555.7  263.26
 1592.13  270.57 1831.96  285.25 1903.64  285.01 1950.34  282.47 1973.52  284.59
 2023.58     283  2044.5  285.12 2074.88  280.78 2152.85  279.01 2210.36  280.03
#Mann= 3 , 0 , 0
       0      .1       0   882.8     .04       0  973.44      .1       0
#XS Ineff= 2 , 0
             877  233.74  954.71          233.87
Permanent Ineff=
       F       F
Bank Sta=882.8,973.44
XS Rating Curve= 0 ,0
Exp/Cntr=0.5,0.3

Type RM Length L Ch R = 1 ,28228.42,294.48,293.99,291.87
XS GIS Cut Line= 2
 1613830.4684611  727859.0088674 1611900.7243394  727537.3848471
#Sta/Elev= 30
       0   301.8   75.61  301.45  211.85  296.64  362.83  284.86   524.1  275.19
  577.41  268.28  623.45  259.68  673.99  253.46  701.51  246.25   729.9  244.16
  744.09  241.15  759.89  234.54  778.14  230.12  814.64  229.61  844.17  226.83
  877.06  225.68  907.31  225.96  919.88   228.4   942.8  228.79  968.93  234.79
  985.38  235.94 1013.76  240.55 1169.89  270.37 1240.85  277.87 1305.69  282.22
 1462.85  297.67 1702.13  311.43  1758.9   313.2 1865.35  313.37 1956.36  308.51
#Mann= 3 , 0 , 0
       0      .1       0  844.17    .045       0  919.88      .1       0
Bank Sta=844.17,919.88
XS Rating Curve= 0 ,0
Exp/Cntr=0.3,0.1

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
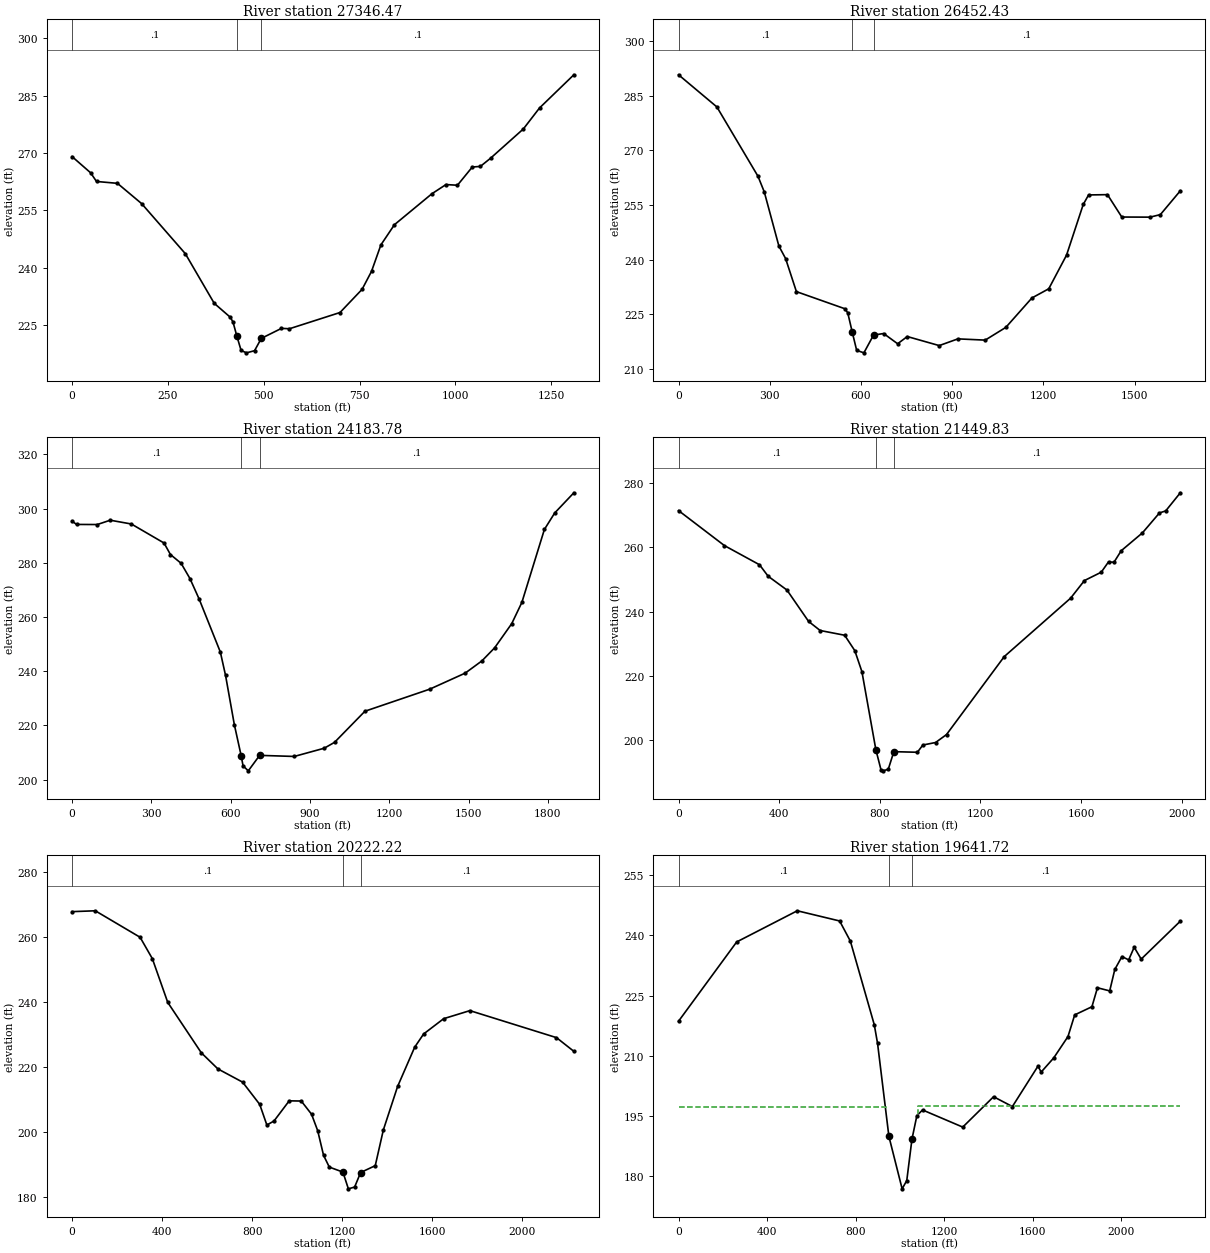
Type RM Length L Ch R = 1 ,27346.47,301.7,298.01,292.48
XS GIS Cut Line= 2
 1613669.6564509  726876.0454554 1612363.0588686  726956.4514605
#Sta/Elev= 30
       0  269.08   48.25  264.85   63.74  262.57  118.38  262.08   181.5  256.77
   295.4  243.68  370.86  230.68  412.94  227.02  419.95  225.75  429.92  222.09
  440.99  218.34  455.02  217.72  476.06  218.28  493.66   221.5  546.19  224.12
  567.23  224.03  698.95  228.27  756.59  234.34  781.16  239.03  805.68  245.97
  840.94  251.25  938.93  259.37  975.46  261.76 1005.35  261.58 1044.13  266.35
  1065.2  266.51 1091.62  268.64 1177.38  276.32 1219.46   281.8 1309.07  290.49
#Mann= 3 , 0 , 0
       0      .1       0  429.92    .045       0  493.66      .1       0
Bank Sta=429.92,493.66
XS Rating Curve= 0 ,0
Exp/Cntr=0.3,0.1

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
Type RM Length L Ch R = 1 ,26452.43,2145.86,2268.65,2246.56
XS GIS Cut Line= 2
 1613508.8444408  725782.5237864 1612051.4855989  726556.4315852
#Sta/Elev= 30
       0  290.74  126.07  281.92  261.29   262.9     282   258.6  329.99  243.76
  352.03  240.34  387.62  231.26  546.14  226.59  556.37  225.48  571.43  220.09
  585.77  215.15  609.54  214.47  641.25  219.34  674.45  219.77   720.5  216.96
  752.21  218.94  857.29  216.46  918.65   218.3 1008.46  217.96 1076.37  221.46
 1162.05  229.52 1217.42  232.04 1275.93  241.27 1330.79  255.16 1348.41  257.78
 1410.53  257.86  1457.6  251.72  1550.3  251.69 1584.41  252.38  1650.1  258.92
#Mann= 3 , 0 , 0
       0      .1       0  571.43    .045       0  641.25      .1       0
Bank Sta=571.43,641.25
XS Rating Curve= 0 ,0
Exp/Cntr=0.3,0.1

Type RM Length L Ch R = 1 ,24183.78,2527.75,2733.95,2842.87
XS GIS Cut Line= 2
 1612986.2054078  724299.0329929 1611227.3240469  725012.6362879
#Sta/Elev= 30
       0  295.36   16.95  294.14   95.33   294.1  144.39   295.7   224.3   294.3
   347.9  287.28  372.13  283.03  412.39  279.81  445.84  274.18  480.56  266.64
  560.85  247.06  580.65   238.4  613.73  220.31  639.63  208.81  646.81  205.06
  666.61  203.22  709.52  208.93  840.35  208.53  953.67  211.56  992.77  213.73
 1107.77  225.21 1352.82  233.35 1487.17  239.28 1550.45   243.8 1598.43  248.61
  1663.1  257.53 1701.53  265.38 1786.66  292.29 1825.73  298.38 1898.13  305.82
#Mann= 3 , 0 , 0
       0      .1       0  639.63    .045       0  709.52      .1       0
Bank Sta=639.63,709.52
XS Rating Curve= 0 ,0
Exp/Cntr=0.3,0.1

Type RM Length L Ch R = 1 ,21449.83,1187.66,1227.61,1238.2
XS GIS Cut Line= 2
 1612755.0381433  723384.4146852 1610825.2940216  722881.8771535
#Sta/Elev= 30
       0  271.38  182.43   260.5  321.75  254.55  356.12  250.98  430.76   246.7
  516.88  236.94  562.79  234.12  660.12  232.65  700.52  227.86  728.81  221.32
  784.27  197.05   804.5  190.87  811.74  190.52  833.44     191  855.67  196.48
  949.17  196.29  970.87  198.54 1021.51  199.32 1064.91  201.79 1294.43  226.02
 1558.01  244.16 1613.02  249.64 1679.75  252.23 1708.69  255.43 1730.39  255.32
 1759.32  258.91 1843.58  264.46 1911.23  270.65 1936.02  271.28 1994.11  276.91
#Mann= 3 , 0 , 0
       0      .1       0  784.27    .045       0  855.67      .1       0
Bank Sta=784.27,855.67
XS Rating Curve= 0 ,0
Exp/Cntr=0.3,0.1

Type RM Length L Ch R = 1 ,20222.22,612.4,580.5,538.3
XS GIS Cut Line= 4
  1613392.925699  722721.0925807 1612471.4309741  722306.0048668
 1612222.3783458  722007.1417128 1611448.4405609  721710.9647046
#Sta/Elev= 30
       0   267.8  103.05  268.07  302.08  259.91  356.47  253.32  424.92  239.84
  573.94  224.32  647.56  219.36  757.34  215.28   833.3  208.43  865.06  202.07
  896.82  203.31  964.28  209.52 1017.83  209.46 1063.39  205.41 1090.73  200.34
 1116.78  192.75 1142.33  189.11 1202.88  187.57 1227.03  182.41 1254.75  182.96
  1281.5  187.44  1346.4  189.55 1382.31  200.55 1445.61  213.94 1521.53  226.05
 1561.21  230.12 1650.23  234.83 1766.69  237.31 2151.19  228.99 2228.38  224.77
#Mann= 3 , 0 , 0
       0      .1       0 1202.88    .045       0  1281.5      .1       0
Bank Sta=1202.88,1281.5
XS Rating Curve= 0 ,0
Exp/Cntr=0.5,0.3

Type RM Length L Ch R = 1 ,19641.72,343.74,353.76,361.02
XS GIS Cut Line= 3
 1613799.9192024  722219.8741661 1612475.2380319  721766.7667155
 1611707.8771244  721365.3123352
#Sta/Elev= 30
       0  218.62  262.55  238.38  536.28  246.15   727.5  243.61  775.93  238.59
     884  217.74  898.79  213.09  949.93  189.93 1009.76  176.84 1030.69   178.9
 1054.15  189.23 1076.35  195.09 1102.01   196.5  1283.5  192.23 1422.73   199.8
 1507.65  197.35 1623.06  207.41  1637.9  205.96  1694.3  209.47 1758.71   214.8
  1789.1   220.2 1866.83  222.23  1891.8  226.96  1947.1  226.18 1970.12  231.52
  2002.4  234.74  2032.8  233.91  2057.7  237.06  2089.3   234.1 2266.06  243.56
#Mann= 3 , 0 , 0
       0      .1       0  949.93     .04       0 1054.15      .1       0
#XS Ineff= 2 , 0
          934.72  197.28 1081.26          197.38
Permanent Ineff=
       F       F
Bank Sta=949.93,1054.15
XS Rating Curve= 0 ,0
Exp/Cntr=0.5,0.3