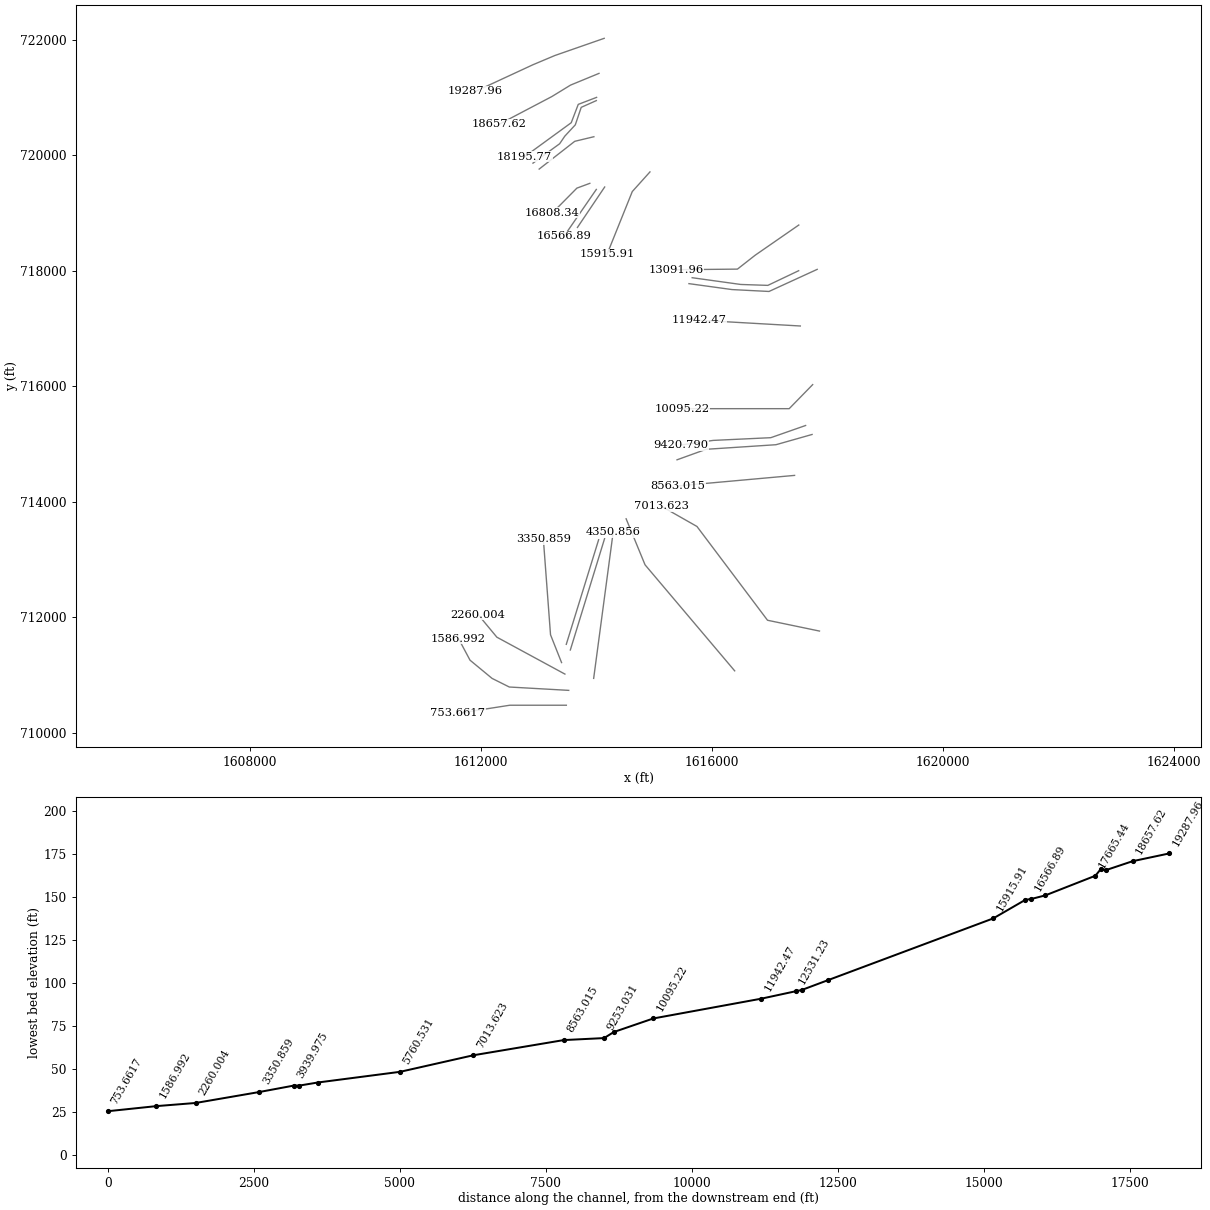
HEC-RAS study LittleNortheast.prj: Little Northeast Creek

--- LittleNortheast.g03 (geometry) --- (continued)

Type RM Length L Ch R = 3 ,19509.95,,,
BEGIN DESCRIPTION:
I-95 JFK Memorial Hwy
END DESCRIPTION:
Bridge Culvert--1,0,-1,-1, 0
Deck Dist Width WeirC Skew NumUp NumDn MinLoCord MaxHiCord MaxSubmerge Is_Ogee
100,156,2.6,0, 60, 60, , , 0.95, 0, 0,0,,
       0   34.39      47   76.49   91.39   98.85  210.01  219.73  254.93  298.22
  312.64  337.37  412.87  505.64  538.82  559.77  675.99  687.69  732.42  769.69
  853.54  918.76  963.48 1075.29 1100.48 1122.31 1127.47 1172.65 1235.05 1241.04
 1279.04 1362.64  1418.6 1453.32 1469.04 1488.47  1541.8 1583.04 1588.85 1613.44
 1651.44 1698.64 1704.63 1751.76 1788.23 1795.83 1818.63 1826.23 1910.48  1927.6
 1982.76 1986.06 1990.31 2005.14 2034.48 2042.55 2059.68 2075.06 2099.04 2221.97
  218.34  218.38  218.01  217.93  217.41  217.74  217.37  217.72  217.51  217.97
  217.68  218.15  218.34  219.48  220.23  220.25  222.68  222.81  223.46  224.37
  225.21  226.74  227.39  229.85  230.73  231.05  230.86  232.33  233.39  233.75
  234.37  236.47   237.2  238.23  238.27  238.93  239.81  240.93  240.76  241.55
  242.05  243.33  243.15  244.41  244.85  245.31  245.16  245.95  247.82   247.8
  249.18  249.15  249.19  249.64   249.9  250.34  250.42  251.04  251.26  253.61
                                                                                
                                                          214.81  215.46  216.37
  217.21  218.74  219.39  221.85  222.73  223.05  222.86  224.33  225.39  225.75
  226.37  228.47   229.2  230.23  230.27  230.93  231.81  232.93  232.76  233.55
  234.05  235.33  235.15  236.41  236.85  237.31  237.16  237.95  239.82   239.8
  241.18  241.15
       0   34.39      47   76.49   91.39   98.85  145.47  210.01  219.73  254.93
  298.22  312.64  337.37  412.87  505.64  538.82  559.77  675.99  687.69  732.42
  769.69  853.54  918.76  963.48 1075.29 1100.48 1122.31 1127.47 1138.68 1153.55
 1172.65 1235.05 1241.04 1279.04 1362.64  1418.6 1453.32 1469.04 1488.47  1541.8
 1583.04 1588.85 1613.44  1652.3 1666.64 1751.76 1788.23 1795.83 1818.63 1826.23
 1910.48  1927.6 2001.01 2018.66 2034.48 2042.55 2059.68 2075.06 2099.04 2221.97
  218.34  218.38  218.01  217.93  217.41  217.74  217.39  217.37  217.72  217.51
  217.97  217.68  218.15  218.34  219.48  220.23  220.25  222.68  222.81  223.46
  224.37  225.21  226.74  227.39  229.85  230.73  231.05  230.86  231.42  231.62
  232.33  233.39  233.75  234.37  236.47   237.2  238.23  238.27  238.93  239.81
  240.93  240.76  241.55  242.08  242.42  244.41  244.85  245.31  245.16  245.95
  247.82   247.8  249.57  249.63   249.9  250.34  250.42  251.04  251.26  253.61
                                                                                
                                                                  214.81  215.46
  216.37  217.21  218.74  219.39  221.85  222.73  223.05  222.86  223.42  223.62
  224.33  225.39  225.75  226.37  228.47   229.2  230.23  230.27  230.93  231.81
  232.93  232.76  233.55  234.08
                                                                                
Pier Skew, UpSta & Num, DnSta & Num=  ,953.76, 2 ,1047.08, 2 , 0 , 0 , 0 ,,
       3       3
     180     225
       3       3
     180     225
Pier Skew, UpSta & Num, DnSta & Num=  ,1065.75, 2 ,1159.08, 2 , 0 , 0 , 0 ,,
       3       3
     180     225
       3       3
     180     225
Abutment Skew #Up #Dn= , 3 , 3
 1076.35 1136.35 1986.06
  195.09  225.09  241.15
 1195.73 1275.73  1652.3
  181.48  231.45  234.08
BR Coef=-1 , 1 , 0 ,, 0 ,,,0.8,0,1.2,0,
WSPro=,,,, 1 ,,,, 0 ,,,, 0 ,,,,-1 ,-1 ,-1 , 0 , 0 , 0 , 0 , 0
BC Design=,, 0 ,, 0 ,,,,,,
BC Use User HTab Curves=0
BC User HTab FreeFlow(D)= 0

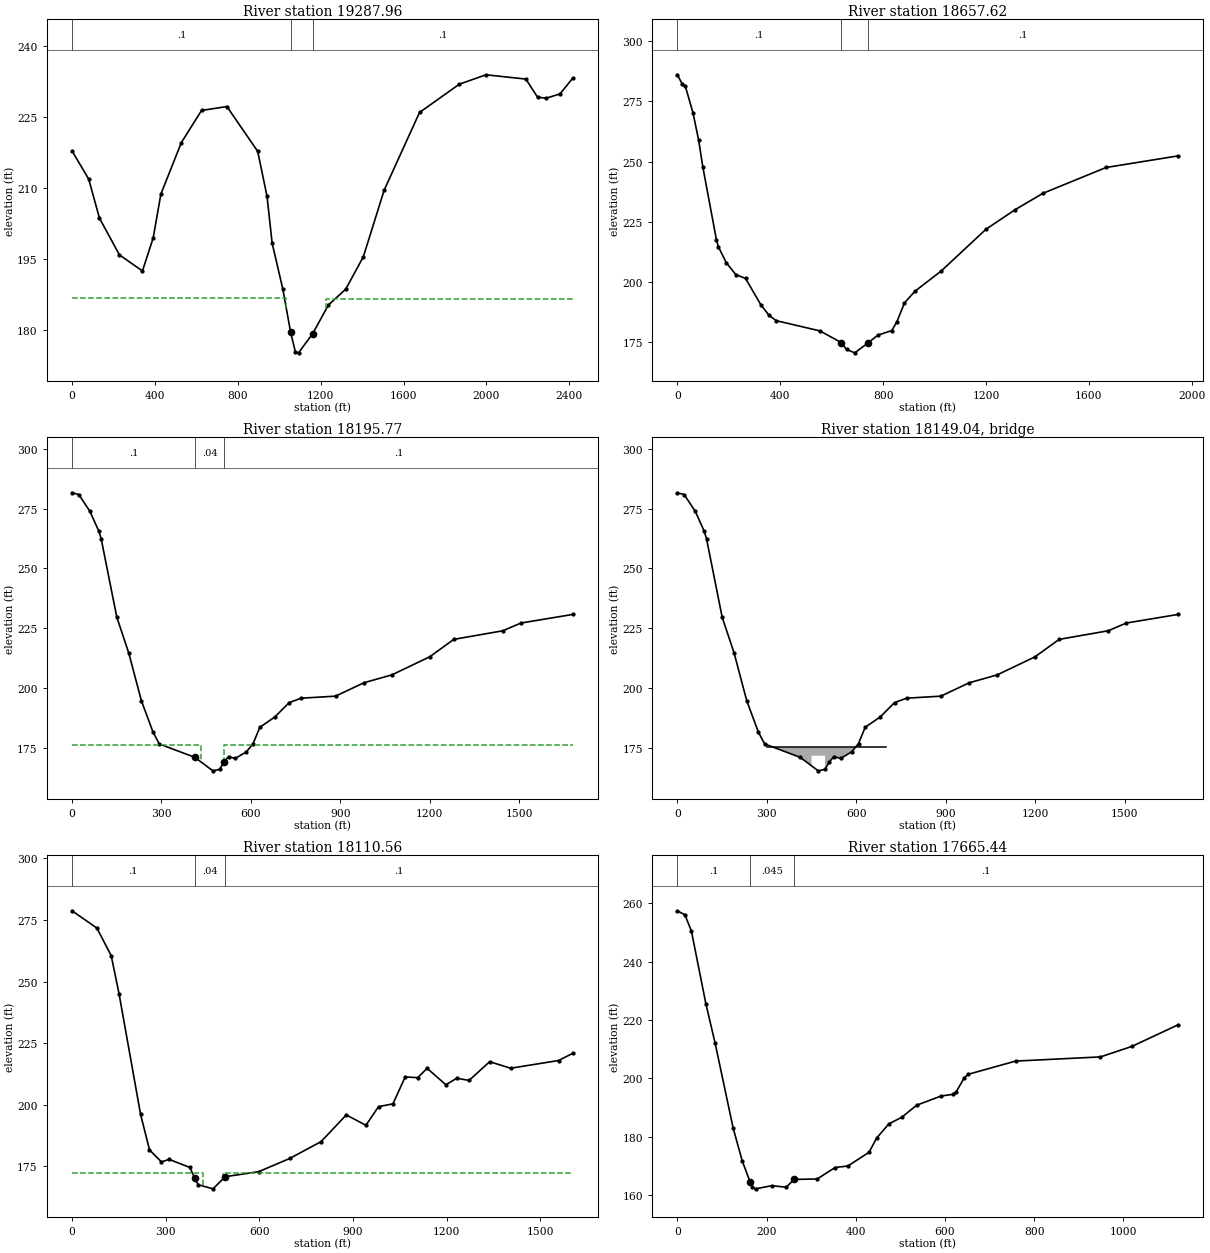
Type RM Length L Ch R = 1 ,19287.96,611.82,630.34,626.94
XS GIS Cut Line= 4
 1614131.4705139  722028.4149581 1613277.6771762  721731.0662059
 1612895.7486521  721570.2541958 1611899.3363325  721108.4768122
#Sta/Elev= 30
       0  217.89   80.45  211.93  132.33  203.68  228.69  195.89  339.88  192.49
  391.77  199.48  428.73  208.74  527.69  219.66  625.09  226.45  747.48  227.28
  896.11  217.79  941.17  208.27  965.74  198.38 1017.13  188.69  1055.1   179.5
 1077.66   175.4 1093.08  175.16 1161.23  179.21 1237.39  185.28 1320.97  188.64
 1405.84  195.48 1506.14  209.56 1676.99  226.02 1868.75     232 1997.89     234
 2190.08  233.09 2246.79  229.26 2288.53  229.05 2354.81  229.95 2416.71   233.3
#Mann= 3 , 0 , 0
       0      .1       0  1055.1     .04       0 1161.23      .1       0
#XS Ineff= 2 , 0
         1034.64  186.74 1225.58          186.56
Permanent Ineff=
       F       F
Bank Sta=1055.1,1161.23
XS Rating Curve= 0 ,0
Exp/Cntr=0.5,0.3

Type RM Length L Ch R = 1 ,18657.62,375.64,461.86,535.66
XS GIS Cut Line= 4
 1614041.8115677  721421.3491765 1613549.0474433  721218.4779236
  1613224.607631  721019.7518133 1612309.3392218  720538.7689249
#Sta/Elev= 30
       0  286.03   18.51  282.26   30.62  281.42    60.9  270.18   82.86  258.82
   98.75   247.9  151.74  217.64  159.31  214.66   190.1  208.07  227.44  203.08
  265.29  201.49  324.86  190.52  356.13  186.22  384.54  183.98  554.64  179.73
  636.73  174.91  657.71  172.04  689.69  170.63  739.62  174.61  779.82  177.97
  833.74  179.88  853.98  183.61  882.99  191.32  923.64  196.18 1026.44  204.64
 1200.41  221.95 1314.24   230.1 1421.83  236.85 1667.21  247.56 1947.31  252.37
#Mann= 3 , 0 , 0
       0      .1       0  636.73    .045       0  739.62      .1       0
Bank Sta=636.73,739.62
XS Rating Curve= 0 ,0
Exp/Cntr=0.5,0.3

Type RM Length L Ch R = 1 ,18195.77,80.94,85.21,109.27
XS GIS Cut Line= 4
 1613999.7839366   721005.742603 1613682.2418355  720884.3294467
 1613560.8286792  720566.7873456 1612752.9642161  719978.4005111
#Sta/Elev= 30
       0  281.63   22.79  280.89   60.26  273.81   90.23  265.48   97.73  262.44
  150.19  229.63  190.16   214.7  232.63   194.7  271.48  181.63  292.58  176.64
  412.04  171.02  472.53  165.39  495.02     166  510.04   169.2  524.99  171.35
  547.48  170.55  584.95  173.36  607.43   176.8  629.91  183.61  679.92  187.88
  728.32  193.92  768.41  195.76  883.65  196.61  978.85  202.21  1072.5   205.5
 1199.31  213.05 1280.33  220.35 1444.77  223.94 1505.49  227.18 1679.35  230.78
#Mann= 3 , 0 , 0
       0      .1       0  412.04     .04       0  510.04      .1       0
#XS Ineff= 2 , 0
          433.21  176.03  508.35          176.21
Permanent Ineff=
       F       F
Bank Sta=412.04,510.04
XS Rating Curve= 0 ,0
Exp/Cntr=0.5,0.3

Type RM Length L Ch R = 3 ,18149.04,,,
BEGIN DESCRIPTION:
Quarry Rd
END DESCRIPTION:
Bridge Culvert--1,0,-1,-1, 0
Deck Dist Width WeirC Skew NumUp NumDn MinLoCord MaxHiCord MaxSubmerge Is_Ogee
40,10,2.6,0, 6, 6, , , 0.95, 0, 0,0,,
     300     450     450     495     495     700
  175.21  175.21  175.21  175.21  175.21  175.21
                  171.71  171.71
     350     429     429     474     474     700
  175.21  175.21  175.21  175.21  175.21  175.21
                  171.71  171.71
BR Coef=-1 , 0 , 0 ,, 0 ,,,0.8,0,,0,
WSPro=,,,, 1 ,,,, 0 ,,,, 0 ,,,,-1 ,-1 ,-1 , 0 , 0 , 0 , 0 , 0
BC Design=,, 0 ,, 0 ,,,,,,
BC Use User HTab Curves=0
BC User HTab FreeFlow(D)= 0

Type RM Length L Ch R = 1 ,18110.56,105,89.02,53.42
XS GIS Cut Line= 6
 1613995.1141999  720949.7057616 1613733.6089401  720832.9623421
 1613630.8747309  720529.4294513 1613448.7549965  720333.3005065
 1613360.0299976  720202.5478766 1612897.7260563  719866.3268284
#Sta/Elev= 30
       0  278.68   79.52  271.68  125.52   260.5  150.53  245.12  219.43  196.26
  248.17  181.73  286.38  176.87  311.15  177.87  377.66  174.61  392.44  170.32
  404.36  167.61  451.56  165.94  490.79  170.87   597.6  172.88  697.62  178.27
  797.78  185.08  878.49  195.91  941.47  191.71  981.79  199.25 1028.09  200.41
 1067.26  211.33 1107.33     211 1137.42  214.81 1197.55  208.14 1232.63  210.79
 1271.79  209.89 1337.86   217.5 1404.91  214.84 1558.35  217.96 1604.13  220.89
#Mann= 3 , 0 , 0
       0      .1       0  392.44     .04       0  490.79      .1       0
#XS Ineff= 2 , 0
          418.83  172.21  484.68          172.25
Permanent Ineff=
       F       F
Bank Sta=392.44,490.79
XS Rating Curve= 0 ,0
Exp/Cntr=0.5,0.3

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
Type RM Length L Ch R = 1 ,17665.44,852.56,857.1,815.58
XS GIS Cut Line= 3
 1613953.0865689  720323.9610329 1613621.5352574  720244.5755076
 1613005.1300023  719763.5926192
#Sta/Elev= 30
       0  257.39   17.06  255.98   31.45  250.45   63.92  225.55   84.78  211.97
  125.02  183.01  145.22  171.86  162.65   164.7  168.21   162.7  175.41   162.2
   211.4  163.27  243.95  162.77  261.78  165.42  313.64  165.58   353.4   169.5
  382.33  170.02  429.76  174.71  446.71  179.57  474.15  184.43   503.6  186.75
   536.3  190.82  591.79     194  617.39  194.54  625.09  195.37  642.85  200.13
  651.73   201.4  758.28  205.93  948.67  207.37 1019.16  210.96 1122.78  218.37
#Mann= 3 , 0 , 0
       0      .1       0  162.65    .045       0  261.78      .1       0
Bank Sta=162.65,261.78
XS Rating Curve= 0 ,0
Exp/Cntr=0.3,0.1

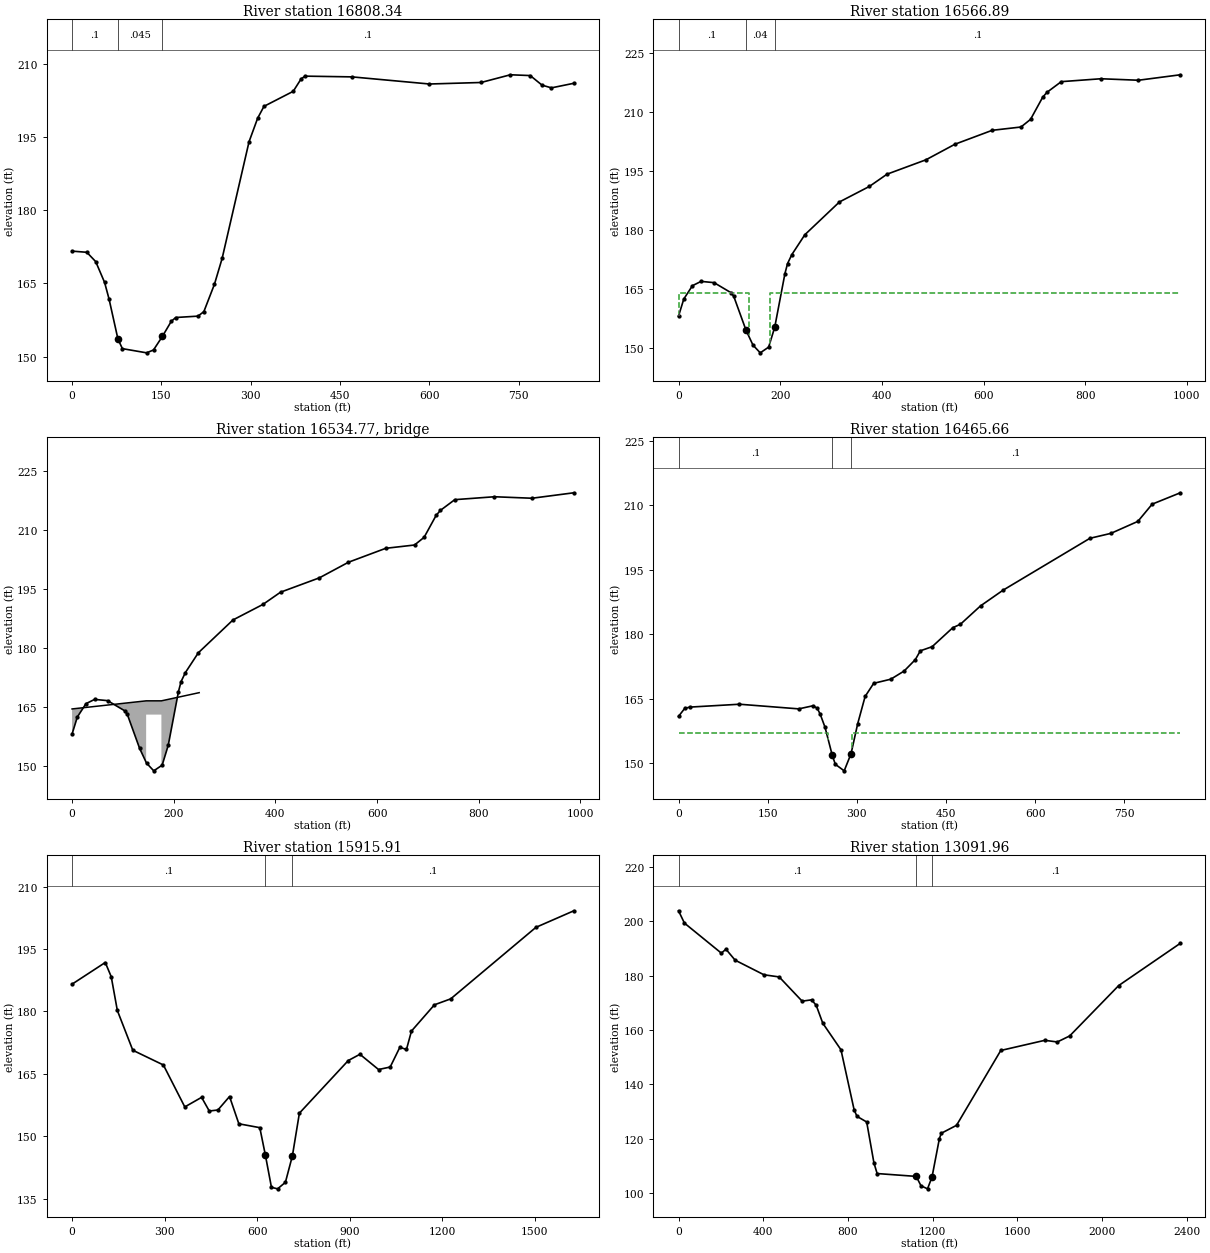
Type RM Length L Ch R = 1 ,16808.34,207.26,241.45,273.28
XS GIS Cut Line= 3
 1613882.7292014  719516.6154294 1613658.5818358  719433.5978866
 1613233.9471045  719004.7603922
#Sta/Elev= 30
       0  171.62   24.77  171.38    39.7  169.47   54.63   165.2   62.09  161.81
   77.02   153.6   84.49  151.64  125.21  150.78  136.74  151.37  151.67  154.15
   166.6  157.24  174.06  158.02  211.39   158.3  221.27  159.22  239.03  164.82
  251.93  170.11  297.14  194.03  311.63  198.86   322.2  201.28  371.32  204.36
  384.58  206.91  391.15  207.47  469.96  207.32  600.14  205.86  686.69  206.17
  735.94  207.75  769.26  207.59  789.16  205.62   804.9  205.07  842.53  206.01
#Mann= 3 , 0 , 0
       0      .1       0   77.02    .045       0  151.67      .1       0
Bank Sta=77.02,151.67
XS Rating Curve= 0 ,0
Exp/Cntr=0.5,0.3

Type RM Length L Ch R = 1 ,16566.89,100.59,101.24,101.58
BEGIN DESCRIPTION:
Quarry located on Left Bank
END DESCRIPTION:
XS GIS Cut Line= 2
 1613995.1141999  719411.0274922 1613434.7457861  718598.4932922
#Sta/Elev= 30
       0  158.05   10.36  162.39   27.37  165.78   44.37  166.87   69.88  166.55
  103.89  163.94  108.66  163.05  132.74  154.45  146.41  150.66   160.7  148.69
  177.22  150.14  189.18  155.19  209.31  168.87  214.44  171.41  222.94   173.7
  248.45  178.74  316.48  187.08  375.39  191.03  410.01  194.14  486.54   197.8
  543.73  201.77  616.95  205.31  673.61  206.15  692.44   208.1  716.13  213.69
  724.63  214.97  752.83  217.69  830.87  218.43  904.68  218.05  987.03  219.44
#Mann= 3 , 0 , 0
       0      .1       0  132.74     .04       0  189.18      .1       0
#XS Ineff= 2 , 0
          137.66  163.82   179.4          164.02
Permanent Ineff=
       F       F
Bank Sta=132.74,189.18
XS Rating Curve= 0 ,0
Exp/Cntr=0.3,0.3

Type RM Length L Ch R = 3 ,16534.77,,,
BEGIN DESCRIPTION:
Lums Rd
END DESCRIPTION:
Bridge Culvert--1,0,-1,-1, 0
Deck Dist Width WeirC Skew NumUp NumDn MinLoCord MaxHiCord MaxSubmerge Is_Ogee
35,30,2.6,0, 6, 6, , , 0.95, 0, 0,0,,
       0   145.7   145.7   175.7   175.7     250
  164.44   166.5   166.5   166.5   166.5  168.58
                     163     163
       0     257     257     287     287     400
  164.44   166.5   166.5   166.5   166.5  168.58
                     163     163
BR Coef=-1 , 0 , 0 ,, 0 ,,,0.8,0,,0,
WSPro=,,,, 1 ,,,, 0 ,,,, 0 ,,,,-1 ,-1 ,-1 , 0 , 0 , 0 , 0 , 0
BC Design=,, 0 ,, 0 ,,,,,,
BC Use User HTab Curves=0
BC User HTab FreeFlow(D)= 0

Type RM Length L Ch R = 1 ,16465.66,545.43,549.75,551.02
XS GIS Cut Line= 2
 1614139.8760401  719453.0551232 1613668.2326252   718752.594606
#Sta/Elev= 30
       0  160.88   10.31  162.71   18.75  163.03  102.59   163.7  202.26  162.62
  226.27  163.34  233.38  162.77  238.42  161.38   246.6  158.31  258.59  151.87
  263.87  149.71  278.77  148.19  290.32  152.19  301.47  159.15     314  165.51
  328.43  168.57   357.2  169.53  379.63  171.43   398.5  174.09  406.94  176.14
   426.8   177.1  461.49  181.52  474.45  182.33  508.21   186.6  546.06  190.25
  692.31  202.34  727.64  203.49     773  206.28  797.06  210.29  844.45  212.94
#Mann= 3 , 0 , 0
       0      .1       0  258.59     .04       0  290.32      .1       0
#XS Ineff= 2 , 0
          252.13  156.92   292.4          156.92
Permanent Ineff=
       F       F
Bank Sta=258.59,290.32
XS Rating Curve= 0 ,0
Exp/Cntr=0.5,0.3

Type RM Length L Ch R = 1 ,15915.91,2612.31,2823.95,2558.72
XS GIS Cut Line= 3
 1614924.3918193   719714.560383 1614618.1844281  719374.2289215
 1614181.9036711  718290.2906647
#Sta/Elev= 30
       0  186.55   107.6  191.75  126.92  188.34  146.71  180.23  196.82  170.68
  295.95  167.14  365.34  157.07  419.78  159.37  444.65  156.09  472.61  156.33
  510.34  159.57  540.52  153.02  608.43  152.09  626.45  145.51  646.16  137.77
  666.06   137.4  691.43  138.97  714.07  145.33  736.71  155.57  895.17  168.21
   932.9  169.71  993.26  166.05 1030.99  166.65 1062.25  171.38 1083.77  170.87
 1099.91  175.28 1174.36  181.59 1227.18  183.02 1503.26  200.19 1626.25  204.17
#Mann= 3 , 0 , 0
       0      .1       0  626.45    .045       0  714.07      .1       0
Bank Sta=626.45,714.07
XS Rating Curve= 0 ,0
Exp/Cntr=0.3,0.1

Type RM Length L Ch R = 1 ,13091.96,509.62,456.28,372.22
XS GIS Cut Line= 4
 1617502.2940665  718794.3628073 1616746.8344272  718271.3522878
 1616439.6695189  718030.6014137 1615378.2840587  718020.3290719
#Sta/Elev= 30
       0  203.94   27.78  199.41  202.24  188.35  223.99   189.8  267.33  185.76
  403.55  180.38  475.53  179.59  583.84  170.67   628.7  171.16  650.45  169.13
  681.49  162.55  767.32  152.78  829.24  130.77  842.79  128.28  888.84   126.2
  923.07  111.16   938.2  107.22 1122.68  106.17 1145.42  102.73 1176.18  101.59
 1197.47  105.93 1232.37   120.1 1241.19  122.04 1313.28  124.97  1522.3  152.52
 1730.27  156.26  1789.3  155.65 1847.86  157.87 2079.63  176.43 2370.54  191.97
#Mann= 3 , 0 , 0
       0      .1       0 1122.68    .045       0 1197.47      .1       0
Bank Sta=1122.68,1197.47
XS Rating Curve= 0 ,0
Exp/Cntr=0.5,0.3

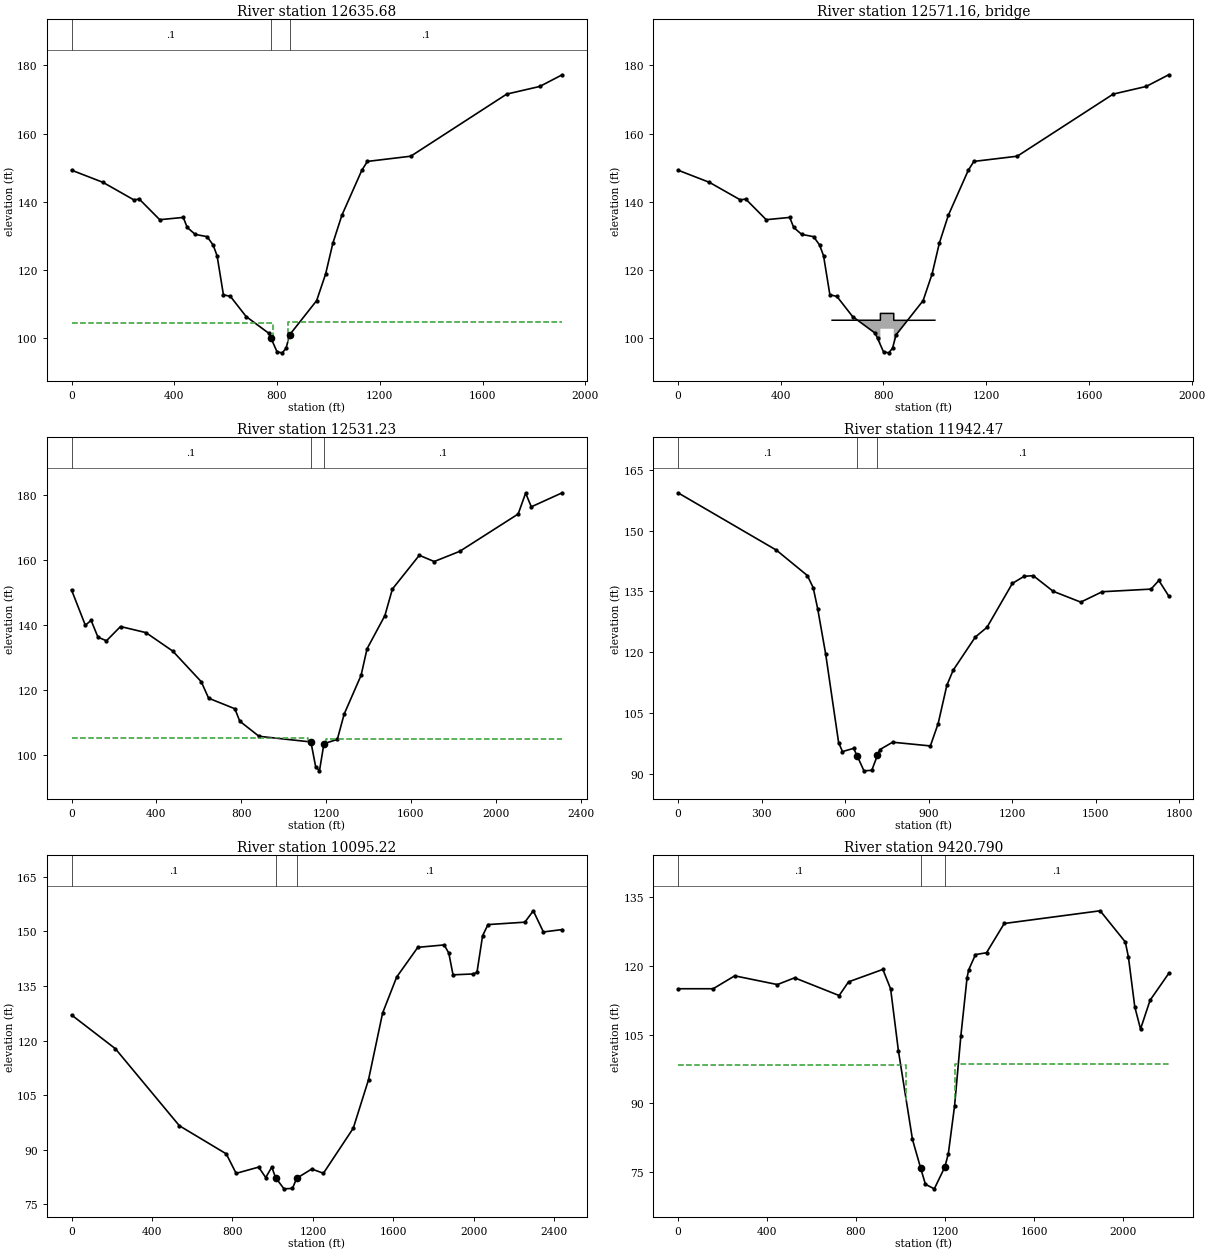
Type RM Length L Ch R = 1 ,12635.68,106.72,104.45,99.34
XS GIS Cut Line= 4
 1617500.2186279  718003.1018527 1616966.3026588  717748.9588048
 1616496.2252199  717764.9452768 1615655.6725993  717881.6886963
#Sta/Elev= 30
       0   149.3  122.69  145.72   242.6   140.6  263.61  140.84  343.43  134.79
  434.94  135.46  450.44  132.53  481.45  130.49  527.97  129.82  551.23  127.38
  566.73  124.21  591.32  112.81  618.74  112.31  679.71  106.43  767.77  101.54
     777  100.02  800.24   96.06   820.5   95.79  835.26   97.14  849.05  101.06
  954.33  111.09  989.35  118.92 1017.37  127.89 1052.39  136.07 1130.04  149.25
 1151.82  151.86 1320.85  153.39 1694.25  171.58 1822.78  173.82 1910.29  177.24
#Mann= 3 , 0 , 0
       0      .1       0     777     .04       0  849.05      .1       0
#XS Ineff= 2 , 0
           783.3  104.55  841.92          104.68
Permanent Ineff=
       F       F
Bank Sta=777,849.05
XS Rating Curve= 0 ,0
Exp/Cntr=0.5,0.3

Type RM Length L Ch R = 3 ,12571.16,,,
BEGIN DESCRIPTION:
Union Church Rd
END DESCRIPTION:
Bridge Culvert--1,0,-1,-1, 0
Deck Dist Width WeirC Skew NumUp NumDn MinLoCord MaxHiCord MaxSubmerge Is_Ogee
50,25,2.6,0, 6, 6, , , 0.95, 0, 0,0,,
     600     788     788     840     840    1000
  105.34  105.34  107.34  107.34  105.31  105.34
                  102.84  102.84
     600    1135    1135    1187    1187    1300
  105.34  105.34  107.34  107.34  105.31  105.34
                  102.84  102.84
BR Coef=-1 , 0 , 0 ,, 0 ,,,0.8,0,,0,
WSPro=,,,, 1 ,,,, 0 ,,,, 0 ,,,,-1 ,-1 ,-1 , 0 , 0 , 0 , 0 , 0
BC Design=,, 0 ,, 0 ,,,,,,
BC Use User HTab Curves=0
BC User HTab FreeFlow(D)= 0

Type RM Length L Ch R = 1 ,12531.23,581.2,588.75,569.49
XS GIS Cut Line= 4
 1617821.4965185  718026.4505366  1616986.547582  717643.5321205
 1616346.7936429   717676.220278 1615599.6357579  717778.9544872
#Sta/Elev= 30
       0  150.81   65.12  139.92   92.41  141.41  124.62  136.25  164.69  135.13
  231.03  139.52  350.68  137.65   477.4  131.95  611.59  122.52  646.35  117.44
   770.1  114.19   793.2  110.36  883.93   105.7 1128.64  103.96  1150.8   96.38
 1168.94   95.06 1189.97  103.44 1253.05  104.73 1285.35  112.54  1365.2   124.5
 1393.23  132.66 1477.34  142.89 1512.74  151.07 1639.53  161.47 1709.85  159.55
 1829.97  162.68 2105.72  174.19 2140.87  180.64 2167.53   176.4 2313.34  180.73
#Mann= 3 , 0 , 0
       0      .1       0 1128.64     .04       0 1189.97      .1       0
#XS Ineff= 2 , 0
         1112.72  105.23 1201.47          104.82
Permanent Ineff=
       F       F
Bank Sta=1128.64,1189.97
XS Rating Curve= 0 ,0
Exp/Cntr=0.5,0.3

Type RM Length L Ch R = 1 ,11942.47,1675.31,1847.25,1560.15
XS GIS Cut Line= 2
 1617529.1446943  717045.4062604 1615770.2633334  717145.9137667
#Sta/Elev= 30
       0  159.31  353.28  145.17   464.4  138.91  485.44  135.92  501.44  130.76
  530.35  119.51  576.77   97.69  590.61    95.5  630.61   96.29   643.1   94.48
  667.73   90.75  695.78   90.88  716.05   94.56   725.1      96   770.6   97.81
  906.12   96.89  934.17  102.42  965.23  111.82  987.89  115.55 1067.38  123.73
 1109.45  126.14  1200.6  136.97 1242.67  138.71 1275.39  138.88 1346.96  135.02
    1446  132.35 1523.13  134.91 1698.41  135.56 1726.46  137.69 1761.75  133.87
#Mann= 3 , 0 , 0
       0      .1       0   643.1    .045       0  716.05      .1       0
Bank Sta=643.1,716.05
XS Rating Curve= 0 ,0
Exp/Cntr=0.3,0.1

Type RM Length L Ch R = 1 ,10095.22,649.68,674.44,581.1
XS GIS Cut Line= 3
 1617743.0449405  716029.8786327 1617336.2589809  715613.1742951
 1615479.7966401  715613.1742951
#Sta/Elev= 30
       0  127.02  217.75  117.76  536.04   96.59   769.1   88.87   818.1   83.51
   930.1   85.23   965.1   82.36  995.42   85.23  1014.1   82.34  1056.1   79.26
  1098.1   79.38  1119.1   82.16 1193.76    84.7  1252.1   83.54 1400.26   95.91
  1476.1  109.23  1546.1  127.54  1616.1  137.43  1721.1  145.59 1851.76  146.25
  1875.1  144.03  1896.1  138.04  1994.1  138.27  2015.1  138.71  2043.1  148.78
 2069.93  151.84  2253.1   152.5  2295.1  155.63 2345.26  149.81  2438.8  150.47
#Mann= 3 , 0 , 0
       0      .1       0  1014.1    .045       0  1119.1      .1       0
Bank Sta=1014.1,1119.1
XS Rating Curve= 0 ,0
Exp/Cntr=0.5,0.3

Type RM Length L Ch R = 1 ,9420.790,160.4,167.76,162.87
XS GIS Cut Line= 4
 1617620.6065251  715321.7025267 1617017.5614871  715110.6367634
 1616018.9781209  715063.5025488 1615458.6097071  714984.1170236
#Sta/Elev= 30
       0  114.98  157.98  114.98  254.89  117.79  446.55  115.89  523.97  117.36
  724.07   113.5  766.25  116.48  920.43  119.19  955.33  114.95  990.37  101.44
 1053.44   82.17 1089.59   76.02 1111.65    72.4 1151.55    71.4 1199.07   76.17
 1214.62   79.06 1242.65   89.46 1270.68  104.61 1298.71  117.38 1305.72  119.06
 1336.63  122.42 1386.08  122.82 1465.82  129.19 1896.74  131.96 2009.76  125.16
  2023.9  121.82 2052.18  111.05 2078.07   106.2 2121.03  112.48 2204.57   118.3
#Mann= 3 , 0 , 0
       0      .1       0 1089.59     .04       0 1199.07      .1       0
#XS Ineff= 2 , 0
         1025.75   98.32 1245.56           98.59
Permanent Ineff=
       F       F
Bank Sta=1089.59,1199.07
XS Rating Curve= 0 ,0
Exp/Cntr=0.5,0.3

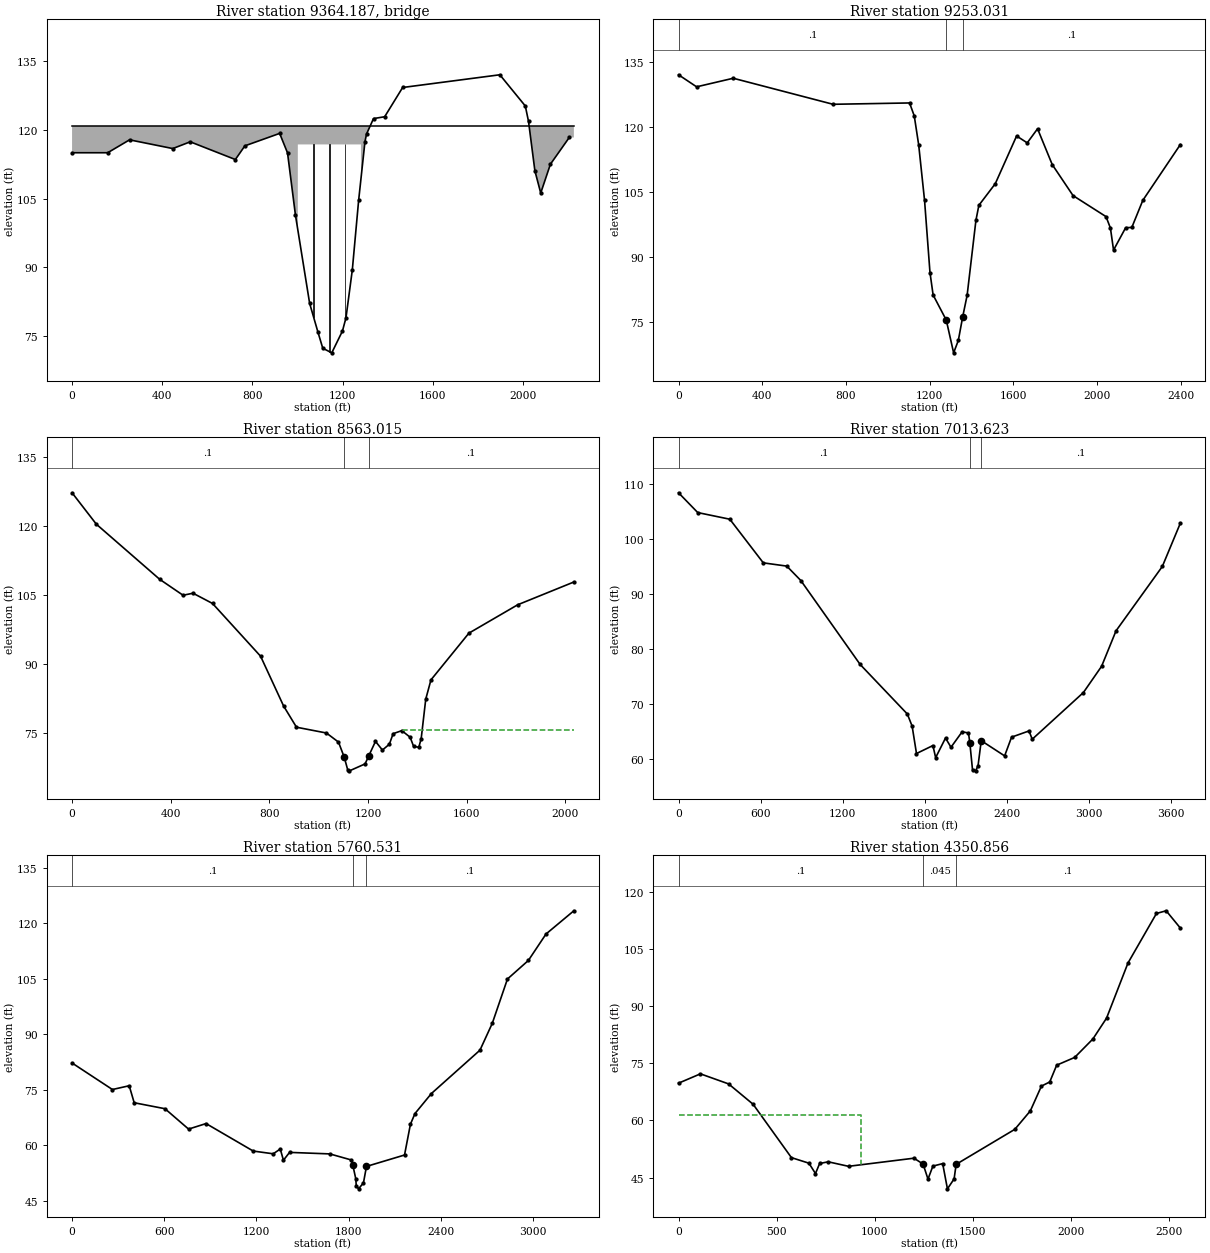
Type RM Length L Ch R = 3 ,9364.187,,,
BEGIN DESCRIPTION:
Railroad
END DESCRIPTION:
Bridge Culvert--1,0,-1,-1, 0
Deck Dist Width WeirC Skew NumUp NumDn MinLoCord MaxHiCord MaxSubmerge Is_Ogee
50,28,2.6,0, 4, 4, , , 0.95, 0, 0,0,,
       0    1001    1281    2225
  120.79  120.79  120.79  120.79
          116.79  116.79
       0    1161    1441    2400
  120.79  120.79  120.79  120.79
          116.79  116.79
Pier Skew, UpSta & Num, DnSta & Num=  ,1071, 2 ,1301, 2 , 0 , 0 , 0 ,,
       2       2
      70  116.79
       2       2
      70  116.79
Pier Skew, UpSta & Num, DnSta & Num=  ,1141, 2 ,1231, 2 , 0 , 0 , 0 ,,
       2       2
      70  116.79
       2       2
      70  116.79
Pier Skew, UpSta & Num, DnSta & Num=  ,1211, 2 ,1371, 2 , 0 , 0 , 0 ,,
       2       2
      70  116.79
       2       2
      70  116.79
BR Coef=-1 , 1 , 0 ,, 0 ,,,0.8,0,1.2,0,
WSPro=,,,, 1 ,,,, 0 ,,,, 0 ,,,,-1 ,-1 ,-1 , 0 , 0 , 0 , 0 , 0
BR U #Sta/Elev= 30
       0  114.98  157.98  114.98  254.89  117.79  446.55  115.89  523.97  117.36
  724.07   113.5  766.25  116.48  920.43  119.19  955.33  114.95  990.37  101.44
 1053.44   82.17 1089.59   76.02 1111.65    72.4 1151.55    71.4 1199.07   76.17
 1214.62   79.06 1242.65   89.46 1270.68  104.61 1298.71  117.38 1305.72  119.06
 1336.63  122.42 1386.08  122.82 1465.82  129.19 1896.74  131.96 2009.76  125.16
  2023.9  121.82 2052.18  111.05 2078.07   106.2 2121.03  112.48 2204.57   118.3
BR U #Mann= 3
       0      .1 1089.59     .04 1199.07      .1
BR D #Sta/Elev= 30
       0  132.03   86.38  129.25  261.57  131.23  738.64  125.22 1104.37  125.53
 1126.89  122.53 1148.01  115.84 1176.07  103.03 1201.97    86.4 1216.98   81.22
 1279.83   75.43 1301.46    70.5 1330.15   70.08 1358.47   76.21 1379.51   81.13
  1421.6   98.44 1435.63  101.91 1514.16   106.9 1616.04  117.91 1666.84  116.32
 1716.23  119.57 1786.38  111.31 1885.94  104.15 2043.52    99.3 2064.56   96.66
 2079.45   91.58 2137.41   96.75 2166.75    96.8 2219.43  103.06 2398.69  115.92
BR D #Mann= 3
       0      .1 1279.83     .04 1358.47      .1
BC Design=,, 0 ,, 0 ,,,,,,
BC Use User HTab Curves=0
BC User HTab FreeFlow(D)= 0

Type RM Length L Ch R = 1 ,9253.031,689.46,690.02,654.9
BEGIN DESCRIPTION:
End of detailed study.  edited with hec-2 data
END DESCRIPTION:
XS GIS Cut Line= 4
 1617732.7715196   715166.236758 1617107.0267909  714988.7867603
 1615897.5649646  714909.4012351 1615393.2333922  714727.2815006
#Sta/Elev= 30
       0  132.03   86.38  129.25  261.57  131.23  738.64  125.22 1104.37  125.53
 1126.89  122.53 1148.01  115.84 1176.07  103.03 1201.97    86.4 1216.98   81.22
 1279.83   75.43    1315   67.87 1337.42   70.72 1358.47   76.21 1379.51   81.13
  1421.6   98.44 1435.63  101.91 1514.16   106.9 1616.04  117.91 1666.84  116.32
 1716.23  119.57 1786.38  111.31 1885.94  104.15 2043.52    99.3 2064.56   96.66
 2079.45   91.58 2137.41   96.75 2166.75    96.8 2219.43  103.06 2398.69  115.92
#Mann= 3 , 0 , 0
       0      .1       0 1279.83     .04       0 1358.47      .1       0
#XS Ineff= 2 , 0
         1187.83   93.87  1414.3           93.87
Permanent Ineff=
       F       F
Bank Sta=1279.83,1358.47
XS Rating Curve= 0 ,0
Exp/Cntr=0.5,0.3

Type RM Length L Ch R = 1 ,8563.015,1655.15,1549.39,1390.88
BEGIN DESCRIPTION:
not edited with hec-2 data, invert from lidar lower than invert from old profile
END DESCRIPTION:
XS GIS Cut Line= 2
 1617429.6422631  714457.3379722 1615403.5215078  714274.4174813
#Sta/Elev= 30
       0   127.2   98.54  120.36  355.13  108.38  449.96  104.91  490.38  105.35
  569.45  103.12  764.35   91.64  857.62   80.81  909.84    76.2  1031.2   74.94
 1080.16   72.96 1103.61   69.65 1117.67   66.89  1124.7   66.71 1187.95   68.22
 1202.71   69.95 1230.12   73.12 1258.24   71.23 1286.35    72.5 1301.61   74.79
 1336.87   75.46 1370.69   74.01 1384.75   72.02 1405.84   71.84 1415.44   73.73
 1433.95   82.33 1455.04    86.5 1608.84   96.66 1806.46  102.83 2034.36  107.79
#Mann= 3 , 0 , 0
       0      .1       0 1103.61    .045       0 1202.71      .1       0
#XS Ineff= 2 , 0
                         1340.53           75.53
Permanent Ineff=
       F       F
Bank Sta=1103.61,1202.71
XS Rating Curve= 0 ,0
Exp/Cntr=0.3,0.1

Type RM Length L Ch R = 1 ,7013.623,1103.86,1253.09,1136.67
BEGIN DESCRIPTION:
not edited with hec-2 data, invert from lidar lower than invert from old profile
END DESCRIPTION:
XS GIS Cut Line= 4
 1617860.9292634  711760.7044573 1616960.8298714  711948.0424524
 1615738.2906673   713572.802347 1615117.0387158  713925.6816812
#Sta/Elev= 30
       0  108.47  140.37  104.87  374.73  103.66  619.42   95.72  791.02   95.13
   893.6   92.51 1327.42   77.23 1672.09   68.22 1707.13   66.02 1739.05   61.03
 1859.03   62.48 1879.02   60.28 1951.14   63.85 1991.04   62.17 2072.54   64.98
 2119.11   64.77 2128.97   62.95 2148.96   57.95 2171.43   57.88 2188.96   58.82
 2212.25   63.37  2383.1    60.6  2433.9   64.01 2561.52   65.14  2584.8   63.63
 2958.95   72.13 3091.81    76.9 3197.44   83.36 3535.56   95.06  3667.2  102.93
#Mann= 3 , 0 , 0
       0      .1       0 2128.97    .045       0 2212.25      .1       0
Bank Sta=2128.97,2212.25
XS Rating Curve= 0 ,0
Exp/Cntr=0.3,0.1

Type RM Length L Ch R = 1 ,5760.531,1447.02,1409.67,976.59
BEGIN DESCRIPTION:
edited with hec-2 data
END DESCRIPTION:
XS GIS Cut Line= 3
 1616391.9344318  711071.6558903 1614839.3228945  712908.1008717
 1614511.5870879  713705.3874349
#Sta/Elev= 30
       0   82.24  262.74   75.08  372.02    76.1  404.43   71.51  604.74    69.9
  758.53    64.4  872.35   65.89 1179.37   58.47 1309.48   57.73  1355.5   59.02
 1376.07   55.99 1415.98   58.11 1678.11    57.7 1819.06   56.05 1827.37   54.74
 1847.24   50.95    1850   49.17    1865   48.27    1897   49.87 1916.64   54.32
 2164.39    57.4 2202.88   65.71 2232.52    68.6 2339.49      74 2655.54    85.7
 2735.91   92.97 2834.48  104.91 2970.71  109.92 3085.57  117.06 3266.83  123.33
#Mann= 3 , 0 , 0
       0      .1       0 1827.37    .045       0 1916.64      .1       0
Bank Sta=1827.37,1916.64
XS Rating Curve= 0 ,0
Exp/Cntr=0.3,0.1

Type RM Length L Ch R = 1 ,4350.856,349.76,316.22,295.18
BEGIN DESCRIPTION:
edited with hec-2 data
END DESCRIPTION:
XS GIS Cut Line= 2
 1613949.1432356  710940.9032605 1614287.4397224  713475.0137537
#Sta/Elev= 30
       0   69.78  111.58   72.23  255.03   69.59  379.94   64.25  575.16   50.25
  664.34   48.79   697.7   46.07  718.92   48.71   762.9   49.15  865.98   47.97
 1199.43    50.1 1246.03   48.56 1270.95   44.61 1295.88   48.02 1345.72   48.68
    1370   42.06    1404   44.66 1414.43   48.49 1713.31   57.67 1792.36   62.51
 1848.86   69.01 1891.23    70.1 1926.54    74.5 2018.35   76.54 2111.16   81.38
 2180.77   86.85 2289.91  101.31 2435.01  114.31 2484.45  115.01 2556.59  110.48
#Mann= 3 , 0 , 0
       0      .1       0 1246.03    .045       0 1414.43      .1       0
#XS Ineff= 2 , 0
           930.8   61.42
Permanent Ineff=
       F       F
Bank Sta=1246.03,1414.43
XS Rating Curve= 0 ,0
Exp/Cntr=0.5,0.3

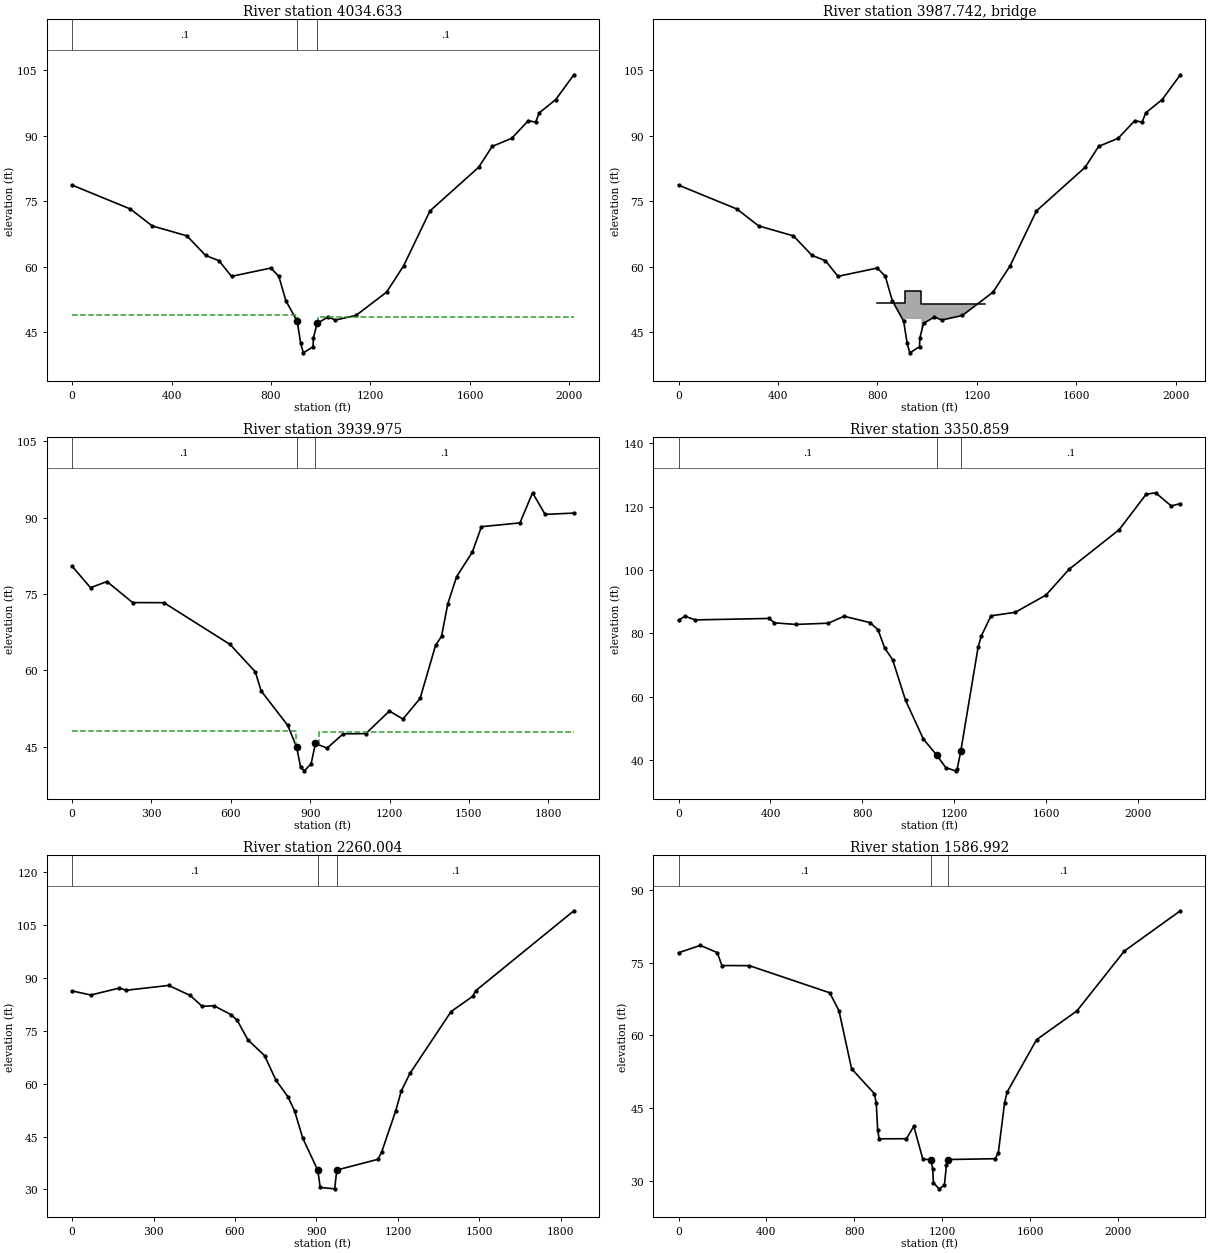
Type RM Length L Ch R = 1 ,4034.633,95.27,94.66,94.83
BEGIN DESCRIPTION:
edited with hec-2 data
END DESCRIPTION:
XS GIS Cut Line= 2
 1613544.9515742  711432.7822014 1614138.0081454  713361.3834921
#Sta/Elev= 30
       0   78.66  234.85   73.18  321.88   69.33   461.9   67.04   537.1   62.55
  590.73   61.37  641.14   57.78  799.46   59.68  831.44   57.78  859.58    52.2
  905.22   47.51  919.33   42.43     930   40.27     969   41.67  970.59   43.72
  985.24   47.01 1029.18   48.47 1058.47   47.77 1141.62   48.83 1264.79   54.17
 1333.28   60.19 1439.29   72.76 1634.93   82.74 1689.38   87.52 1767.78   89.37
 1834.76   93.42 1864.05   93.06  1878.7    95.2 1944.61   98.22 2017.73  103.91
#Mann= 3 , 0 , 0
       0      .1       0  905.22    .045       0  985.24      .1       0
#XS Ineff= 2 , 0
          903.64   48.99  990.23           48.55
Permanent Ineff=
       F       F
Bank Sta=905.22,985.24
XS Rating Curve= 0 ,0
Exp/Cntr=0.5,0.3

Type RM Length L Ch R = 3 ,3987.742,,,
BEGIN DESCRIPTION:
Mechanics Valley Rd
END DESCRIPTION:
Bridge Culvert--1,0,-1,-1, 0
Deck Dist Width WeirC Skew NumUp NumDn MinLoCord MaxHiCord MaxSubmerge Is_Ogee
30,26,2.6,0, 8, 8, , , 0.95, 0, 0,0,,
     800   910.5   910.5   910.5   975.5   975.5   975.5 1230.85
   51.62   51.62    54.5    54.5    54.5    54.5   51.37   51.37
                              48      48
   792.3   857.5   857.5   857.5   922.5   922.5   922.5 1227.85
   51.52   51.62    54.5    54.5    54.5    54.5   51.37   51.37
                              48      48
BR Coef=-1 , 0 , 0 ,, 0 ,,,0.8,0,,0,
WSPro=,,,, 1 ,,,, 0 ,,,, 0 ,,,,-1 ,-1 ,-1 , 0 , 0 , 0 , 0 , 0
BC Design=,, 0 ,, 0 ,,,,,,
BC Use User HTab Curves=0
BC User HTab FreeFlow(D)= 0

Type RM Length L Ch R = 1 ,3939.975,574.68,589.12,614.54
BEGIN DESCRIPTION:
edited with hec-2 data
END DESCRIPTION:
XS GIS Cut Line= 2
 1613474.9055224  711530.8466738 1614035.2739362  713342.7045449
#Sta/Elev= 30
       0   80.46    69.7   76.23  131.76   77.44  228.92   73.31  347.14   73.29
  597.32   65.08  692.58   59.71  714.56   55.97  815.18   49.19  848.38   44.98
     864   40.97     878   40.27   903.6   41.67  919.72   45.66  963.68   44.72
 1024.81   47.54 1110.22   47.57 1199.32   52.02 1250.58   50.44 1315.38   54.49
    1374   64.93  1396.4   66.69 1420.09   73.08 1453.15   78.37 1512.91   83.24
 1547.18   88.21 1692.82   88.96 1740.36   94.87 1787.82   90.63 1896.53   90.88
#Mann= 3 , 0 , 0
       0      .1       0  848.38    .045       0  919.72      .1       0
#XS Ineff= 2 , 0
          847.25   48.02  934.28           47.86
Permanent Ineff=
       F       F
Bank Sta=848.38,919.72
XS Rating Curve= 0 ,0
Exp/Cntr=0.5,0.3

Type RM Length L Ch R = 1 ,3350.859,934.21,1090.85,1115.85
BEGIN DESCRIPTION:
not edited with hec-2 data, invert from lidar lower than invert from old profile
END DESCRIPTION:
XS GIS Cut Line= 3
  1613392.925699  711214.8611516 1613201.9853506  711696.3628997
 1613077.4590364  713356.7137553
#Sta/Elev= 30
       0   84.11   27.58   85.36   72.89    84.2  393.67   84.66  417.25   83.27
  509.52   82.77  651.75   83.16  720.05   85.35     833   83.35   868.1   81.07
  896.36    75.4  931.27   71.64  987.43   58.85 1064.65   46.63 1123.62   41.47
 1162.92   37.52 1205.04   36.54 1212.06   37.03 1227.93   42.79 1303.32   75.61
 1317.35   79.16 1359.47   85.49 1464.77    86.6 1598.14   92.02 1699.54  100.21
 1917.11   112.7 2034.28  123.87 2075.48  124.34 2143.58  120.18 2182.99  120.93
#Mann= 3 , 0 , 0
       0      .1       0 1123.62    .045       0 1227.93      .1       0
Bank Sta=1123.62,1227.93
XS Rating Curve= 0 ,0
Exp/Cntr=0.3,0.1

Type RM Length L Ch R = 1 ,2260.004,661.93,673.01,679.65
BEGIN DESCRIPTION:
edited with hec-2 data
END DESCRIPTION:
XS GIS Cut Line= 3
 1613451.0379789   711015.619049 1612272.1888714  711654.8541283
 1611948.4204546  712045.0365794
#Sta/Elev= 30
       0    86.3   68.87   85.13  174.38   87.11  200.29   86.49  355.53   87.85
  435.16   85.01  479.01   81.93  522.75   82.08  586.45   79.52  608.09   77.95
  647.98   72.38  708.96   67.95  750.78   60.98  794.83   56.32  819.78   52.22
  849.23   44.62  904.97   35.41     914   30.57     967   30.17  974.67   35.23
  976.64   35.54 1126.53   38.54 1139.89   40.53 1191.64   52.21 1212.18   57.87
  1244.2   62.88 1395.93   80.45  1475.2   84.74 1486.16   86.32 1848.03  109.02
#Mann= 3 , 0 , 0
       0      .1       0  904.97    .045       0  976.64      .1       0
Bank Sta=904.97,976.64
XS Rating Curve= 0 ,0
Exp/Cntr=0.3,0.1

Type RM Length L Ch R = 1 ,1586.992,827.7,833.33,888.94
BEGIN DESCRIPTION:
edited with hec-2 data
END DESCRIPTION:
XS GIS Cut Line= 5
 1613517.4520131  710733.3594035 1612488.0344827  710791.4716835
 1612189.1713287  710940.9032605 1611807.2906319   711256.369923
 1611608.0485292  711629.9488655
#Sta/Elev= 30
       0   77.03   99.11   78.54  176.33   77.06  197.27   74.39  322.43   74.36
  688.05   68.77  730.11   65.09  787.69    53.1  891.37   47.97  899.81   46.09
  906.44   40.48  913.08   38.65 1037.44   38.68 1070.79   41.24 1111.62   34.52
 1149.05    34.3 1156.87   32.41    1160   29.64    1185   28.34    1210   29.04
 1219.48    33.3 1227.31   34.39  1441.3   34.55  1455.6    35.8 1483.89   46.05
 1495.37   48.27 1629.62    59.1 1813.25   65.03 2028.99   77.37 2283.92   85.68
#Mann= 3 , 0 , 0
       0      .1       0 1149.05    .045       0 1227.31      .1       0
Bank Sta=1149.05,1227.31
XS Rating Curve= 0 ,0
Exp/Cntr=0.5,0.3

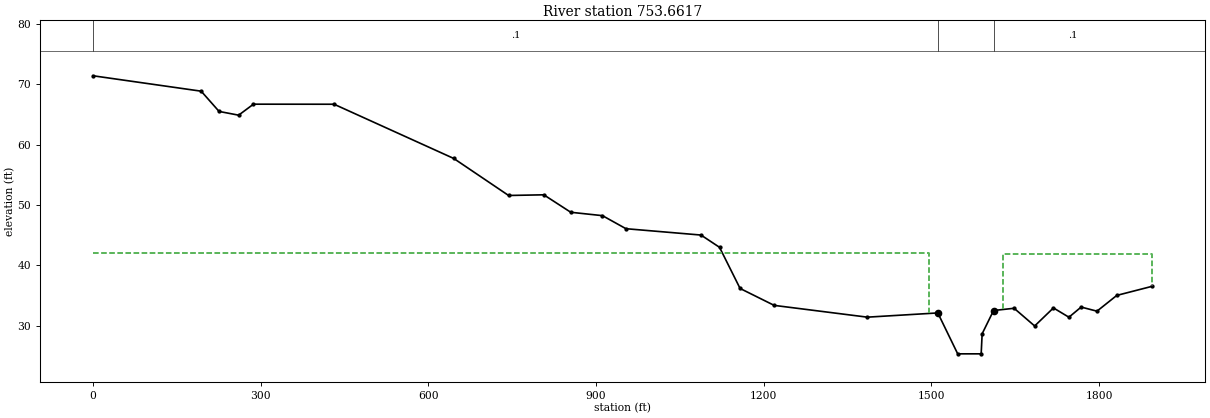
Type RM Length L Ch R = 1 ,753.6617,224.54,226.34,227.88
BEGIN DESCRIPTION:
edited with hec-2 data
END DESCRIPTION:
XS GIS Cut Line= 3
 1613475.9432417  710476.0050209 1612496.3362369  710476.0050209
 1611591.4450207  710334.8751982
#Sta/Elev= 30
       0   71.39  193.43   68.84  225.44   65.49  260.44   64.87  286.95   66.69
   431.2   66.68  645.44    57.7  743.44   51.58  806.44   51.69   854.7    48.8
  911.44   48.24  953.44   46.08 1087.73   45.03 1120.87      43 1157.64   36.19
 1218.63   33.39 1385.29   31.44 1511.42   32.14    1547   25.37    1589   25.37
 1590.74   28.69 1611.17   32.54 1647.94   32.91 1684.71   29.98 1718.27   32.97
    1746   31.43 1767.86   33.11  1796.2   32.43 1831.62   35.04 1895.44   36.56
#Mann= 3 , 0 , 0
       0      .1       0 1511.42     .04       0 1611.17      .1       0
#XS Ineff= 2 , 0
         1495.56   41.98 1628.77           41.91
Permanent Ineff=
       F       F
Bank Sta=1511.42,1611.17
XS Rating Curve= 0 ,0
Exp/Cntr=0.5,0.3