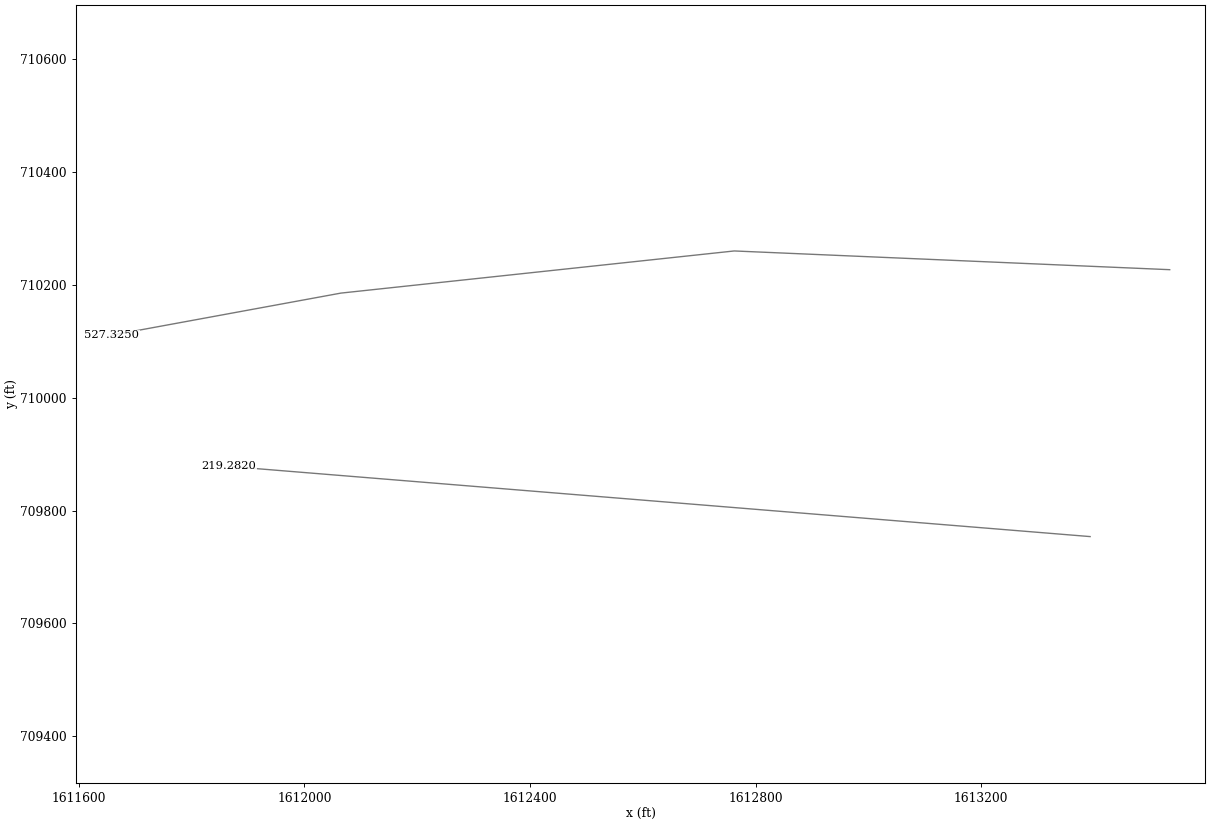
HEC-RAS study LittleNortheast.prj: Little Northeast Creek

--- LittleNortheast.g03 (geometry) --- (continued)

Type RM Length L Ch R = 3 ,671.9841,,,
BEGIN DESCRIPTION:
Hw 40 W Pulaski Hwy
END DESCRIPTION:
Bridge Culvert--1,0,-1,-1, 0
Deck Dist Width WeirC Skew NumUp NumDn MinLoCord MaxHiCord MaxSubmerge Is_Ogee
75,108,2.6,0, 60, 60, , , 0.95, 0, 0,0,,
       0   17.45   48.58  150.77  178.68  227.96  263.04  276.88  307.77  351.68
  368.29  395.54   402.1  466.53  473.54  487.58  494.93  508.63  550.72  571.73
  578.74  606.75  620.76  677.27  683.79  704.62  767.83  813.58  840.14  874.28
  949.92 1083.45  1115.3  1188.9 1195.93 1202.96 1224.05 1231.08 1261.18 1322.46
 1329.49 1343.55 1358.93 1393.52 1427.91 1446.07    1504    1504    1506    1616
    1618    1618 1640.46 1713.03 1740.41 1749.31 1755.88 1763.02    1863    1900
   69.05   69.02   68.19   66.35   65.32   64.55    63.3    63.2   62.16   61.17
   61.13   59.87   59.98      58    58.1   57.85    57.4    57.3   55.78   55.36
    55.5   54.49    54.5   52.94   52.55   52.39    50.5   49.69   48.91   48.57
      47   45.39   45.45   44.81   45.05   44.74   44.56   44.83   44.24   43.87
   44.09   43.54    43.7   43.11   43.06   42.72   42.75   45.99   45.99   45.99
   45.99    42.5   42.01   42.05   41.77   42.03   41.76   41.98   41.55   41.57
                                                                                
                                                                                
                                                                                
                                                                                
                                                                   40.49   40.49
                                                                                
       0   17.45   48.58  150.77  178.68  227.96  263.04  276.88  307.77  351.68
  368.29  395.54   402.1  466.53  473.54  487.58  494.93  508.63  550.72  571.73
  578.74  606.75  620.76  677.27  683.79  704.62  767.83  813.58  840.14  874.28
  949.92 1083.45  1115.3  1188.9 1195.93 1202.96 1215.44 1224.05 1231.08 1261.18
 1322.46 1329.49 1343.55 1358.93 1393.52 1427.91 1438.56    1555    1555    1557
    1667    1669    1669 1713.03 1740.41 1749.31 1755.88 1763.02    1863    1900
   69.05   69.02   68.19   66.35   65.32   64.55    63.3    63.2   62.16   61.17
   61.13   59.87   59.98      58    58.1   57.85    57.4    57.3   55.78   55.36
    55.5   54.49    54.5   52.94   52.55   52.39    50.5   49.69   48.91   48.57
      47   45.39   45.45   44.81   45.05   44.74   44.88   44.56   44.83   44.24
   43.87   44.09   43.54    43.7   43.11   43.06   42.74    42.5   45.99   45.99
   45.99   45.99      42   42.05   41.77   42.03   41.76   41.98   41.55   41.57
                                                                                
                                                                                
                                                                                
                                                                                
                                                                           40.49
   40.49
Pier Skew, UpSta & Num, DnSta & Num=  ,1541, 2 ,1592, 2 , 0 , 0 , 0 ,,
       3       3
      25      44
       3       3
      25      44
Pier Skew, UpSta & Num, DnSta & Num=  ,1581, 2 ,1632, 2 , 0 , 0 , 0 ,,
       3       3
      25      44
       3       3
      25      44
BR Coef=-1 , 1 , 0 ,, 0 ,,,0.8,0,1.33,0,
WSPro=,,,, 1 ,,,, 0 ,,,, 0 ,,,,-1 ,-1 ,-1 , 0 , 0 , 0 , 0 , 0
BC Design=,, 0 ,, 0 ,,,,,,
BC Use User HTab Curves=0
BC User HTab FreeFlow(D)= 0

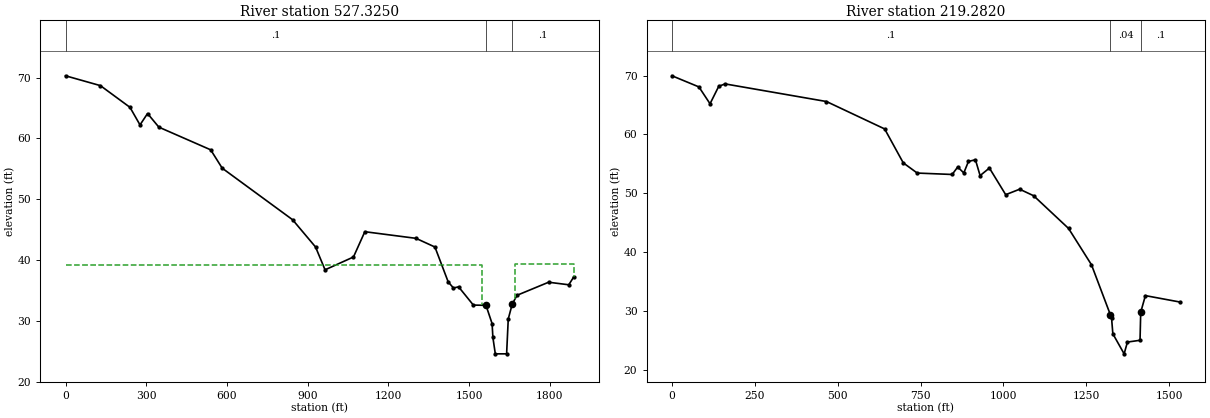
Type RM Length L Ch R = 1 ,527.3250,317.6,308.04,291.17
BEGIN DESCRIPTION:
edited with hec-2 data
END DESCRIPTION:
XS GIS Cut Line= 4
 1613534.0555217  710226.9523925 1612761.9923738  710260.1594097
 1612064.6450145  710185.4436212 1611657.8590549  710110.7278327
#Sta/Elev= 30
       0   70.31  129.68   68.69  239.52   65.12  276.81   62.23  304.84    64.1
  346.88   61.86  539.42   58.13  582.25   55.11  843.77   46.63  929.16   42.14
  964.36   38.39 1069.96    40.5  1112.2   44.66 1302.28   43.57 1372.68   42.14
 1421.96    36.4 1441.49    35.4 1460.57   35.59 1515.42   32.59 1562.37   32.55
 1585.09   29.54    1588   27.27    1597   24.57    1639   24.57  1645.1    30.3
 1659.67   32.73 1677.61    34.2 1795.02   36.35 1869.99   35.93 1887.71   37.17
#Mann= 3 , 0 , 0
       0      .1       0 1562.37     .04       0 1659.67      .1       0
#XS Ineff= 2 , 0
         1547.07   39.16 1669.63           39.39
Permanent Ineff=
       F       F
Bank Sta=1562.37,1659.67
XS Rating Curve= 0 ,0
Exp/Cntr=0.5,0.3

Type RM Length L Ch R = 1 ,219.2820,203.44,219.28,73.95
BEGIN DESCRIPTION:
edited with hec-2 data
END DESCRIPTION:
XS GIS Cut Line= 2
  1613392.925699  709753.7523987 1611865.4029118  709878.2787129
#Sta/Elev= 30
       0   69.96   81.27   68.07  114.81   65.21  141.17   68.18  160.23   68.58
  466.09   65.59  641.55   60.94  697.73   55.18  739.87   53.45  845.22   53.21
  861.99   54.48  880.34   53.47  894.38   55.42  915.45   55.71   929.5   53.02
  957.59    54.3 1006.75   49.78 1048.89   50.71 1091.03    49.6 1196.38   44.05
 1265.57   37.88 1322.66   29.38 1326.09   28.85    1330   26.17    1364   22.77
    1374   24.77    1412   25.07 1414.03   29.83 1428.15   32.65 1532.59   31.56
#Mann= 3 , 0 , 0
       0      .1       0 1322.66     .04       0 1414.03      .1       0
Bank Sta=1322.66,1414.03
XS Rating Curve= 0 ,0
Exp/Cntr=0.3,0.1

Chan Stop Cuts=-1
Use User Specified Reach Order=0
User Specified Reach Order=Little NE Creek ,Upper