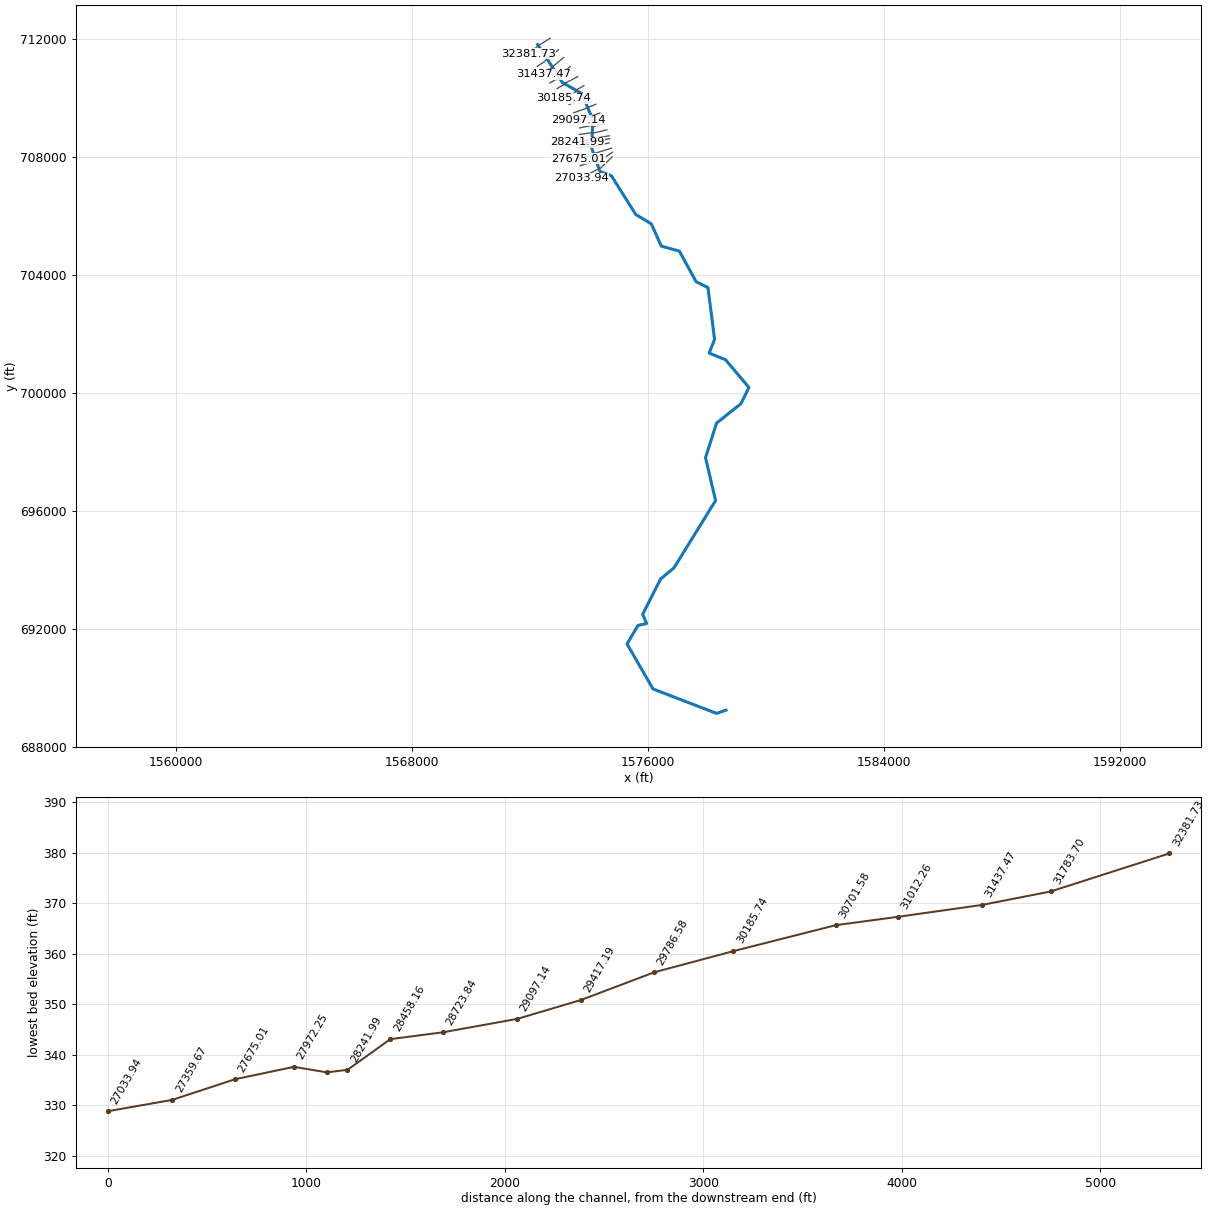
--- MillCreek.prj (project) ---

Proj Title=MillCreek
Current Plan=p01
Default Exp/Contr=0.3,0.1
English Units
Geom File=g01
Flow File=f01
Flow File=f02
Plan File=p01
Plan File=p02
Y Axis Title=Elevation
X Axis Title(PF)=Main Channel Distance
X Axis Title(XS)=Station
BEGIN DESCRIPTION:
Mill Creek (Perryville, Maryland and upstream unincorporated area) - Georeferenced HEC-RAS model.  MD Stateplane.  Horizontal Datum: NAD83.  Vertical Datum: NAVD88.  Units: Feet.  Created by: Jodell Kormanik-Sonterre, USACE - St. Paul District as part of FEMA Map Modernization study for Cecil County, MD.
END DESCRIPTION:
DSS Export Rating Curves= 0
DSS Export Rating Curve Sorted= 0
DSS Export Volume Flow Curves= 0
DXF OffsetX= 0
DXF OffsetY= 0
DXF ScaleX= 1
DXF ScaleY= 10

--- MillCreek.p01 (plan) ---

Plan Title=Mill Creek frequency profiles
Program Version=4.00
Short Identifier=freq
Geom File=g01
Flow File=f01
Subcritical Flow
K Sum by GR= 0
Std Step Tol= 0.01
Critical Tol= 0.01
Num of Std Step Trials= 20
Max Error Tol= 0.3
Flow Tol Ratio= 0.001
Split Flow NTrial= 30
Split Flow Tol= 0.02
Split Flow Ratio= 0.02
Log Output Level= 0
Friction Slope Method= 1
Unsteady Friction Slope Method= 2
Unsteady Bridges Friction Slope Method= 1
Parabolic Critical Depth
Global Vel Dist= 0 , 0 , 0
Global Log Level= 0
CheckData=True
Encroach Param=-1 ,0,0, 0
Computation Interval=1HOUR
Output Interval=1HOUR
Run HTab= 0
Run UNet= 0
Run PostProcess= 0
Run WQNet= 0
UNET Theta= 1
UNET Theta Warmup= 1
UNET ZTol= 0.02
UNET ZSATol= 0.05
UNET MxIter= 20
UNET MaxInSteps= 0
UNET DtIC= 0
UNET DtMin= 0
UNET MaxCRTS= 20
UNET WFStab= 2
UNET SFStab= 1
UNET WFX= 1
UNET SFX= 1
UNET DSS MLevel= 4
UNET DZMax Abort= 100
UNET Convert EG Bridges= 0
UNET Use Existing IB Tables=-1
UNET Froude Reduction=False
UNET Froude Limit= 1
UNET Froude Power= 10
UNET Time Slicing=0,0, 5
Instantaneous Interval=1HOUR
Write IC File= 0
Echo Input=False
Echo Output=False
Write Detailed= 0
Detailed Automatic Start=False, 10
WQ ULTIMATE=-1
WQ Max Comp Step=1HOUR
WQ Output Interval=15MIN
WQ Output Selected Increments= 0
WQ Output face flow=0
WQ Output face velocity=0
WQ Output face area=0
WQ Output face dispersion=0
WQ Output cell volume=0
WQ Output cell surface area=0
WQ Output cell continuity=0
WQ Output face conc=0
WQ Output face dconc_dx=0
WQ Output face courant=0
WQ Output face peclet=0
WQ Output face adv mass=0
WQ Output face disp mass=0
WQ Output cell mass=0
WQ Output cell source sink temp=0
WQ Output cell source sink nsm=0
WQ Output MaxMinRange=-1
WQ Daily Max Min Mean=-1
WQ Daily Range=0
WQ Daily Time=0
WQ Create Restart=0
WQ Fixed Restart=0
WQ System Summary=False
Sorting and Armoring Iterations= 10
XS Update Threshold= 0.02
Hydraulics Update Threshold= 0.02
Energy Slope Method= 1
Volume Change Method= 0
XS Weighting Method= 0
Number of US Weighted Cross Sections= 1
Number of DS Weighted Cross Sections= 1
Upstream XS Weight=0.25
Main XS Weight=0.5
Downstream XS Weight=0.25
Number of DS XS's Weighted with US Boundary= 1
Upstream Boundary Weight= 1
Weight of XSs Associated with US Boundary= 0
Number of US XS's Weighted with DS Boundary= 1
Downstream Boundary Weight= 0.5
Weight of XSs Associated with DS Boundary= 0.5
Sediment Output Level= 4
Mass or Volume Output= 0
Output Increment Type= 1
Profile and TS Output Increment= 10
XS Output Flag= 0
XS Output Increment= 10
Disregard all LS=0
Disregard all Conn=0
Disregard all Breaches=0
Disregard all Pumps=0

--- MillCreek.p02 (plan) ---

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Plan Title=Mill Creek floodway
Short Identifier=floodway
Geom File=g01
Flow File=f02
Encroach Param=-1 ,0,0, 2
Encroach River=Mill Creek
Encroach Reach=Unincorporated
Encroach Node=22785.93
       1     310     490
Encroach Node=22597.68
       1     485     651
Encroach Node=22497.19
       1     550     665
Encroach Node=22396.14
       1     320     425
Encroach Node=22325.40
       1     320     415
Encroach Node=21755.04
       1     825     890
Encroach Node=21347.99
       1     750     800
Encroach Node=21255.14
       1     490     540
Encroach Node=21204.46
       1     490     550
Encroach Node=20849.09
       1     460     565
Encroach Node=20648.28
       1     320     440
Encroach Node=20578.42
       1   311.8  405.87
Encroach Node=20268.57
       1  343.17  399.89
Encroach Node=19925.94
       1  483.22  513.29
Encroach Node=19506.85
       1  754.34  817.43
Encroach Node=18962.52
       1     789  886.96
Encroach Node=18343.44
       1     715     765
Encroach Node=17579.25
       1     460     530
Encroach Node=17386.73
       1     490     695
Encroach Node=17197.16
       1     440     650
Encroach Node=17117.46
       1     475     575
Encroach Node=16856.24
       1     580     725
Encroach Node=16746.56
       1     490     575
Encroach Node=16416.39
       1     340     425
Encroach Node=15687.49
       1     590     675
Encroach Node=14704.89
       1     580     680
Encroach Node=13540.72
       1     630     920
Encroach Node=12126.52
       1    1125    1435
Encroach Node=11951.65
       1     805     930
Encroach Node=11767.99
       1  779.81  862.31
Encroach Node=11567.82
       1     780     860
Encroach Node=11276.75
       1     610    1385
Encroach Node=10848.27
       1     765    1220
Encroach Node=10126.31
       1     450     900
Encroach Node=9651.695
       1     400     735
Encroach Node=9288.987
       1    1100    1300
Encroach Node=8348.613
       1     800    1280
Encroach Node=8020.921
       1     580     970
Encroach Node=7878.745
       1     765    1085
Encroach Node=7659.476
       1  576.84     885
Encroach Node=7468.421
       1     560     835
Encroach Node=7068.937
       1  542.61  850.96
Encroach Node=6300.701
       1     870 1140.08
Encroach Node=6038.382
       1     820    1140
Encroach Node=5370.580
       1     900    1075
Encroach Node=5143.526
       1     985    1230
Encroach Node=4920.064
       1     800    1000
Encroach Node=4762.096
       1    1100    1370
Encroach Node=4441.342
       1     980    1285
Encroach Node=4078.491
       1    1900    2100
Encroach Node=3870.823
       1    1800    2100
Encroach Node=3710.443
       1    1700    2150
Encroach Node=3131.528
       1     600     850
Encroach Node=3031.046
       1     590     890
Encroach Node=2936.614
       1     590     900
Encroach Node=2660.046
       1     500     810
Encroach Node=2583.904
       1     475  766.88
Encroach Node=2349.426
       1     310  529.88
Encroach Node=1359.639
       1     700  856.49
Encroach Node=808.8627
       1   556.5   765.3
Encroach Node=144.4616
       1  692.27 1191.49

--- MillCreek.f01 (steady flow) ---

Flow Title=Mill Creek frequency flows
Program Version=4.00
Number of Profiles= 5
Profile Names=10yr,50yr,100yr,500yr,100ult
River Rch & RM=Mill Creek,Unincorporated  ,32381.73
     545    1160    1540    2820    1660
River Rch & RM=Mill Creek,Unincorporated  ,28458.16
     645    1390    1850    3440    2010
River Rch & RM=Mill Creek,Unincorporated  ,27675.01
     693    1510    2040    3860    2220
River Rch & RM=Mill Creek,Unincorporated  ,24902.61
     765    1680    2260    4290    2480
River Rch & RM=Mill Creek,Unincorporated  ,24451.10
     808    1770    2390    4560    2600
River Rch & RM=Mill Creek,Unincorporated  ,19506.85
     890    1976    2687    5190    3033
River Rch & RM=Mill Creek,Unincorporated  ,18962.52
     907    2064    2825    5550    3182
River Rch & RM=Mill Creek,Unincorporated  ,15687.49
     982    2322    3220    6505    3579
River Rch & RM=Mill Creek,Unincorporated  ,13540.72
    1029    2466    3421    6920    3779
River Rch & RM=Mill Creek,Unincorporated  ,6300.701
    1099    2675    3726    7588    4091
River Rch & RM=Mill Creek,Unincorporated  ,5370.580
    1314    3203    4442    8969    4798
River Rch & RM=Mill Creek,Unincorporated  ,3710.443
    1377    3373    4676    9419    5006
River Rch & RM=Mill Creek,Unincorporated  ,144.4616
    1491    3674    5094   10284    5385
Boundary for River Rch & Prof#=Mill Creek,Unincorporated  , 1
Up Type= 0
Dn Type= 3
Dn Slope=0.0025
Boundary for River Rch & Prof#=Mill Creek,Unincorporated  , 2
Up Type= 0
Dn Type= 3
Dn Slope=0.0025
Boundary for River Rch & Prof#=Mill Creek,Unincorporated  , 3
Up Type= 0
Dn Type= 3
Dn Slope=0.0025
Boundary for River Rch & Prof#=Mill Creek,Unincorporated  , 4
Up Type= 0
Dn Type= 3
Dn Slope=0.0025
Boundary for River Rch & Prof#=Mill Creek,Unincorporated  , 5
Up Type= 0
Dn Type= 3
Dn Slope=0.0025
DSS Import GetInterval= 0
DSS Import GetPeak= 0
DSS Import FillOption= 0

--- MillCreek.f02 (steady flow) ---

Flow Title=Mill Creek  Floodway Flows
Program Version=4.00
Number of Profiles= 2
Profile Names=100yr,100fldwy
River Rch & RM=Mill Creek,Unincorporated  ,32381.73
    1540    1540
River Rch & RM=Mill Creek,Unincorporated  ,28458.16
    1850    1850
River Rch & RM=Mill Creek,Unincorporated  ,27675.01
    2040    2040
River Rch & RM=Mill Creek,Unincorporated  ,24902.61
    2260    2260
River Rch & RM=Mill Creek,Unincorporated  ,24451.10
    2390    2390
River Rch & RM=Mill Creek,Unincorporated  ,19506.85
    2687    2687
River Rch & RM=Mill Creek,Unincorporated  ,18962.52
    2825    2825
River Rch & RM=Mill Creek,Unincorporated  ,15687.49
    3220    3220
River Rch & RM=Mill Creek,Unincorporated  ,13540.72
    3421    3421
River Rch & RM=Mill Creek,Unincorporated  ,6300.701
    3726    3726
River Rch & RM=Mill Creek,Unincorporated  ,5370.580
    4442    4442
River Rch & RM=Mill Creek,Unincorporated  ,3710.443
    4676    4676
River Rch & RM=Mill Creek,Unincorporated  ,144.4616
    5094    5094
Boundary for River Rch & Prof#=Mill Creek,Unincorporated  , 1
Up Type= 0
Dn Type= 3
Dn Slope=0.0025
Boundary for River Rch & Prof#=Mill Creek,Unincorporated  , 2
Up Type= 0
Dn Type= 1
Dn Known WS=4.15
DSS Import GetInterval= 0
DSS Import GetPeak= 0
DSS Import FillOption= 0

--- MillCreek.g01 (geometry) ---

Geom Title=Mill Creek Geometry
Program Version=4.00

River Reach=Mill Creek      ,Unincorporated
Reach XY= 30
1572264.96894325711823.4614938351573105.82002355710531.820806608
1573759.81530821710160.4449128061574135.86259691709270.544186175
1574098.49143779708305.9011413011574380.03944549707513.566068202
1574763.95585898707374.8239979741575592.39845443706058.899469286
1576117.69292387705743.4975567761576458.40648128704986.362916201
1577071.07210201704816.2325517981577636.13017569703781.240982607
1578039.24223545 703582.575642721578263.43239881701823.484399438
1578080.16340835701359.8472033741578632.18723872701137.336165443
1579427.61478172700195.8547807041579159.79379502699644.296500623
1578331.07235539698987.1117913571577956.77028246697813.968796432
 1578298.1977492696360.5058241191576886.76487656694076.404093117
 1576433.8688007693700.4914591011575824.74862787692499.298651531
1575960.52066603692192.9751171921575664.47270174692122.959837273
1575295.99738881691495.7376665321576176.70658538689971.364074856
1578330.62747434689143.5924364481578652.18654254689253.312033281

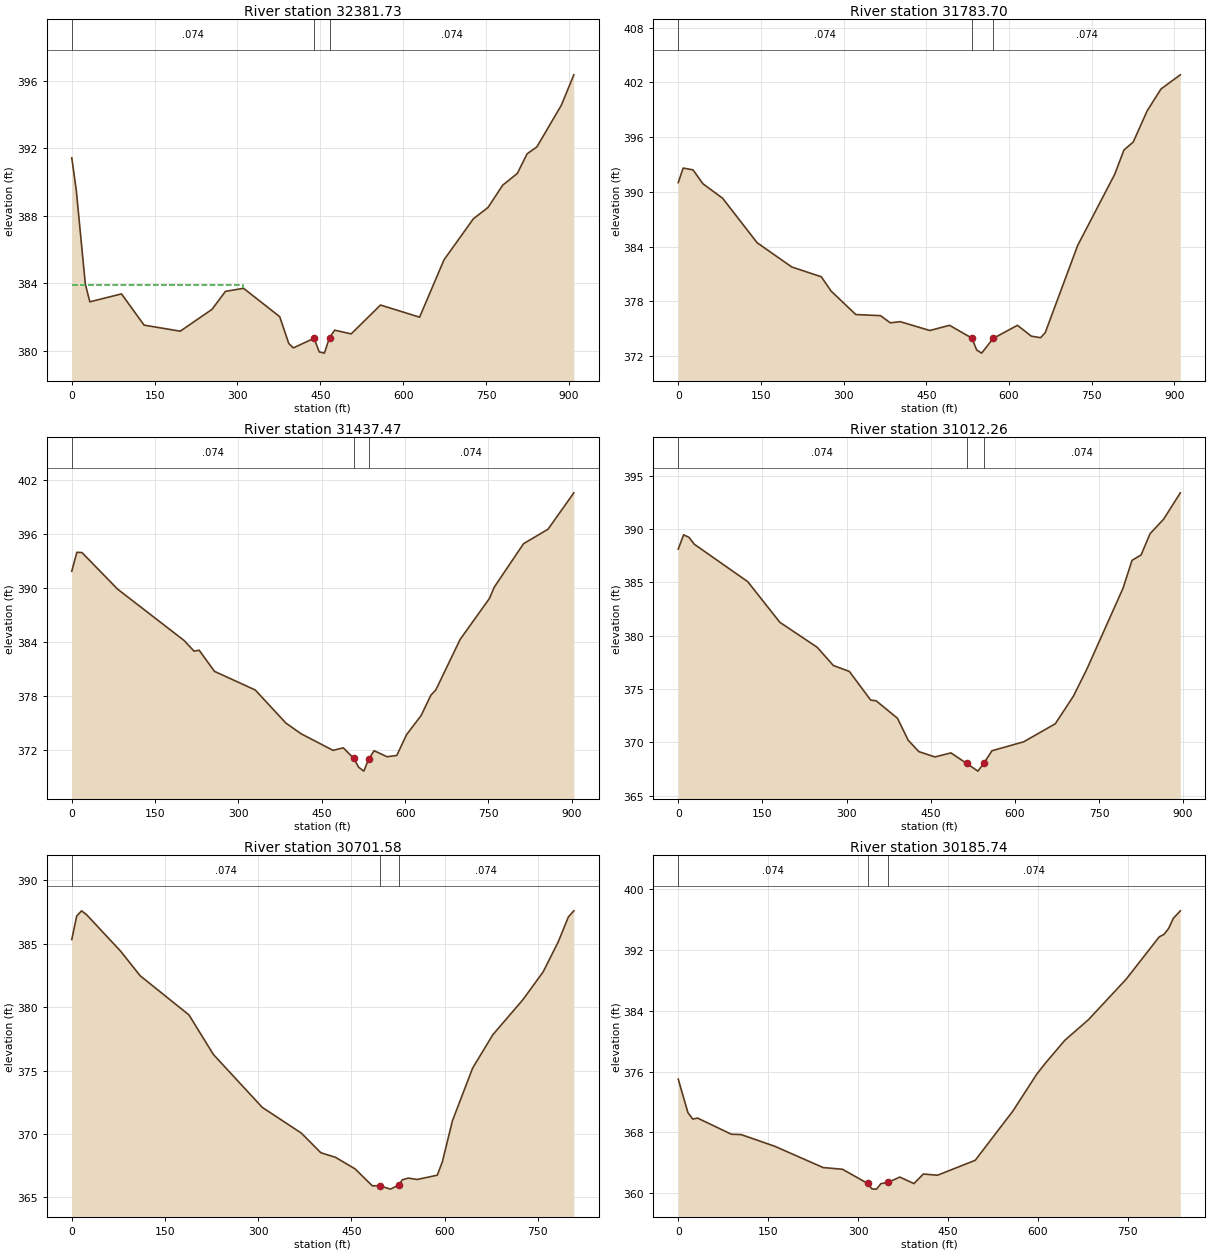
Type RM Length L Ch R = 1 ,32381.73,535.56,598.03,559.71
XS GIS Cut Line= 4
1572687.32044534712032.0533181731572312.09247866711804.725425959
1572268.27023436711766.3809622231571942.34229255711514.403057605
#Sta/Elev= 30
       0  391.43    8.18  389.51   24.55  383.95   32.74   382.9   90.03  383.37
  130.95  381.52  196.43  381.16  253.72  382.45  278.27  383.52  311.01   383.7
  376.48  382.02  392.85  380.43  401.04  380.17  438.72  380.74  448.02  379.93
  457.32  379.86  466.62  380.78  475.92  381.22   505.8     381  558.88  382.71
  629.67  381.99  673.91  385.39     727  387.82  753.54  388.49  780.09  389.81
  806.63  390.51  824.33  391.67  842.02  392.08  886.26  394.55  908.92  396.35
#Mann= 3 , 0 , 0
       0    .074       0  438.72    .045       0  466.62    .074       0
#XS Ineff= 2 , 0
          310.85   383.9
Permanent Ineff=
       F       F
Bank Sta=438.72,466.62
XS Rating Curve= 0 ,0
Exp/Cntr=0.3,0.1

Type RM Length L Ch R = 1 ,31783.70,327.51,346.23,314.23
XS GIS Cut Line= 4
1572966.68725263711640.3920099141572564.07038328711319.941848576
1572512.03146818711254.2084821611572251.83689277 711081.65839529
#Sta/Elev= 30
       0  391.01    8.95  392.61   26.84  392.41   44.73  390.89   80.52   389.3
  143.14  384.42  205.77  381.77  259.45  380.69  277.34  379.12  322.08  376.55
  366.81  376.43   384.7  375.64   402.6  375.77  456.27   374.8  492.06  375.37
  532.43  373.97  541.36  372.66  550.29  372.32  571.23  373.93  615.21  375.37
  640.41  374.18  657.21  374.01  665.61  374.56  724.41  384.12   791.6  391.92
   808.4  394.59   825.2  395.46   850.4  398.87  875.59  401.28  910.62  402.83
#Mann= 3 , 0 , 0
       0    .074       0  532.43    .045       0  571.23    .074       0
Bank Sta=532.43,571.23
XS Rating Curve= 0 ,0
Exp/Cntr=0.3,0.1

Type RM Length L Ch R = 1 ,31437.47,393.04,425.21,410.45
XS GIS Cut Line= 4
1573147.45401029711382.9363247451572788.65938525 711078.91950503
1572728.40379936711026.880589962 1572446.2981018 710813.24714908
#Sta/Elev= 30
       0  391.88    9.17  393.98   18.35  393.95   82.57  389.88  201.85  384.19
   220.2  382.99  229.37  383.09   256.9  380.74   330.3  378.67  385.35     375
  412.87   373.8  470.28  371.96  488.77  372.24  507.27  371.09  516.52  370.08
  525.77  369.65  534.21  370.97  544.27  371.92  567.45  371.25  585.02  371.39
  602.58   373.7  628.92  375.84  646.48   378.1  655.26  378.67  699.16   384.3
  751.85  388.85  760.63  390.12  813.31  394.94  857.22  396.54  903.76  400.59
#Mann= 3 , 0 , 0
       0    .074       0  507.27    .045       0  534.21    .074       0
Bank Sta=507.27,534.21
XS Rating Curve= 0 ,0
Exp/Cntr=0.3,0.1

Type RM Length L Ch R = 1 ,31012.26,320.53,310.68,286.63
XS GIS Cut Line= 4
1573366.56523168 711078.919505031573005.03171636 710744.77489239
1572963.94836235 710681.780416221572679.10377449710520.185890436
#Sta/Elev= 30
       0  388.11    9.53  389.45   19.06  389.22    28.6  388.57  123.91  385.06
  181.11  381.25  247.83   378.9  276.42   377.2  305.02  376.64  343.15  373.95
  352.68  373.89  390.81  372.25  409.87  370.19  428.94  369.12  457.53  368.62
  486.13     369     514  368.02  534.09  367.29  545.32  368.06  559.16   369.2
   615.8  370.04  672.13  371.73  704.32  374.31  728.47  376.86  792.85  384.44
  808.95  387.06  825.04  387.56  841.14  389.56  865.28  390.92     895  393.39
#Mann= 3 , 0 , 0
       0    .074       0     514    .045       0  545.32    .074       0
Bank Sta=514,545.32
XS Rating Curve= 0 ,0
Exp/Cntr=0.3,0.1

Type RM Length L Ch R = 1 ,30701.58,475,515.84,480.79
XS GIS Cut Line= 4
1573621.28202659710731.0804410431573207.70959617710520.185890436
1573150.19290057710459.9303045421572925.60389861710328.463571697
#Sta/Elev= 30
       0  385.33    7.86  387.18   15.72   387.6   23.57  387.31   78.58  384.42
  110.01  382.48  188.58  379.39  227.87  376.27  306.45   372.1  369.31  370.07
  400.74  368.52  424.31  368.16  455.74  367.25  483.59  365.91  495.25  365.92
  512.63  365.65  526.02  365.97  531.98  366.39  541.66  366.52  555.65  366.41
   588.1  366.75  596.21   367.8  612.43  371.04  644.87  375.19  677.32  377.82
  725.98   380.6  758.43  382.79  782.76  385.16  798.98  387.12  807.78   387.6
#Mann= 3 , 0 , 0
       0    .074       0  495.25    .045       0  526.02    .074       0
Bank Sta=495.25,526.02
XS Rating Curve= 0 ,0
Exp/Cntr=0.3,0.1

Type RM Length L Ch R = 1 ,30185.74,356.61,399.16,347.85
XS GIS Cut Line= 4
 1573832.1765772710427.0636213421573577.45978229710281.902437165
1573550.07087964  710210.69129021573133.75955893709997.057849318
#Sta/Elev= 30
       0     375   16.11   370.6   24.17  369.74   32.23  369.87   88.63  367.74
  104.74   367.7  161.14  366.15  241.71  363.35  273.94  363.13  315.68  361.27
  323.18  360.53  330.68  360.51  338.18  361.24  350.03  361.39  369.47   362.1
  393.08  361.24  408.81   362.5  432.42  362.34  495.36  364.31   558.3  370.81
  597.64  375.62  613.38   377.2  644.85  380.12  684.19  382.83  747.13  388.17
  802.21  393.74  810.07  394.06  817.94  394.85  825.81  396.19   837.4  397.17
#Mann= 3 , 0 , 0
       0    .074       0  315.68    .045       0  350.03    .074       0
Bank Sta=315.68,350.03
XS Rating Curve= 0 ,0
Exp/Cntr=0.3,0.1

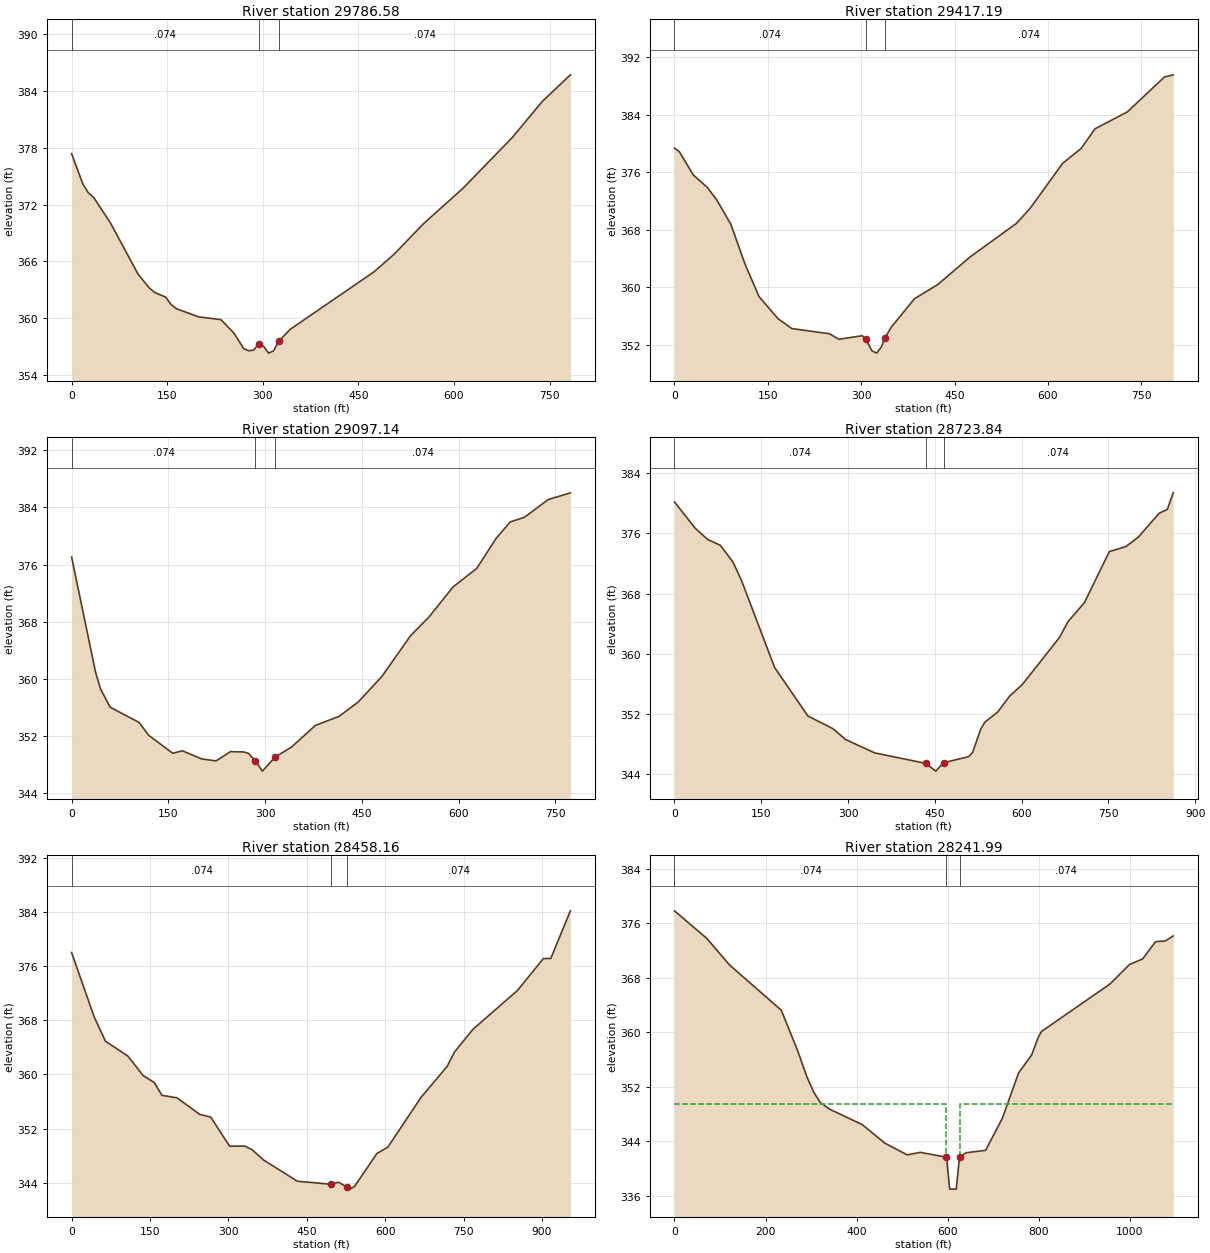
Type RM Length L Ch R = 1 ,29786.58,390.65,369.39,359.64
XS GIS Cut Line= 4
1574015.68222514710164.1301556381573810.26545505710013.491190925
1573730.83763729709975.1467271891573333.69854851709786.163298711
#Sta/Elev= 30
       0   377.4   17.36  374.24   26.04  373.28   34.72  372.75   60.76   370.1
  104.17  364.67  121.53  363.23  130.21  362.73  147.57  362.23  156.25  361.44
  164.93  360.99  199.65  360.14  234.37  359.85  254.73  358.43  270.28  356.77
  278.05  356.56  285.82  356.63   293.6  357.31  301.37  357.03  309.14  356.31
  316.92  356.55  324.69  357.54  342.93  358.82  474.72  364.91  505.73  366.74
  552.24  369.99  614.26  373.74  691.78  379.12  738.29  382.89  782.74  385.73
#Mann= 3 , 0 , 0
       0    .074       0   293.6    .045       0  324.69    .074       0
Bank Sta=293.6,324.69
XS Rating Curve= 0 ,0
Exp/Cntr=0.3,0.1

Type RM Length L Ch R = 1 ,29417.19,321.57,320.05,296.81
XS GIS Cut Line= 4
1574240.27122705709797.1188597831573974.59887113709690.302139342
 1573897.9099436709654.6965658521573492.55418402709509.535381675
#Sta/Elev= 30
       0  379.36    7.54  378.91   30.18  375.64   52.81  373.89    67.9  372.16
   90.54  368.78  113.17  363.26   135.8  358.71  165.98  355.65  188.62  354.24
  248.97  353.52  264.06  352.75  301.78  353.24  307.52  352.75  317.21  351.15
  324.93  350.82  332.65  351.71  337.81  352.88  348.08   354.4  385.76   358.4
  422.94  360.36  474.99  364.21  549.34  368.87  571.65     371  623.69  377.24
  653.43  379.32  675.74  382.05  727.79  384.41  787.27  389.27  801.46  389.57
#Mann= 3 , 0 , 0
       0    .074       0  307.52    .045       0  337.81    .074       0
Bank Sta=307.52,337.81
XS Rating Curve= 0 ,0
Exp/Cntr=0.3,0.1

Type RM Length L Ch R = 1 ,29097.14,367.25,373.3,313.13
XS GIS Cut Line= 4
1574371.73795991709498.5798206031574127.97672607 709408.19644177
1574048.54890832709391.7631001621573637.71536818709257.557477057
#Sta/Elev= 30
       0  377.05   37.33  360.87   44.79  358.61   59.73  356.04  104.52  353.91
  119.45  352.11  156.78  349.59  171.71  349.94  201.57   348.8  223.97  348.52
  246.37  349.82  267.13  349.77  274.27  349.57  285.03  348.52  295.72  347.09
  315.42  349.05  341.09  350.47  377.91  353.48  414.73  354.76  444.18  356.75
     481  360.33  525.19  366.01  554.64  368.72  591.46  372.88  628.28  375.48
  657.74  379.61  679.83  381.96  701.92  382.61  738.75  385.09  773.29  386.04
#Mann= 3 , 0 , 0
       0    .074       0  285.03    .045       0  315.42    .074       0
Bank Sta=285.03,315.42
XS Rating Curve= 0 ,0
Exp/Cntr=0.3,0.1

Type RM Length L Ch R = 1 ,28723.84,226.02,265.68,238.03
XS GIS Cut Line= 4
1574525.11581491709137.0463052841574125.23783584709038.446255654
1574059.50446939709074.0518291151573692.49317355708994.624011353
#Sta/Elev= 30
       0  380.15   36.05  376.65   57.68  375.16   79.31   374.4  100.94   372.2
  115.35  369.84  173.03   358.2  230.71  351.75  273.97  350.07   295.6  348.64
  346.06  346.86  434.25  345.47  451.66  344.44   465.2  345.56   508.1  346.35
  515.26   346.9  529.58  350.05  536.75  350.96  558.23  352.24  579.72  354.42
   601.2  355.92  665.66  362.19  679.99  364.25  708.64   366.8  751.61  373.56
  780.26  374.23  801.74  375.48  837.55  378.64  851.88  379.16  862.12  381.36
#Mann= 3 , 0 , 0
       0    .074       0  434.25    .045       0   465.2    .074       0
Bank Sta=434.25,465.2
XS Rating Curve= 0 ,0
Exp/Cntr=0.3,0.1

Type RM Length L Ch R = 1 ,28458.16,191.24,216.18,222.96
XS GIS Cut Line= 4
1574610.02141322708928.8906449531574141.67117743708816.596143976
1574084.15448183708833.0294855831573676.05983198708770.035009414
#Sta/Elev= 30
       0  377.99   43.19  368.49   64.79  364.91  107.98  362.69  136.77  359.84
  158.36  358.79  172.76  356.92  201.56  356.55  244.75  354.13  266.34   353.7
  302.33  349.41  331.13  349.43  345.52  348.89  367.12  347.39   431.9  344.25
  496.94343.7921  510.74   344.1  527.29  343.35  532.59  343.08  541.44  343.48
  583.94  348.32  605.19  349.29  668.93  356.65  718.51  361.18  732.68  363.32
  768.09  366.67  853.09  372.39  902.67   377.1  916.84  377.11  954.37  384.14
#Mann= 3 , 0 , 0
       0    .074       0  496.94    .045       0  527.29    .074       0
Bank Sta=496.94,527.29
XS Rating Curve= 0 ,0
Exp/Cntr=0.5,0.3

Type RM Length L Ch R = 1 ,28241.99,100.04,103.58,102.88
XS GIS Cut Line= 4
1574691.18846203708727.9296536741574223.14231876708644.984767511
1574005.49178173708595.5187363921573617.63420704708510.859468803
#Sta/Elev= 30
       0  377.86   71.09  373.81  120.85  369.92   234.6  363.27  270.14   357.4
  291.47  353.39  305.69  351.27  319.91  349.74  341.24  348.72  412.33  346.48
  462.09  343.75  511.23  342.03  539.95   342.4   597.5  341.69  604.55     337
  618.91     337  626.09  341.68  640.44  342.34  683.52   342.7  720.03  347.38
  755.86  354.06  784.52  356.69  798.85  359.26  806.01  360.14  956.47  367.11
  999.46  369.98 1028.12  370.79 1056.78  373.33 1078.27  373.44 1095.53  374.18
#Mann= 3 , 0 , 0
       0    .074       0   597.5    .045       0  626.09    .074       0
#XS Ineff= 2 , 0
       0   597.5   349.5  626.09       0   349.5
Permanent Ineff=
       F       F
Bank Sta=597.5,626.09
XS Rating Curve= 0 ,0
Exp/Cntr=0.5,0.3

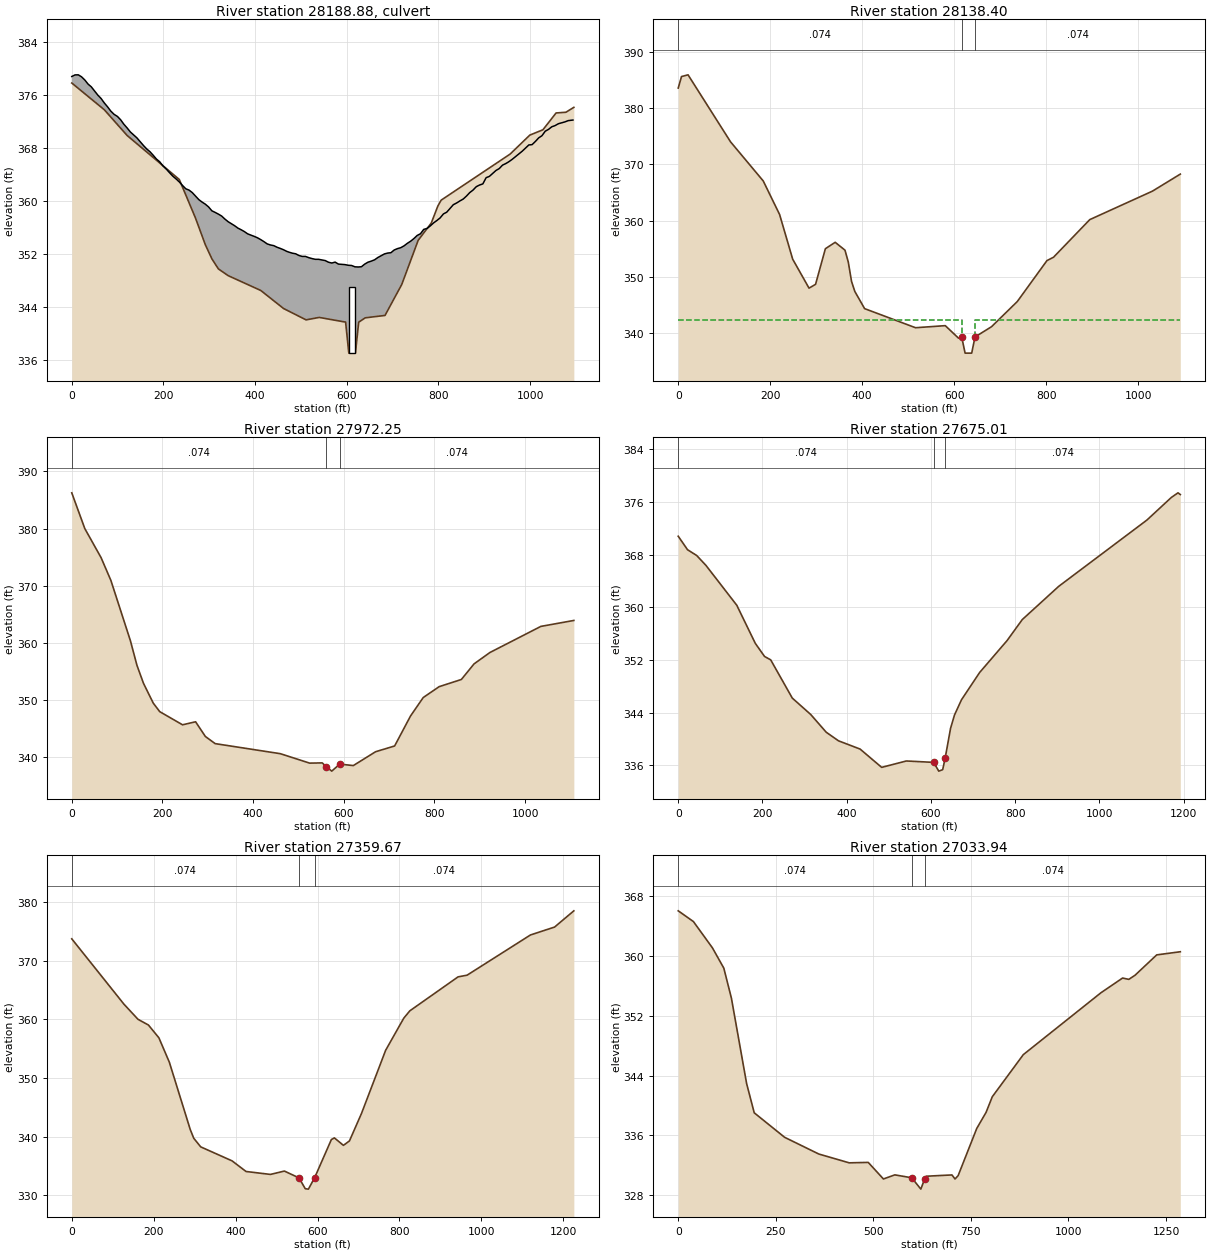
Type RM Length L Ch R = 2 ,28188.88,,,
BEGIN DESCRIPTION:
Diamond Jim Road
MDE Bridge #: CE032707FS-14
Bridge Deck taken from DEM
Bridge Opening from surveys
END DESCRIPTION:
Bridge Culvert--1,0,-1,-1, 0
Deck Dist Width WeirC Skew NumUp NumDn MinLoCord MaxHiCord MaxSubmerge Is_Ogee
30,30,2.6,0, 154, 154, , , 0.98, 0, 1,1,,
       0    7.11   14.22   21.33   28.44   35.55   42.65   49.76   56.87   63.98
   71.09    78.2   85.31   92.42   99.53  106.64  113.75  120.85  127.96  135.07
  142.18  149.29   156.4  163.51  170.62  177.73  184.84  191.94  199.05  206.16
  213.27  220.38  227.49   234.6  241.71  248.82  255.93  263.04  270.14  277.25
  284.36  291.47  298.58  305.69   312.8  319.91  327.02  334.13  341.24  348.34
  355.45  362.56  369.67  376.78  383.89     391  398.11  405.22  412.33  419.44
  426.54  433.65  440.76  447.87  454.98  462.09   469.2  474.14  481.32  488.49
  495.67  502.85  510.03  517.21  524.39  531.56  538.74  545.92   553.1  560.28
  567.46  574.64  581.81  588.99  596.17  603.35  610.53  617.71  624.89  632.06
  639.24  646.42   653.6  660.78  667.96  675.14  682.31  689.49  696.35  703.51
  710.68  717.84  725.01  732.17  739.34   746.5  753.67  760.83     768  775.16
  782.33  789.49  796.66  803.82  810.99  818.15  825.32  832.48  839.65  846.81
  853.98  861.14  868.31  875.47  882.63   889.8  896.96  904.13  911.29  918.46
  925.62  932.79  939.95  947.12  954.28  961.45  968.61  975.78  982.94  990.11
  997.27 1004.44  1011.6 1018.77 1025.93  1033.1 1040.26 1047.42 1054.59 1061.75
 1068.92 1076.08 1083.25 1093.55
  378.85  379.09   379.1   378.8  378.32   377.7  377.28  376.65  376.03  375.52
  374.84  374.25   373.6  373.12  372.81   372.3  371.62  371.06  370.45     370
  369.56  368.99  368.41  367.89  367.47  366.93  366.35  365.94  365.31  364.85
   364.3  363.78  363.36   362.9  362.36  361.86  361.66  361.28  360.74  360.22
  359.85  359.53  359.11  358.53  358.29  358.03  357.74  357.28  356.88  356.58
  356.27  355.91  355.66  355.38  355.04  354.85  354.66  354.45  354.17  353.86
  353.52  353.36  353.26  353.02  352.84  352.64  352.39  352.27  352.12  352.03
  351.77  351.63  351.63  351.44   351.3  351.19  351.19  351.09     351  350.75
  350.63  350.77  350.47  350.43  350.39  350.29  350.26  350.06  350.03  350.07
  350.47  350.76  350.92  351.12  351.47  351.74  352.01  352.14  352.19   352.6
  352.81  352.95  353.23  353.61  353.93  354.33   354.8  355.06  355.72  355.86
  356.25   356.7  357.06  357.46  358.06  358.32  358.89  359.45  359.71  360.02
   360.3  360.75  361.28  361.66  362.18  362.43   362.6  363.54  363.74  364.19
  364.63  364.92  365.44  365.68  365.98  366.34  366.74  367.15  367.55  368.02
  368.49  368.54  369.02  369.56  369.89  370.57  370.85  371.24  371.42   371.7
  371.84  371.98  372.17  372.26
                                                                                
                                                                                
                                                                                
                                                                                
                                                                                
                                                                                
                                                                                
                                                                                
                                                                                
                                                                                
                                                                                
                                                                                
                                                                                
                                                                                
                                                                                
                                
       0    7.11   14.22   21.33   28.44   35.55   42.65   49.76   56.87   63.98
   71.09    78.2   85.31   92.42   99.53  106.64  113.75  120.85  127.96  135.07
  142.18  149.29   156.4  163.51  170.62  177.73  184.84  191.94  199.05  206.16
  213.27  220.38  227.49   234.6  241.71  248.82  255.93  263.04  270.14  277.25
  284.36  291.47  298.58  305.69   312.8  319.91  327.02  334.13  341.24  348.34
  355.45  362.56  369.67  376.78  383.89     391  398.11  405.22  412.33  419.44
  426.54  433.65  440.76  447.87  454.98  462.09   469.2  474.14  481.32  488.49
  495.67  502.85  510.03  517.21  524.39  531.56  538.74  545.92   553.1  560.28
  567.46  574.64  581.81  588.99  596.17  603.35  610.53  617.71  624.89  632.06
  639.24  646.42   653.6  660.78  667.96  675.14  682.31  689.49  696.35  703.51
  710.68  717.84  725.01  732.17  739.34   746.5  753.67  760.83     768  775.16
  782.33  789.49  796.66  803.82  810.99  818.15  825.32  832.48  839.65  846.81
  853.98  861.14  868.31  875.47  882.63   889.8  896.96  904.13  911.29  918.46
  925.62  932.79  939.95  947.12  954.28  961.45  968.61  975.78  982.94  990.11
  997.27 1004.44  1011.6 1018.77 1025.93  1033.1 1040.26 1047.42 1054.59 1061.75
 1068.92 1076.08 1083.25 1093.55
  378.85  379.09   379.1   378.8  378.32   377.7  377.28  376.65  376.03  375.52
  374.84  374.25   373.6  373.12  372.81   372.3  371.62  371.06  370.45     370
  369.56  368.99  368.41  367.89  367.47  366.93  366.35  365.94  365.31  364.85
   364.3  363.78  363.36   362.9  362.36  361.86  361.66  361.28  360.74  360.22
  359.85  359.53  359.11  358.53  358.29  358.03  357.74  357.28  356.88  356.58
  356.27  355.91  355.66  355.38  355.04  354.85  354.66  354.45  354.17  353.86
  353.52  353.36  353.26  353.02  352.84  352.64  352.39  352.27  352.12  352.03
  351.77  351.63  351.63  351.44   351.3  351.19  351.19  351.09     351  350.75
  350.63  350.77  350.47  350.43  350.39  350.29  350.26  350.06  350.03  350.07
  350.47  350.76  350.92  351.12  351.47  351.74  352.01  352.14  352.19   352.6
  352.81  352.95  353.23  353.61  353.93  354.33   354.8  355.06  355.72  355.86
  356.25   356.7  357.06  357.46  358.06  358.32  358.89  359.45  359.71  360.02
   360.3  360.75  361.28  361.66  362.18  362.43   362.6  363.54  363.74  364.19
  364.63  364.92  365.44  365.68  365.98  366.34  366.74  367.15  367.55  368.02
  368.49  368.54  369.02  369.56  369.89  370.57  370.85  371.24  371.42   371.7
  371.84  371.98  372.17  372.26
                                                                                
                                                                                
                                                                                
                                                                                
                                                                                
                                                                                
                                                                                
                                                                                
                                                                                
                                                                                
                                                                                
                                                                                
                                                                                
                                                                                
                                                                                
                                
BR Coef=-1 , 0 , 0 ,, 0 ,,,0.8,0,,0,
WSPro=,,,, 1 ,,,, 0 ,,,, 0 ,,,,-1 ,-1 ,-1 , 0 , 0 , 0 , 0 , 0
Culvert=2,10,12,46,0.013,0.2,1,59,2,337,611.7,336.5,630,Culvert #1  , 0 ,22
Culvert Bottom n=0.013
BC Design=,, 0 ,, 0 ,,,,,,
BC Use User HTab Curves=0
BC User HTab FreeFlow(D)= 0

Type RM Length L Ch R = 1 ,28138.40,160.88,166.16,136.23
XS GIS Cut Line= 4
1574708.63809437708629.4638711661574242.95964192708546.938575745
1574027.23589383708497.9104512041573638.95952183 708413.15977101
#Sta/Elev= 30
       0  383.57    7.11  385.61   21.33  385.92  113.75  374.02  184.84  367.07
  220.38  361.12  248.82  353.19  284.36  348.04  298.58  348.72  319.91  355.04
  341.24  356.18  362.56  354.78  369.67  352.69  376.78  349.24  383.89  347.46
  405.22   344.4  516.01  341.01  580.61  341.38  609.33  339.16   616.5  339.29
  623.68   336.5  638.04   336.5  645.22  339.37  681.11  341.19  737.15  345.66
  801.63  352.93  815.96  353.53  894.77  360.21 1030.91  365.26 1091.58  368.29
#Mann= 3 , 0 , 0
       0    .074       0   616.5    .045       0  645.22    .074       0
#XS Ineff= 2 , 0
       0   616.5   342.4  645.22       0   342.4
Permanent Ineff=
       F       F
Bank Sta=616.5,645.22
XS Rating Curve= 0 ,0
Exp/Cntr=0.5,0.3

Type RM Length L Ch R = 1 ,27972.25,225.3,297.23,307.29
XS GIS Cut Line= 4
1574683.97145042708485.1904215661574166.32118987708364.679249793
1574097.84893318708364.6792497931573591.15423365708337.290347129
#Sta/Elev= 30
       0  386.26   28.75  380.01   64.68  374.92   86.25  370.95  129.37  360.39
  143.74   356.1  158.12  352.96  179.68  349.49  194.05  347.99  244.36  345.69
  273.11  346.22  294.67  343.65  316.24   342.4  459.98  340.64  524.67  338.99
  552.49  339.03  561.01  338.39  573.49  337.59  591.02  338.82     621  338.56
  670.07  340.98  712.13  341.99  747.18  347.23  775.22  350.46  810.27  352.36
  859.34  353.62  887.38  356.35  922.43  358.34  1034.6   362.9  1107.4  363.94
#Mann= 3 , 0 , 0
       0    .074       0  561.01    .045       0  591.02    .074       0
Bank Sta=561.01,591.02
XS Rating Curve= 0 ,0
Exp/Cntr=0.3,0.1

Type RM Length L Ch R = 1 ,27675.01,276.72,315.34,216.41
XS GIS Cut Line= 5
1574768.87704873 708307.16255419 1574212.8823244708137.351357579
1574144.41006771708077.0957717151573645.93203902707951.106819376
1573651.40981954707951.106819376
#Sta/Elev= 30
       0  370.79   21.96  368.75   43.92  367.86   65.87  366.36  139.06  360.31
  182.98  354.53  204.94  352.54  219.58  352.02  270.81  346.22  314.73  343.72
  351.32  341.04   380.6  339.73  431.83  338.48  483.07   335.7  541.62  336.67
  606.47  336.46  618.65  335.13  627.97  335.35  634.03  337.17  646.62  341.62
  655.94  343.64  672.56  345.96  715.88  350.12  780.86  354.95  816.96  358.14
   903.6  363.19 1112.98  373.25 1170.74  376.67 1186.71  377.38 1192.19  377.12
#Mann= 3 , 0 , 0
       0    .074       0  606.47    .045       0  634.03    .074       0
Bank Sta=606.47,634.03
XS Rating Curve= 0 ,0
Exp/Cntr=0.3,0.1

Type RM Length L Ch R = 1 ,27359.67,233.2,325.73,323.53
XS GIS Cut Line= 4
1574799.00484169708170.2180407941574355.30461831707863.462330818
1574275.87680057707899.0679043081573706.18762486707712.823366106
#Sta/Elev= 30
       0  373.76  127.65  362.59  161.69  360.03  187.22  359.05  212.75  356.87
  238.28   352.7  289.34  341.21  297.85  339.73  314.87  338.26  391.46  335.87
   425.5  334.06  485.07  333.56  519.11  334.13  554.76  332.97   570.1  331.12
  577.77  331.05  593.11  333.02  633.82  339.51  641.19  339.79  663.28  338.52
  678.01  339.28  707.47  343.98  766.39  354.75  810.57  360.22   825.3  361.47
  943.13  367.27  965.23  367.56 1119.89  374.42  1178.8  375.77 1225.82  378.54
#Mann= 3 , 0 , 0
       0    .074       0  554.76    .045       0  593.11    .074       0
Bank Sta=554.76,593.11
XS Rating Curve= 0 ,0
Exp/Cntr=0.3,0.1

Type RM Length L Ch R = 1 ,27033.94,296.71,394.05,540.56
XS GIS Cut Line= 4
1574790.78817089708011.3624052851574374.47685018 707608.74553594
1574308.74348378707597.7899748681573744.53208865707293.773155153
#Sta/Elev= 30
       0  366.07   38.95  364.63   87.64  361.11  116.86  358.39  136.33  354.36
  175.28  342.93  194.76  339.02  272.67  335.74  360.31   333.5  438.21  332.32
   486.9  332.38  525.85  330.16  555.07  330.71  598.44  330.32  621.73   328.8
  631.38  330.14  635.92  330.53  701.45   330.7   709.4  330.16  717.35  330.61
  765.06  336.93  788.92  339.08  804.82  341.17  884.34  346.81 1083.13  355.09
 1138.79  357.07 1154.69  356.89 1170.59  357.44 1226.25  360.17  1286.7  360.59
#Mann= 3 , 0 , 0
       0    .074       0  598.44    .045       0  631.38    .074       0
Bank Sta=598.44,631.38
XS Rating Curve= 0 ,0
Exp/Cntr=0.3,0.1