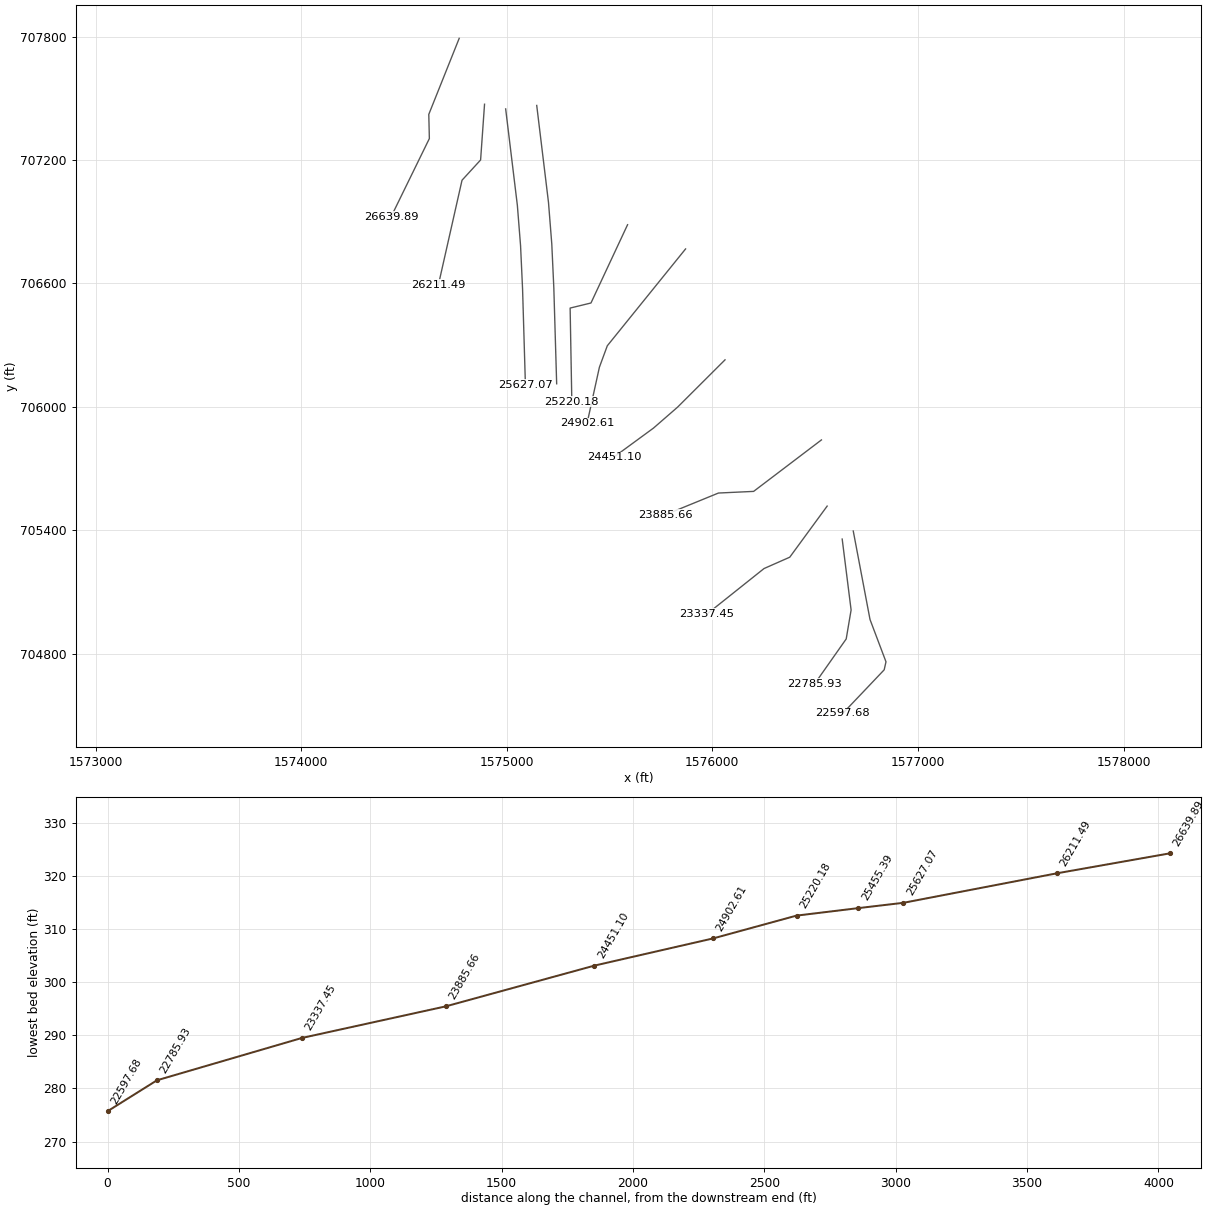
HEC-RAS study MillCreek.prj: MillCreek

--- MillCreek.g01 (geometry) --- (continued)

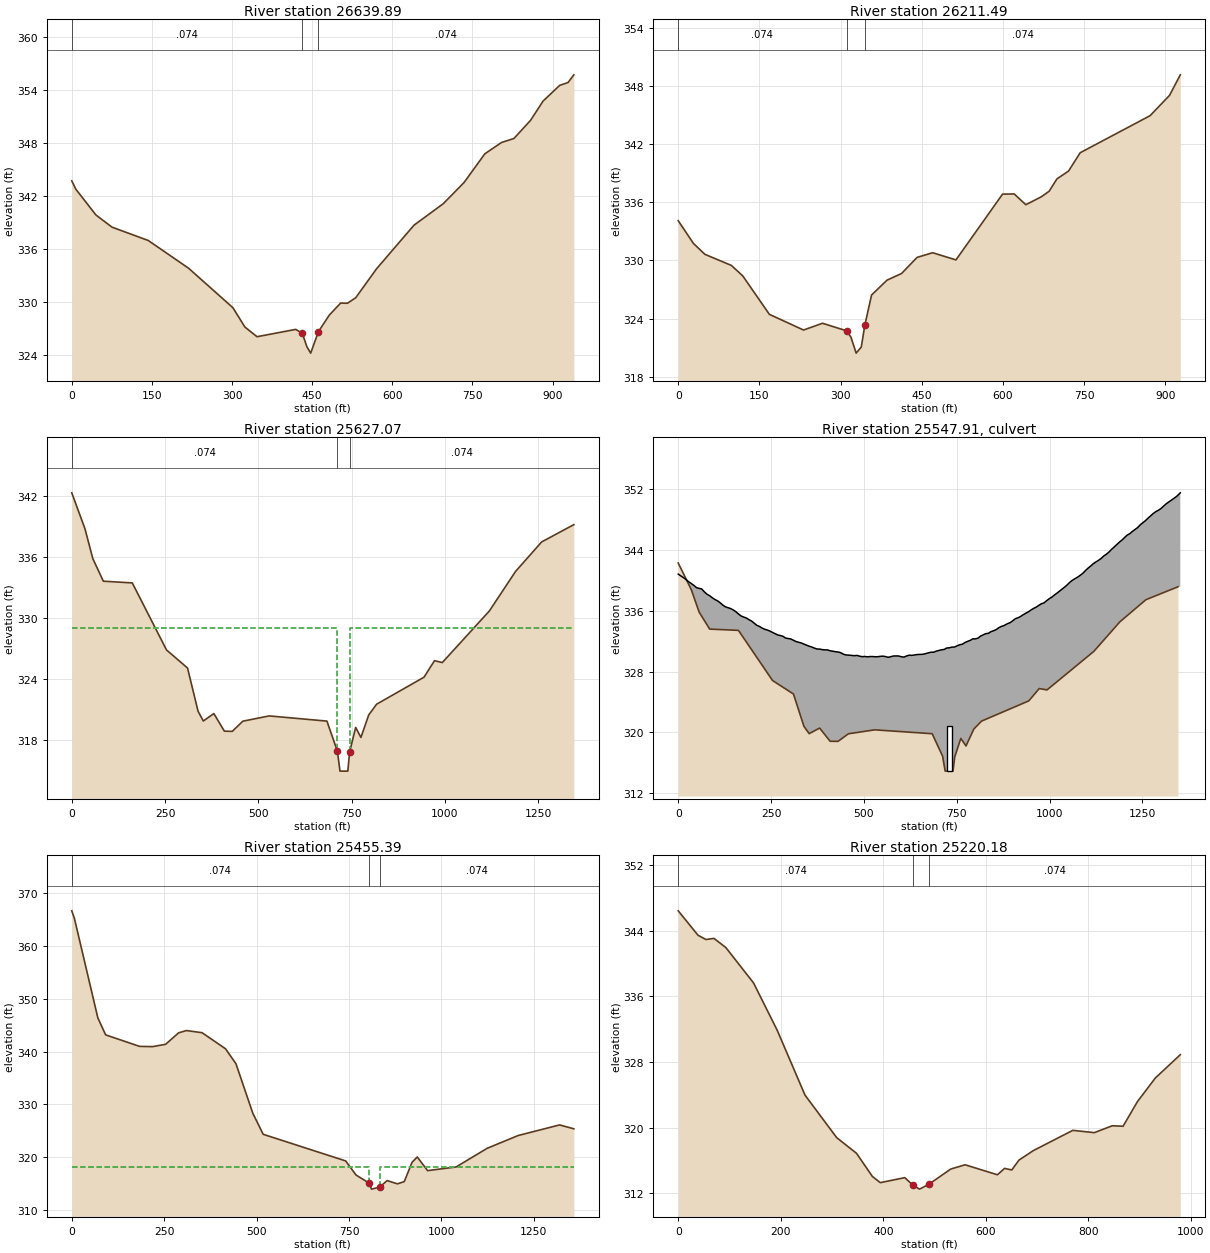
Type RM Length L Ch R = 1 ,26639.89,291.37,428.4,267.11
XS GIS Cut Line= 4
1574768.87704873707792.2511838671574620.97697429707422.500997722
1574623.71586452707304.7287162241574437.47132635706924.022969037
#Sta/Elev= 30
       0  343.71    7.54  342.77   45.24  339.84   75.39  338.46  143.25  336.95
  218.64  333.81  301.57  329.34  324.19  327.14   346.8  326.05  419.24  326.88
  431.49  326.44  440.24   324.9  447.25  324.19  461.75  326.63  482.26  328.51
  503.26  329.86  516.04  329.84  531.62  330.47  570.59  333.75  640.72  338.69
  695.27  341.11  734.23  343.51   773.2  346.77  804.37  348.05  827.75  348.51
  858.92  350.57   882.3  352.75  913.47  354.53  929.05  354.85  939.86  355.72
#Mann= 3 , 0 , 0
       0    .074       0  431.49    .045       0  461.75    .074       0
Bank Sta=431.49,461.75
XS Rating Curve= 0 ,0
Exp/Cntr=0.3,0.1

Type RM Length L Ch R = 1 ,26211.49,281.1,584.42,690.37
XS GIS Cut Line= 4
1574892.12711079707471.8010225591574872.95487893707200.650886044
1574782.57150009707102.0508364141574667.53810883706592.617246628
#Sta/Elev= 30
       0   334.1   28.07  331.76   49.12  330.64   98.24  329.49   119.3  328.41
  168.42  324.45  231.58  322.83  266.66  323.53  311.11  322.75  319.31  322.08
   328.8  320.45   338.3  321.08  344.88  323.34  357.29  326.44  385.78  327.97
  412.76  328.66  441.47  330.32  470.17   330.8  513.23  330.06  599.34  336.84
  620.87  336.86   642.4  335.75  671.11  336.57  685.46  337.14  699.81  338.41
  721.34  339.22  742.87  341.11  872.04  344.93  907.92  347.02  927.85  349.14
#Mann= 3 , 0 , 0
       0    .074       0  311.11    .045       0  344.88    .074       0
Bank Sta=311.11,344.88
XS Rating Curve= 0 ,0
Exp/Cntr=0.5,0.3

Type RM Length L Ch R = 1 ,25627.07,331.94,171.68,180.3
XS GIS Cut Line= 5
1574994.85134256707448.9373531791575051.80209853706979.584571108
1575067.35528928706783.2255379111575077.12475412706572.205098033
1575090.89669865706107.893823847
#Sta/Elev= 30
       0  342.27   35.26  338.75   56.41   335.8   84.62  333.58  162.18  333.41
  253.85  326.82  310.26  325.04  338.46  320.79  352.57  319.83  380.77  320.56
  408.98  318.83  430.13  318.81  458.34  319.81  528.97  320.33  683.78  319.82
  711.81  316.87  718.82   314.9  739.84   314.9  744.48  316.76  760.87   319.2
  774.88  318.21   795.9  320.43  816.93  321.48  944.04  324.14  972.06  325.76
  993.06  325.58 1119.12  330.65 1189.15  334.53 1259.18  337.44 1345.53  339.14
#Mann= 3 , 0 , 0
       0    .074       0  711.81    .045       0  744.48    .074       0
#XS Ineff= 2 , 0
       0  711.81     329  744.48       0     329
Permanent Ineff=
       F       F
Bank Sta=711.81,744.48
XS Rating Curve= 0 ,0
Exp/Cntr=0.5,0.3

Type RM Length L Ch R = 2 ,25547.91,,,
BEGIN DESCRIPTION:
Perrylawn Dr.
MDE Bridge #: CE032707FS-13
Bridge Deck taken from DEM
Bridge Opening from surveys
END DESCRIPTION:
Bridge Culvert--1,0,-1,-1, 0
Deck Dist Width WeirC Skew NumUp NumDn MinLoCord MaxHiCord MaxSubmerge Is_Ogee
60,50,2.6,0, 192, 192, , , 0.98, 0, 1,1,,
       0    7.05    14.1   21.15   28.21   35.26   42.31   49.36   56.41   63.46
   70.51   77.56   84.62   91.67   98.72  105.77  112.82  119.87  126.92  133.98
  141.03  148.08  155.13  162.18  169.23  176.28  183.33  190.39  197.44  204.49
  211.54  218.59  225.64  232.69  239.75   246.8  253.85   260.9  267.95     275
  282.05  289.11  296.16  303.21  310.26  317.31  324.36  331.41  338.46  345.52
  352.57  359.62  366.67  373.72  380.77  387.82  394.88  401.93  408.98  416.03
  423.08  430.13  437.18  444.23  451.29  458.34  465.39  474.25  481.28   488.3
  495.32  502.34  509.36  516.39  523.41  530.43  537.45  544.47   551.5  558.52
  565.54  572.56  579.58  586.61  593.63  600.65  607.67  614.69  621.72  628.74
  635.76  642.78   649.8  656.82  663.85  673.84  680.84  687.85  694.86  701.87
  708.87  715.88  722.89   729.9   736.9  743.91  750.92  757.93  764.93  771.94
  778.95  785.96  792.96  799.97  806.98  813.99  820.99     828  835.01  842.02
  849.02  856.03  863.04  870.05  877.05  886.81  893.81  900.82  907.82  914.82
  921.83  928.83  935.83  942.84  949.84  956.84  963.85  970.85  977.85  984.85
  991.86  998.86 1005.86 1012.87 1019.87 1026.87 1033.88 1040.88 1047.88 1054.88
 1061.89 1068.89 1075.89  1082.9  1089.9  1096.9 1103.91 1110.91 1117.91 1124.92
 1131.92 1138.92 1145.92 1152.93 1159.93 1166.93 1173.94 1180.94 1187.94 1194.95
 1201.95 1208.95 1215.95 1222.96 1229.96 1236.96 1243.97 1250.97 1257.97 1264.98
 1271.98 1278.98 1285.99 1292.99 1299.99 1306.99    1314    1321    1328 1335.01
 1342.01 1351.91
  340.81  340.57  340.35  340.09   339.8  339.57  339.32  339.02  338.93  338.85
  338.47  338.16  337.97   337.7  337.47   337.3  337.05  336.74  336.51   336.4
  336.28   336.1  335.87  335.57  335.31  335.16  335.04  334.82  334.64  334.36
  334.08  333.93  333.72  333.56  333.46  333.32  333.14  332.98  332.81  332.73
  332.63   332.4  332.34  332.28  332.11  331.94  331.85  331.75   331.6  331.46
  331.33  331.22  331.08  330.96  330.95  330.88  330.85  330.84  330.73  330.67
  330.61  330.57  330.48  330.29  330.18  330.16  330.12  330.08  330.12  330.02
  329.95  329.98  329.93  329.97  329.97  329.94  329.95     330  330.02  329.96
  329.87  329.96  330.04  330.05  330.04  329.94   329.9  330.04  330.15  330.12
  330.17  330.23  330.24  330.26  330.32  330.46  330.54  330.54  330.68  330.77
  330.86   330.9  331.09  331.12  331.21  331.22  331.38  331.52  331.59  331.81
  331.96  332.09  332.29   332.3  332.38  332.66  332.82  332.98  333.02  333.24
  333.36  333.51  333.76  333.93  334.04   334.3  334.43  334.68  334.95  335.07
  335.24  335.47  335.67  335.85  336.09   336.3  336.47   336.7  336.91  337.03
  337.31  337.57  337.78  338.06  338.31  338.58  338.86  339.12  339.42  339.76
  340.02  340.22  340.43  340.67  340.94   341.3  341.61  341.89  342.19  342.42
  342.63  342.88   343.2  343.43  343.72  344.07  344.38  344.71  345.02  345.29
  345.63  345.94  346.13  346.43  346.68  346.93  347.29  347.57  347.84  348.17
  348.47  348.78  349.03  349.21  349.44  349.76  350.06  350.31  350.54  350.79
  351.03   351.5
                                                                                
                                                                                
                                                                                
                                                                                
                                                                                
                                                                                
                                                                                
                                                                                
                                                                                
                                                                                
                                                                                
                                                                                
                                                                                
                                                                                
                                                                                
                                                                                
                                                                                
                                                                                
                                                                                
                
       0    7.05    14.1   21.15   28.21   35.26   42.31   49.36   56.41   63.46
   70.51   77.56   84.62   91.67   98.72  105.77  112.82  119.87  126.92  133.98
  141.03  148.08  155.13  162.18  169.23  176.28  183.33  190.39  197.44  204.49
  211.54  218.59  225.64  232.69  239.75   246.8  253.85   260.9  267.95     275
  282.05  289.11  296.16  303.21  310.26  317.31  324.36  331.41  338.46  345.52
  352.57  359.62  366.67  373.72  380.77  387.82  394.88  401.93  408.98  416.03
  423.08  430.13  437.18  444.23  451.29  458.34  465.39  474.25  481.28   488.3
  495.32  502.34  509.36  516.39  523.41  530.43  537.45  544.47   551.5  558.52
  565.54  572.56  579.58  586.61  593.63  600.65  607.67  614.69  621.72  628.74
  635.76  642.78   649.8  656.82  663.85  673.84  680.84  687.85  694.86  701.87
  708.87  715.88  722.89   729.9   736.9  743.91  750.92  757.93  764.93  771.94
  778.95  785.96  792.96  799.97  806.98  813.99  820.99     828  835.01  842.02
  849.02  856.03  863.04  870.05  877.05  886.81  893.81  900.82  907.82  914.82
  921.83  928.83  935.83  942.84  949.84  956.84  963.85  970.85  977.85  984.85
  991.86  998.86 1005.86 1012.87 1019.87 1026.87 1033.88 1040.88 1047.88 1054.88
 1061.89 1068.89 1075.89  1082.9  1089.9  1096.9 1103.91 1110.91 1117.91 1124.92
 1131.92 1138.92 1145.92 1152.93 1159.93 1166.93 1173.94 1180.94 1187.94 1194.95
 1201.95 1208.95 1215.95 1222.96 1229.96 1236.96 1243.97 1250.97 1257.97 1264.98
 1271.98 1278.98 1285.99 1292.99 1299.99 1306.99    1314    1321    1328 1335.01
 1342.01 1351.91
  340.81  340.57  340.35  340.09   339.8  339.57  339.32  339.02  338.93  338.85
  338.47  338.16  337.97   337.7  337.47   337.3  337.05  336.74  336.51   336.4
  336.28   336.1  335.87  335.57  335.31  335.16  335.04  334.82  334.64  334.36
  334.08  333.93  333.72  333.56  333.46  333.32  333.14  332.98  332.81  332.73
  332.63   332.4  332.34  332.28  332.11  331.94  331.85  331.75   331.6  331.46
  331.33  331.22  331.08  330.96  330.95  330.88  330.85  330.84  330.73  330.67
  330.61  330.57  330.48  330.29  330.18  330.16  330.12  330.08  330.12  330.02
  329.95  329.98  329.93  329.97  329.97  329.94  329.95     330  330.02  329.96
  329.87  329.96  330.04  330.05  330.04  329.94   329.9  330.04  330.15  330.12
  330.17  330.23  330.24  330.26  330.32  330.46  330.54  330.54  330.68  330.77
  330.86   330.9  331.09  331.12  331.21  331.22  331.38  331.52  331.59  331.81
  331.96  332.09  332.29   332.3  332.38  332.66  332.82  332.98  333.02  333.24
  333.36  333.51  333.76  333.93  334.04   334.3  334.43  334.68  334.95  335.07
  335.24  335.47  335.67  335.85  336.09   336.3  336.47   336.7  336.91  337.03
  337.31  337.57  337.78  338.06  338.31  338.58  338.86  339.12  339.42  339.76
  340.02  340.22  340.43  340.67  340.94   341.3  341.61  341.89  342.19  342.42
  342.63  342.88   343.2  343.43  343.72  344.07  344.38  344.71  345.02  345.29
  345.63  345.94  346.13  346.43  346.68  346.93  347.29  347.57  347.84  348.17
  348.47  348.78  349.03  349.21  349.44  349.76  350.06  350.31  350.54  350.79
  351.03   351.5
                                                                                
                                                                                
                                                                                
                                                                                
                                                                                
                                                                                
                                                                                
                                                                                
                                                                                
                                                                                
                                                                                
                                                                                
                                                                                
                                                                                
                                                                                
                                                                                
                                                                                
                                                                                
                                                                                
                
BR Coef=-1 , 0 , 0 ,, 0 ,,,0.8,0,,0,
WSPro=,,,, 1 ,,,, 0 ,,,, 0 ,,,,-1 ,-1 ,-1 , 0 , 0 , 0 , 0 , 0
Culvert=2,6,14,110,0.013,0.4,1,8,1,314.9,730,313.9,818,Culvert #1  , 0 ,30
Culvert Bottom n=0.013
BC Design=,, 0 ,, 0 ,,,,,,
BC Use User HTab Curves=0
BC User HTab FreeFlow(D)= 0

Type RM Length L Ch R = 1 ,25455.39,364.6,235.2,95.89
XS GIS Cut Line= 5
1575145.94466098707465.8011108191575203.24712558706993.549764588
1575219.21206467706791.9924089011575229.14143102706577.518096268
1575242.94785003706112.044540778
#Sta/Elev= 30
       0  366.69    7.05  365.28   70.51  346.39   91.67  343.16  183.33  340.98
  218.59  340.93  253.85  341.37  289.11  343.55  310.26  343.98  352.57  343.57
  416.03  340.52  444.23  337.68  489.76   328.3  517.85   324.3  740.97  319.25
     769  316.58  804.04  315.06  811.05   313.9  832.76  314.27  853.09  315.52
  881.12   314.9  899.61  315.33  920.62  318.99  934.63     320  962.64  317.41
 1039.67   318.1 1123.71  321.64 1207.74  324.07 1319.79  326.08 1358.28  325.34
#Mann= 3 , 0 , 0
       0    .074       0  804.04    .045       0  832.76    .074       0
#XS Ineff= 2 , 0
       0  804.04   318.1  832.76       0   318.1
Permanent Ineff=
       F       F
Bank Sta=804.04,832.76
XS Rating Curve= 0 ,0
Exp/Cntr=0.5,0.3

Type RM Length L Ch R = 1 ,25220.18,203.41,317.57,202.49
XS GIS Cut Line= 4
1575587.80523878706885.6785052721575409.77737135706504.972758085
1575308.43843144706480.3227456661575316.65510228706025.666961238
#Sta/Elev= 30
       0  346.44   38.64  343.46   54.09  342.94   69.55  343.08   92.73  341.97
  146.82  337.65  193.19  331.85  247.28  323.96   309.1  318.77  347.74  316.86
  378.65  314.04   394.1  313.28  441.89  313.89  457.53  312.98   470.7  312.49
  488.57  313.07  531.57  314.94  559.57  315.46  622.58  314.24  636.59  315.02
  650.59  314.83  664.59  316.03   692.6  317.19  769.61  319.66  811.62  319.38
  846.62  320.22  867.63  320.16  895.63  323.16  930.64  326.05   979.3  328.89
#Mann= 3 , 0 , 0
       0    .074       0  457.53    .045       0  488.57    .074       0
Bank Sta=457.53,488.57
XS Rating Curve= 0 ,0
Exp/Cntr=0.3,0.1

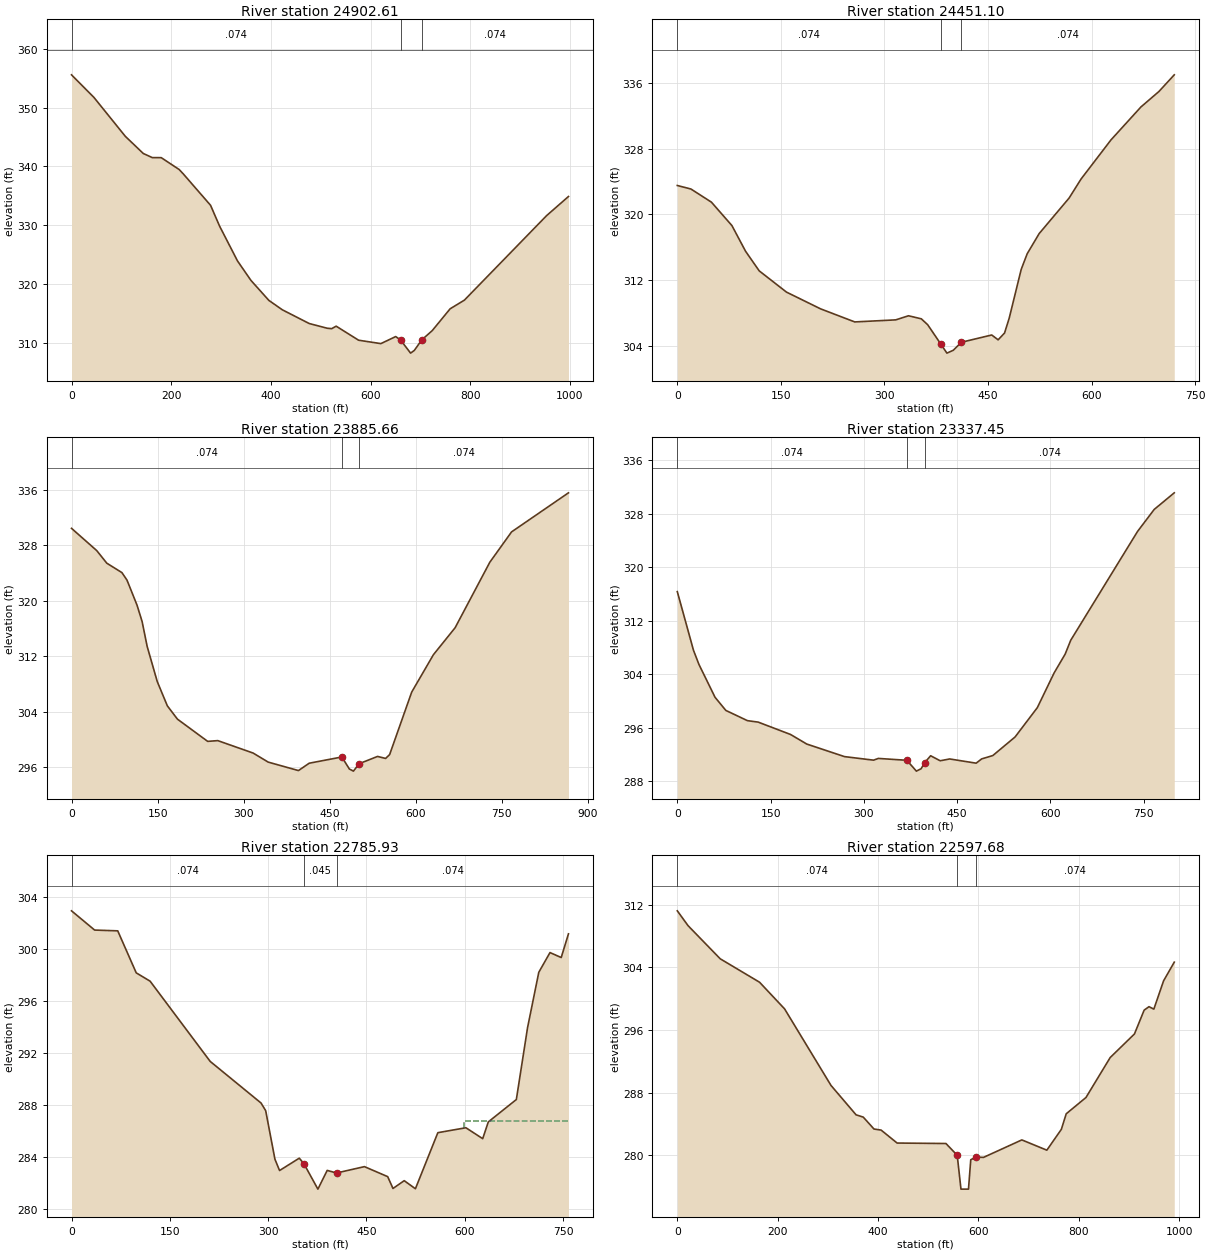
Type RM Length L Ch R = 1 ,24902.61,461.93,451.51,353.58
XS GIS Cut Line= 4
1575869.91093634706767.9062237741575489.20518909706296.817097723
1575450.86072536706192.7392675731575390.60513948705918.850240797
#Sta/Elev= 30
       0  355.61      45  351.76     108  345.13     144  342.21     162  341.51
     180   341.5     216  339.48     225  338.66     279  333.38     297  329.85
     333  323.91     360  320.59     396  317.18     423  315.58     477  313.24
     513  312.44     522  312.37     531  312.79  576.01   310.4  620.61  309.82
  650.45  311.02  660.24  310.43  680.29   308.2  687.75  308.66  702.67  310.45
  723.78  312.04  759.61  315.75  788.28  317.23  953.13  331.62  997.05  334.88
#Mann= 3 , 0 , 0
       0    .074       0  660.24    .045       0  702.67    .074       0
Bank Sta=660.24,702.67
XS Rating Curve= 0 ,0
Exp/Cntr=0.3,0.1

Type RM Length L Ch R = 1 ,24451.10,578.44,565.44,463.08
XS GIS Cut Line= 4
1576061.79091765706228.4833438691575831.27292454 705998.56347999
 1575714.1790604705896.742697164 1575521.2681122705755.525889114
#Sta/Elev= 30
       0  323.51   19.77  323.08   49.43  321.48   79.09  318.63   98.87   315.5
  118.64  313.11  158.19  310.52  207.62  308.48  257.05  306.89  316.37  307.14
  334.86  307.64  353.41  307.27  362.68  306.55  381.29  304.24  390.51  303.09
  399.79  303.44  411.38  304.41  455.45   305.3  464.72  304.71     474  305.54
  480.75  307.35   498.1  313.28  506.78  315.19  524.13  317.65   567.5  321.98
  584.85   324.3  628.23  329.07   671.6  333.08  697.63  334.96  719.83  336.99
#Mann= 3 , 0 , 0
       0    .074       0  381.29    .045       0  411.38    .074       0
Bank Sta=381.29,411.38
XS Rating Curve= 0 ,0
Exp/Cntr=0.3,0.1

Type RM Length L Ch R = 1 ,23885.66,349.19,548.21,438.96
XS GIS Cut Line= 4
1576530.77394001705838.9889693711576200.89605144705588.599728599
1576029.99545853705580.6508638261575770.15654545705474.404262945
#Sta/Elev= 30
       0  330.45   43.94  327.24   61.52  325.42   87.88  324.06   96.67  322.98
  114.25  319.35  123.03     317  131.82  313.42   149.4  308.35  166.97  304.85
  184.55  302.93  237.28  299.72  254.85  299.83  316.37  298.04  342.74  296.73
  395.46  295.51  414.14  296.57  471.08  297.47  484.22  295.73  491.23  295.43
  501.21   296.5  533.27  297.55  547.29  297.26  554.29  297.81  592.79  306.83
   630.6  312.22  668.42  316.11  728.92  325.56  766.73  329.93  865.95  335.57
#Mann= 3 , 0 , 0
       0    .074       0  471.08    .045       0  501.21    .074       0
Bank Sta=471.08,501.21
XS Rating Curve= 0 ,0
Exp/Cntr=0.3,0.1

Type RM Length L Ch R = 1 ,23337.45,452.51,551.52,584.59
XS GIS Cut Line= 4
 1576558.5949668705517.0599455241576376.69639891705268.547739461
1576251.54638141705213.3345117871575974.35340503704992.434869647
#Sta/Elev= 30
       0  316.33   26.02  307.56    34.7  305.46   60.72  300.52   78.07  298.56
  112.77  297.03  130.12  296.81  182.17  294.96  208.19  293.53  268.92  291.65
  315.62  291.12  323.27  291.38  369.18   291.1  384.48  289.48  392.13  289.84
     398  290.77  407.43  291.78  422.73  291.03  438.04   291.3  480.56  290.67
  489.51  291.31  507.41  291.81  543.22  294.59  579.02  298.98  605.87  304.15
  623.78  306.99  632.73  309.06  740.14  325.33  766.99  328.63  799.21  331.11
#Mann= 3 , 0 , 0
       0    .074       0  369.18    .045       0     398    .074       0
Bank Sta=369.18,398
XS Rating Curve= 0 ,0
Exp/Cntr=0.3,0.1

Type RM Length L Ch R = 1 ,22785.93,97.34,188.26,216.3
XS GIS Cut Line= 4
1576631.69642909705356.7019530391576675.07640846705011.831117272
1576651.21741979704870.8461844181576497.21849313 704651.77728875
#Sta/Elev= 30
       0  302.92   35.28  301.44   70.55  301.38   98.77  298.15  119.94  297.51
  211.65  291.34  289.26  288.14  296.32  287.55  310.43  283.82  317.48  282.95
  347.59   283.9  354.69  283.47  375.99  281.52  390.19  282.96  404.38  282.76
  446.98  283.25  482.48  282.48  490.58  281.57  507.69  282.17   524.8  281.55
  559.03  285.86  601.81  286.24  627.48   285.4  636.04  286.69  678.82  288.41
  695.93  293.94  713.05  298.19  730.16  299.71  747.27  299.33  758.36  301.15
#Mann= 3 , 0 , 0
       0    .074       0  354.69    .045       0  404.38    .074       0
#XS Ineff= 2 , 0
                          598.67          286.75
Permanent Ineff=
       F       F
Bank Sta=354.69,404.38
XS Rating Curve= 0 ,0
Exp/Cntr=0.5,0.3

Type RM Length L Ch R = 1 ,22597.68,114.75,100.49,97.55
XS GIS Cut Line= 6
1576685.53976119705395.7801199851576767.05739369704965.448148042
1576844.70039117704759.799127713 1576836.0537885704720.889415681
1576762.49145001704643.3507345911576634.53886494 704508.89208591
#Sta/Elev= 30
       0  311.21   21.37  309.32   85.49  305.09  163.86   302.1  213.73   298.7
  306.35  288.92  356.22  285.18  370.47  284.89  391.85  283.37   406.1  283.23
  437.98  281.58  535.25  281.52   557.7  280.02  565.18   275.7  580.15   275.7
  584.69  279.45  595.11  279.79  610.08  279.75  686.49  281.98  736.26  280.67
   765.2  283.33  774.85  285.31  814.21  287.39  862.52  292.49  910.84   295.5
  930.16  298.54  939.82  298.98  949.49  298.67  968.81  302.27  990.15  304.66
#Mann= 3 , 0 , 0
       0    .074       0   557.7    .045       0  595.11    .074       0
Bank Sta=557.7,595.11
XS Rating Curve= 0 ,0
Exp/Cntr=0.5,0.3