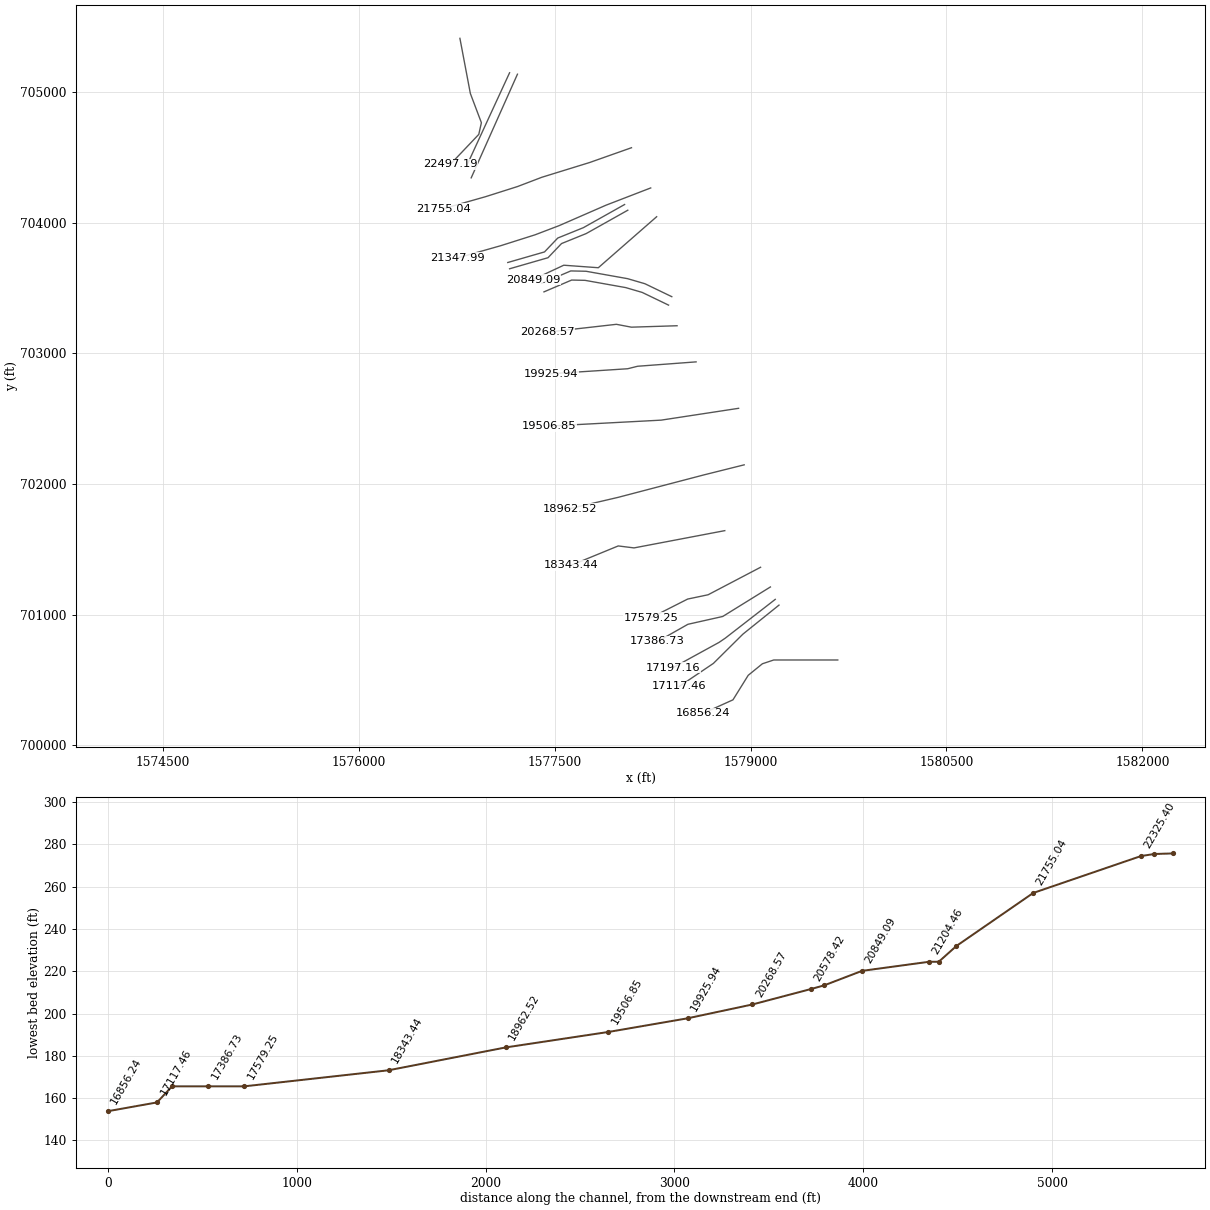
HEC-RAS study MillCreek.prj: MillCreek

--- MillCreek.g01 (geometry) --- (continued)

Type RM Length L Ch R = 2 ,22555.74,,,
BEGIN DESCRIPTION:
Principio Rd
MDE Bridge #CE032707FS-12
Bridge Deck taken from DEM
Bridge Opening from surveys
END DESCRIPTION:
Bridge Culvert--1,0,-1,-1, 0
Deck Dist Width WeirC Skew NumUp NumDn MinLoCord MaxHiCord MaxSubmerge Is_Ogee
30,26,2.6,0, 131, 131, , , 0.98, 0, 1,1,,
       0    7.12   14.25   21.37    28.5   35.62   42.75   49.87      57   64.12
   71.24   78.37   85.49   92.62   99.74  106.87  113.99  121.12  128.24  135.37
  142.49  149.61  156.74  163.86  170.99  178.11  185.24  192.36  199.49  206.61
  213.73  220.86  227.98  235.11  242.23  249.36  256.48  263.61  270.73  277.85
  284.98   292.1  299.23  306.35  313.48   320.6  327.73  334.85  341.98   349.1
  356.22  363.35  370.47   377.6  384.72  391.85  398.97   406.1  413.22  420.34
  427.47  434.94  442.42   449.9  457.38  464.86  472.35  479.83  487.31  494.79
  502.28  509.76  517.24  524.72  532.21  539.69  547.17  554.65  562.13  569.62
   577.1  584.58  592.06  599.55  607.03  614.51  621.99  629.48  636.96  644.44
  651.92  662.14  669.31  676.48  683.66  690.83     698  705.17  712.34  722.13
  731.78  741.43  751.08  760.73  770.38  780.03  789.68  799.33  808.98  818.62
  828.27  838.74   848.4  858.06  867.73  877.39  887.05  896.71  906.38  916.04
   925.7  935.37  945.03  954.69  964.36  974.02  983.68  993.34 1003.01 1012.67
 1024.37
  312.34  310.98  309.97  308.92  308.13  307.78  307.66  307.66  307.62  307.82
  308.07  308.33  308.39  308.12  307.96  307.95  307.83  307.59  307.33  307.27
  306.93  306.67   306.2   305.3  304.21  303.82  303.31  302.52  301.96  301.39
     301  300.36  299.47  298.66  297.79  296.85  295.91  295.17  294.29  293.51
  292.66  291.42  290.22  288.96  287.54  285.96  285.91   286.1  286.03  285.86
   285.6  285.38  285.13  284.88  284.59   284.3  284.07  283.99  283.92  283.84
  283.75  283.64  283.55  283.27  283.18     283  282.91  282.72   282.6  282.56
  282.45  282.31  282.27  282.16  282.07  281.75  281.91  281.86  281.68  281.73
  281.67  281.51  281.43  281.36  281.23  281.21   281.2   281.2  281.11  281.15
   281.1  280.86  281.02  280.99  280.99     281   280.8  280.53  280.33  280.28
  280.37  280.39  280.43  280.39  280.85   281.5   282.3  284.09  285.77   286.3
  286.55  287.35  287.88  288.61  289.56  290.76  291.77  292.36  292.83  293.38
  294.12  295.15  296.05  297.22   298.9  299.16  299.13   300.2  302.61  304.15
  305.23
                                                                                
                                                                                
                                                                                
                                                                                
                                                                                
                                                                                
                                                                                
                                                                                
                                                                                
                                                                                
                                                                                
                                                                                
                                                                                
        
       0    7.12   14.25   21.37    28.5   35.62   42.75   49.87      57   64.12
   71.24   78.37   85.49   92.62   99.74  106.87  113.99  121.12  128.24  135.37
  142.49  149.61  156.74  163.86  170.99  178.11  185.24  192.36  199.49  206.61
  213.73  220.86  227.98  235.11  242.23  249.36  256.48  263.61  270.73  277.85
  284.98   292.1  299.23  306.35  313.48   320.6  327.73  334.85  341.98   349.1
  356.22  363.35  370.47   377.6  384.72  391.85  398.97   406.1  413.22  420.34
  427.47  434.94  442.42   449.9  457.38  464.86  472.35  479.83  487.31  494.79
  502.28  509.76  517.24  524.72  532.21  539.69  547.17  554.65  562.13  569.62
   577.1  584.58  592.06  599.55  607.03  614.51  621.99  629.48  636.96  644.44
  651.92  662.14  669.31  676.48  683.66  690.83     698  705.17  712.34  722.13
  731.78  741.43  751.08  760.73  770.38  780.03  789.68  799.33  808.98  818.62
  828.27  838.74   848.4  858.06  867.73  877.39  887.05  896.71  906.38  916.04
   925.7  935.37  945.03  954.69  964.36  974.02  983.68  993.34 1003.01 1012.67
 1024.37
  312.34  310.98  309.97  308.92  308.13  307.78  307.66  307.66  307.62  307.82
  308.07  308.33  308.39  308.12  307.96  307.95  307.83  307.59  307.33  307.27
  306.93  306.67   306.2   305.3  304.21  303.82  303.31  302.52  301.96  301.39
     301  300.36  299.47  298.66  297.79  296.85  295.91  295.17  294.29  293.51
  292.66  291.42  290.22  288.96  287.54  285.96  285.91   286.1  286.03  285.86
   285.6  285.38  285.13  284.88  284.59   284.3  284.07  283.99  283.92  283.84
  283.75  283.64  283.55  283.27  283.18     283  282.91  282.72   282.6  282.56
  282.45  282.31  282.27  282.16  282.07  281.75  281.91  281.86  281.68  281.73
  281.67  281.51  281.43  281.36  281.23  281.21   281.2   281.2  281.11  281.15
   281.1  280.86  281.02  280.99  280.99     281   280.8  280.53  280.33  280.28
  280.37  280.39  280.43  280.39  280.85   281.5   282.3  284.09  285.77   286.3
  286.55  287.35  287.88  288.61  289.56  290.76  291.77  292.36  292.83  293.38
  294.12  295.15  296.05  297.22   298.9  299.16  299.13   300.2  302.61  304.15
  299.33
                                                                                
                                                                                
                                                                                
                                                                                
                                                                                
                                                                                
                                                                                
                                                                                
                                                                                
                                                                                
                                                                                
                                                                                
                                                                                
        
BR Coef=-1 , 0 , 0 ,, 0 ,,,0.8,0,,0,
WSPro=,,,, 1 ,,,, 0 ,,,, 0 ,,,,-1 ,-1 ,-1 , 0 , 0 , 0 , 0 , 0
Culvert=2,4,7,40,0.012,0.2,1,58,1,275.7,573,275.7,585,Culvert #1  , 0 ,37
Culvert Bottom n=0.012
BC Design=,, 0 ,, 0 ,,,,,,
BC Use User HTab Curves=0
BC User HTab FreeFlow(D)= 0

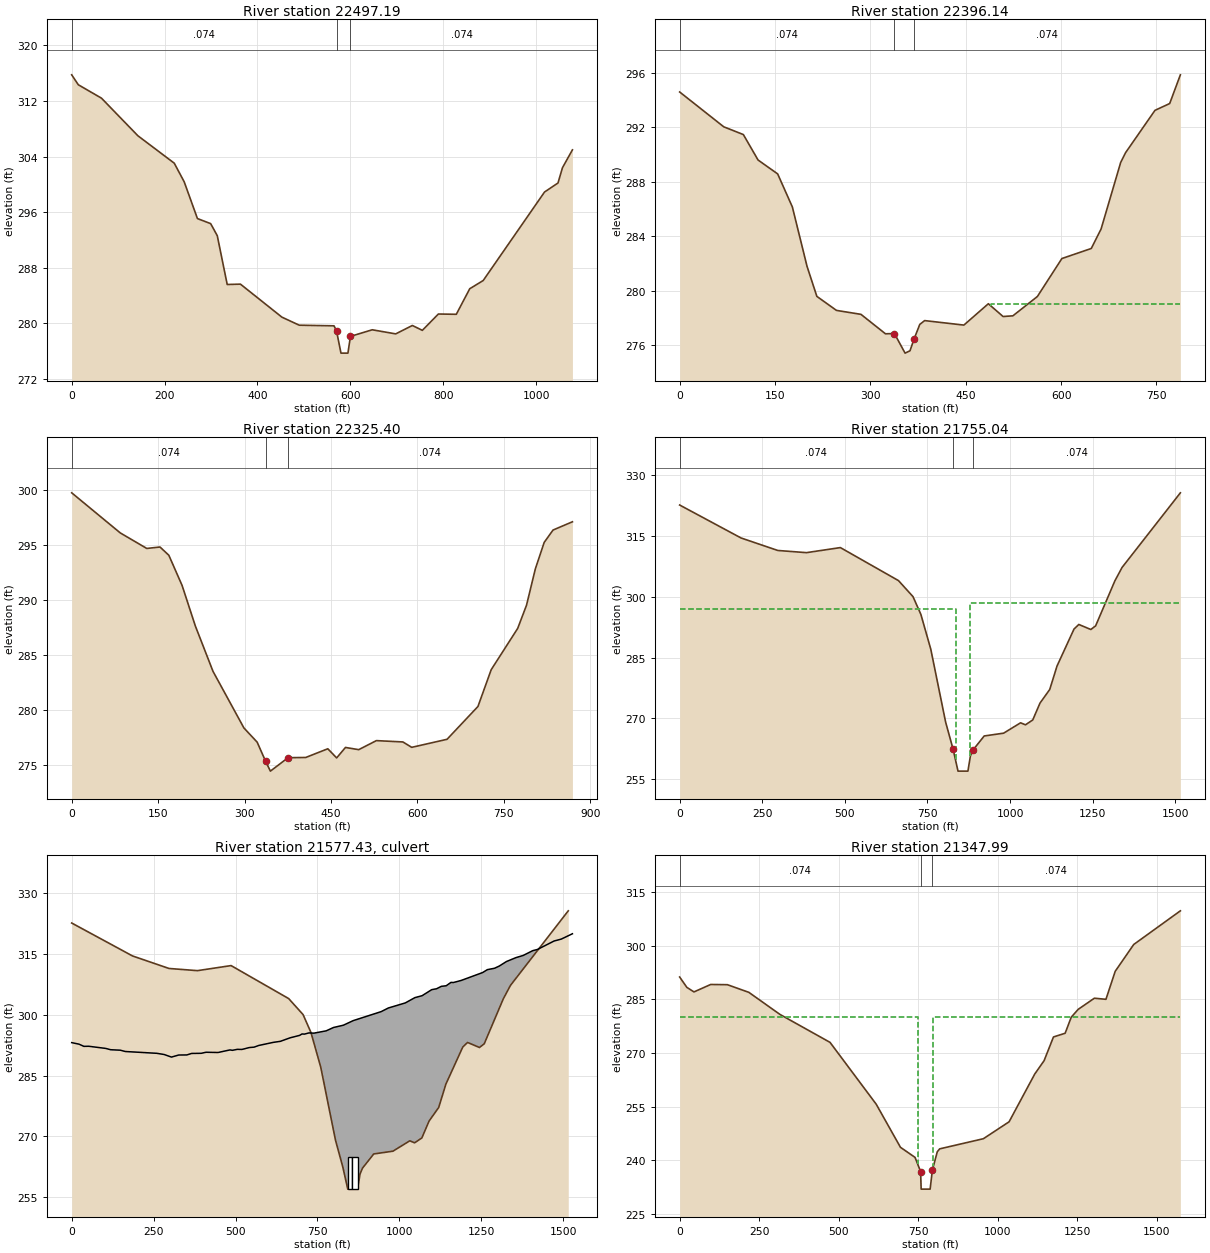
Type RM Length L Ch R = 1 ,22497.19,180.36,101.04,62.27
XS GIS Cut Line= 6
1576773.96719719705412.5308977661576854.02556337704989.902399838
 1576938.3798977704766.4774063231576918.50286059704677.030739829
1576827.73606221704581.3576280181576699.73628108704446.849383444
#Sta/Elev= 30
       0  315.76   14.25  314.33   64.12   312.4  142.49  306.99  220.86  303.04
  242.23  300.36  270.73  295.07  299.23  294.34  313.48   292.6  334.85  285.58
  363.35  285.63  452.59  280.88     490  279.72  564.83  279.63  570.23  278.89
  579.79   275.7  594.75   275.7  600.21  278.11  647.13  279.06  697.65  278.47
   733.5  279.68  755.01  278.98  789.54  281.33  828.13  281.29  857.08  284.97
  886.03  286.15 1018.09  298.89 1047.08  300.19 1056.74  302.39 1078.15  304.96
#Mann= 3 , 0 , 0
       0    .074       0  570.23    .045       0  600.21    .074       0
Bank Sta=570.23,600.21
XS Rating Curve= 0 ,0
Exp/Cntr=0.5,0.3

Type RM Length L Ch R = 1 ,22396.14,65.49,70.75,69.22
XS GIS Cut Line= 2
1577154.31486638705148.9249270261576824.45364948704433.647158101
#Sta/Elev= 30
       0  294.61   69.38  292.05  100.21  291.48  123.34  289.61  154.17  288.59
   177.3  286.16  200.42  281.79  215.84  279.59  246.67  278.56  285.21  278.27
  323.76  276.84  337.83  276.86  354.59  275.42   362.3  275.59  368.95  276.48
  377.72  277.53  385.42  277.81  447.09  277.48  485.64  279.05  508.76  278.11
  524.18  278.16  562.72  279.58  601.26  282.37  647.51  283.11  662.93  284.54
  693.76  289.43  701.47  290.15  747.72  293.26  770.85  293.76  787.67  295.87
#Mann= 3 , 0 , 0
       0    .074       0  337.83    .045       0  368.95    .074       0
#XS Ineff= 2 , 0
       0                  490.01       0  279.05
Permanent Ineff=
       F       F
Bank Sta=337.83,368.95
XS Rating Curve= 0 ,0
Exp/Cntr=0.3,0.1

Type RM Length L Ch R = 1 ,22325.40,653.13,570.36,323.29
XS GIS Cut Line= 2
1577214.60083501705137.9459463661576860.43422055704344.195893437
#Sta/Elev= 30
       0  299.72   84.32  296.08  130.31  294.67   153.3   294.8  168.63  294.05
  191.63  291.31  214.63  287.63  245.29  283.51  298.94  278.37  321.94  277.08
  336.55  275.35  344.93  274.45  375.59  275.67  406.26  275.69  444.58  276.48
  459.91  275.65  475.24   276.6  498.24   276.4   528.9  277.22  574.89   277.1
  590.22  276.61  651.54  277.34   705.2  280.32  728.19  283.66  774.19  287.41
  789.52  289.52  804.85  292.82  820.18  295.22  835.51  296.34  869.18  297.09
#Mann= 3 , 0 , 0
       0    .074       0  336.55    .045       0  375.59    .074       0
Bank Sta=336.55,375.59
XS Rating Curve= 0 ,0
Exp/Cntr=0.5,0.3

Type RM Length L Ch R = 1 ,21755.04,392.16,407.04,430.07
XS GIS Cut Line= 6
1578087.93441473704574.8711386921577767.42255655704461.607549727
1577401.72623605704348.7080145331577215.67704348704277.715559453
1576970.49228005704199.9165479841576646.72312152704108.101413518
#Sta/Elev= 30
       0   322.7  185.61  314.57  296.97  311.48  383.89  310.94  486.46  312.19
  662.28  304.04  706.24  300.09  730.16  295.69  760.12   287.1  805.08  269.09
  827.56  262.43  842.54     257  872.51     257     880  260.73  887.49  262.17
   921.8  265.68  980.55  266.37 1031.96  268.93 1046.64  268.43 1068.68  269.63
 1090.71   273.8 1120.08  277.15 1142.12  282.93 1193.58  292.07 1208.13  293.21
 1244.51  291.97 1259.07  292.87 1317.27  303.97  1339.1  307.29 1515.56  325.71
#Mann= 3 , 0 , 0
       0    .074       0  827.56    .045       0  887.49    .074       0
#XS Ineff= 2 , 0
       0  835.05     297     880       0   298.5
Permanent Ineff=
       F       F
Bank Sta=827.56,887.49
XS Rating Curve= 0 ,0
Exp/Cntr=0.5,0.3

Type RM Length L Ch R = 2 ,21577.43,,,
BEGIN DESCRIPTION:
Interstate Route 95
MDE Bridge #CE032707FS-11
Bridge Deck taken from DEM
Bridge Opening from surveys
END DESCRIPTION:
Bridge Culvert--1,0,-1,-1, 0
Deck Dist Width WeirC Skew NumUp NumDn MinLoCord MaxHiCord MaxSubmerge Is_Ogee
80,220,2.6,0, 60, 60, , , 0.98, 0, 1.5,1.5,,
       0   22.27   37.12   51.97  103.94  118.79  148.48  163.33  259.85  282.12
  304.39  326.67  351.29  365.94  395.24  409.89  446.52  483.15  490.48  505.13
  519.78  541.76  556.41  571.07  615.02     637   666.3  695.61  702.93  710.26
   724.2  739.19  776.65  799.13  829.09  859.06  944.59  966.62 1018.02  1047.4
 1069.43 1098.81  1113.5 1128.18 1142.87 1157.56  1164.9 1188.61 1254.09 1268.64
 1290.47 1305.02 1326.85 1355.96 1377.78 1406.89 1421.44 1472.37  1494.2 1528.24
  293.17  292.79  292.25  292.27  291.74  291.42   291.3  290.98  290.53  290.24
   289.6  290.11  290.13   290.5  290.53  290.79  290.73  291.37  291.27  291.51
  291.49  291.95  292.05  292.47  293.23  293.49  294.35  294.96  295.31  295.27
  295.57  295.51  296.08  296.91  297.47   298.6  300.83  301.73  302.97  304.28
  304.76  306.25  306.47  307.07  307.21  308.04  308.01  308.52  310.47  311.19
  311.53  312.08  313.19  314.16  314.69  315.87  316.17  318.26  318.73  320.05
                                                                                
                                                                                
                                                                                
                                                                                
                                                                                
                                                                                
       0   22.27   37.12   51.97  103.94  118.79  148.48  163.33  259.85  282.12
  304.39  326.67  351.29  365.94  395.24  409.89  446.52  483.15  490.48  505.13
  519.78  556.41  571.07  615.02     637   666.3  695.61  702.93  710.26   724.2
  739.19  776.65  799.13  829.09  859.06  944.59  966.62 1018.02  1047.4 1069.43
 1098.81  1113.5 1128.18 1142.87 1157.56  1164.9 1188.61 1254.09 1268.64 1290.47
 1305.02 1326.85 1355.96 1377.78 1406.89 1421.44 1472.37  1494.2 1528.24 1574.42
  293.17  292.79  292.25  292.27  291.74  291.42   291.3  290.98  290.53  290.24
   289.6  290.11  290.13   290.5  290.53  290.79  290.73  291.37  291.27  291.51
  291.49  292.05  292.47  293.23  293.49  294.35  294.96  295.31  295.27  295.57
  295.51  296.08  296.91  297.47   298.6  300.83  301.73  302.97  304.28  304.76
  306.25  306.47  307.07  307.21  308.04  308.01  308.52  310.47  311.19  311.53
  312.08  313.19  314.16  314.69  315.87  316.17  318.26  318.73  320.05  309.74
                                                                                
                                                                                
                                                                                
                                                                                
                                                                                
                                                                                
BR Coef=-1 , 0 , 0 ,, 0 ,,,0.8,-1,,0,
WSPro=,,,, 1 ,,,, 0 ,,,, 0 ,,,,-1 ,-1 ,-1 , 0 , 0 , 0 , 0 , 0
Culvert=2,8,12,340,0.012,0.5,1,8,2,257,850,231.9,765,Culvert #1  , 0 ,55
Culvert Bottom n=0.012
Culvert=2,8,16,340,0.012,0.5,1,8,2,257,865,231.9,780,Culvert #2  , 0 ,55
Culvert Bottom n=0.012
BC Design=,, 0 ,, 0 ,,,,,,
BC Use User HTab Curves=0
BC User HTab FreeFlow(D)= 0

Type RM Length L Ch R = 1 ,21347.99,92.03,92.85,123.16
XS GIS Cut Line= 6
1578235.03970005 704266.81780538 1577893.6641099704135.144363493
1577534.63057525703978.5476579221577350.15306512703908.154923797
1577086.88995779703824.6195147341576756.72229344703730.989878595
#Sta/Elev= 30
       0  291.23   22.51  288.34   45.02  287.06   97.53  289.14  150.05  289.08
  217.58  286.94  315.11  280.78  472.81  272.95  617.91  255.67  694.27   243.6
   740.1  240.78  757.59  236.83  759.35   231.9  787.56   231.9  794.61   237.2
  810.03  242.35  817.53  243.16  955.04     246 1035.82  250.73 1116.61  264.11
 1145.98  267.84 1175.36  274.46 1212.08   275.5 1231.24  279.98 1253.07  282.18
    1304   285.3 1340.38  284.99 1369.48  292.82 1427.69  300.32 1574.42  309.74
#Mann= 3 , 0 , 0
       0    .074       0  757.59    .045       0  794.61    .074       0
#XS Ineff= 2 , 0
       0     748     280     796       0     280
Permanent Ineff=
       F       F
Bank Sta=757.59,794.61
XS Rating Curve= 0 ,0
Exp/Cntr=0.5,0.3

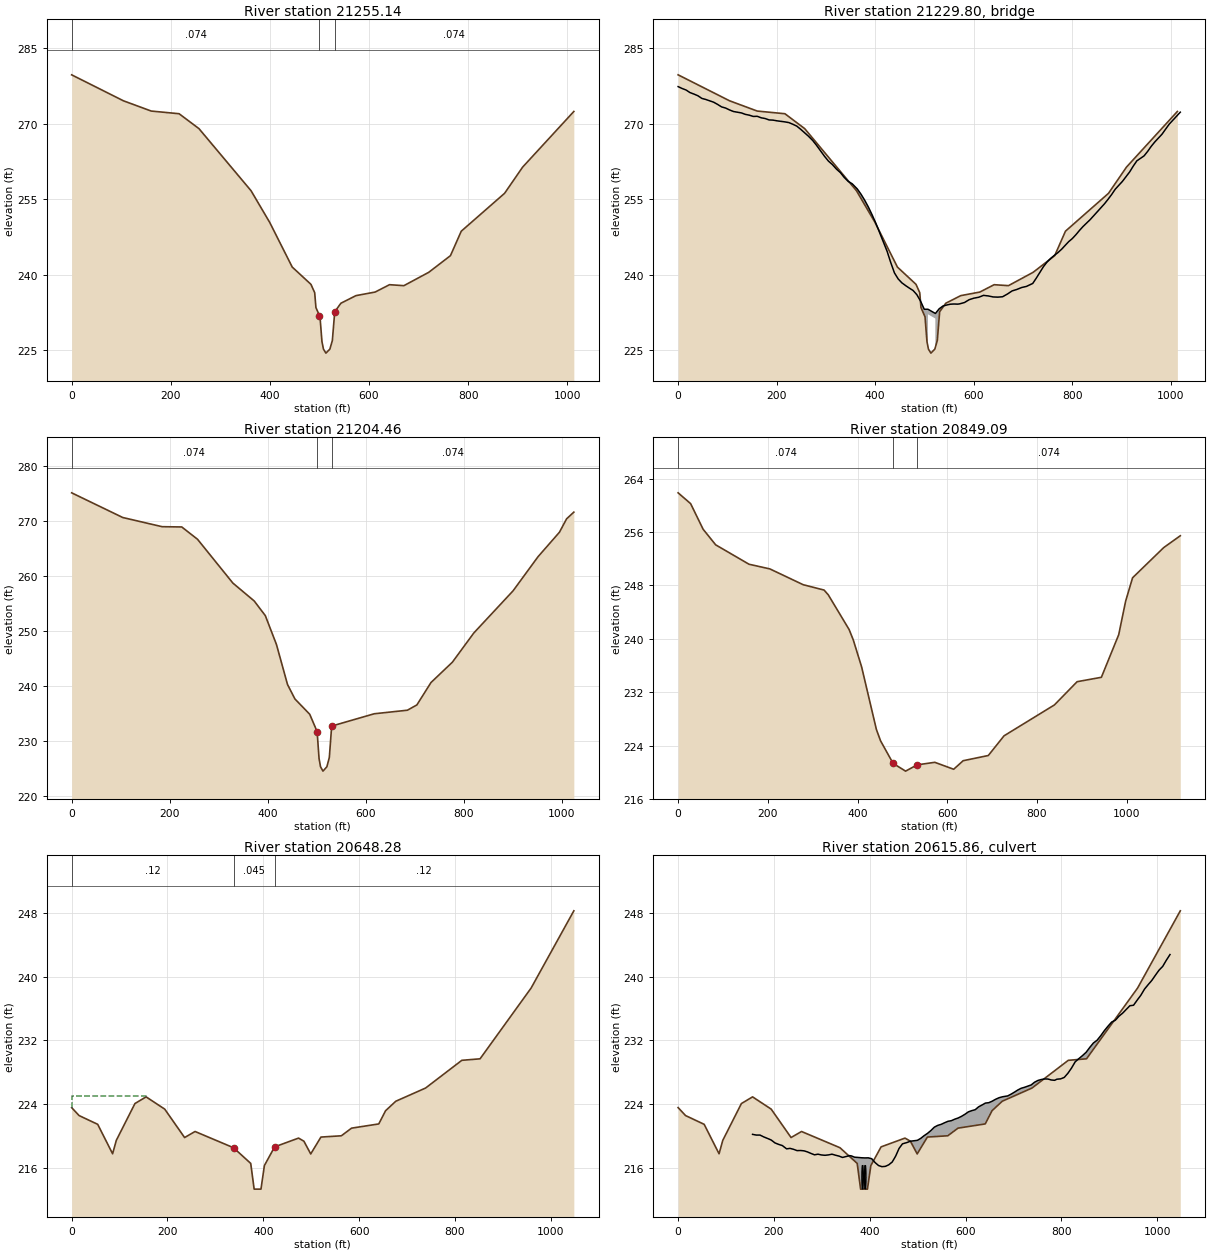
Type RM Length L Ch R = 1 ,21255.14,53.98,50.68,50.1
XS GIS Cut Line= 5
1578035.04251985704139.8739227651577719.43471602703962.648002163
1577523.28766733703883.1960330461577421.82866691703776.905651614
1577140.59281841703695.871593595
#Sta/Elev= 30
       0   279.7  104.37  274.55  160.56  272.51  216.76  271.98   256.9  269.02
  361.96   256.7  399.73  250.39  445.04  241.55   482.8  238.12  490.36  236.47
  492.86  233.51  500.04  231.91  501.08  231.67     505  226.77     508  225.27
     513  224.47     521  225.27     526  226.97  530.79  232.68  543.22  234.37
  573.59  235.88   612.3  236.59  641.33  238.05  670.36  237.86  720.53  240.51
  764.24  243.81  786.09  248.67  873.51  256.19  909.94  261.39 1013.21  272.43
#Mann= 3 , 0 , 0
       0    .074       0  500.04    .045       0  530.79    .074       0
Bank Sta=500.04,530.79
XS Rating Curve= 0 ,0
Exp/Cntr=0.5,0.3

Type RM Length L Ch R = 3 ,21229.80,,,
BEGIN DESCRIPTION:
private drive
MDE Bridge #CE032707FS-10
Bridge Deck taken from DEM
Bridge Opening from surveys
END DESCRIPTION:
Bridge Culvert--1,0,-1,-1, 0
Deck Dist Width WeirC Skew NumUp NumDn MinLoCord MaxHiCord MaxSubmerge Is_Ogee
15,17,2.6,0, 132, 133, , , 0.98, 0, 0,0,,
       0    8.03   16.06   24.08   32.11   40.14   48.17    56.2   64.23   72.25
   80.28   88.31   96.34  104.37  112.39  120.42  128.45  136.48  144.51  152.53
  160.56  168.59  176.62  184.65  192.68   200.7  208.73  216.76  224.79  232.82
  240.84  248.87   256.9  264.93  272.96  280.98  289.01  297.04  305.07   313.1
  321.13  329.15  337.18  345.21  353.24  363.55   371.1  378.66  386.21  393.76
  401.31  408.87  416.42  423.97  431.52  439.07  446.63  454.18  461.73  469.28
  476.84  484.39  491.94  499.49     507     507     522     522  522.15   529.7
  537.26  544.81  552.36  559.91  567.47  571.39  581.06  590.74  600.42   610.1
  619.77  629.45  639.13   648.8  658.48  668.16  677.84  687.51  697.19  706.87
  719.71  726.99  734.28  741.56  748.85  756.13  763.42   770.7  777.99  785.27
  792.56  799.84  807.13  814.41   821.7  828.98  836.27  843.55  850.84  858.12
   865.4  872.69  879.97  887.26  894.54  901.83  909.11   916.4  923.68  930.97
  938.25  945.54  952.82  960.11  967.39  974.68  981.96  989.25  996.53 1003.82
  1011.1 1019.15
  277.36  276.99  276.69  276.18  275.88  275.55  275.02  274.81  274.54  274.26
  273.82  273.33  273.11  272.73  272.42  272.27  272.14  271.85  271.69  271.44
  271.47  271.17  271.03  270.75  270.71  270.57  270.47  270.36  270.22  269.89
  269.52  268.88  268.18  267.48  266.69   265.7  264.61  263.54  262.58  261.89
  261.01  260.31  259.33  258.55  258.08  257.06  256.02  254.81  253.44   251.9
  250.24  248.41  246.58  244.72  242.44  240.38  239.19  238.41  237.87  237.37
   236.9  236.08  234.81  233.18  233.18  233.18  232.34  232.34  232.34  233.26
  233.81  234.01  234.18  234.22  234.19  234.25  234.51  235.08  235.38  235.56
  235.93  235.82  235.62  235.58  235.66  236.19  236.82  237.11  237.49  237.71
   238.3  239.37  240.53  241.65  242.56  243.27  243.87  244.41  245.06  245.83
  246.59  247.19  247.95  248.81  249.59  250.29  250.97  251.76  252.56  253.32
  254.12  255.02  255.97  257.02  257.79  258.57   259.5  260.44  261.59  262.63
  263.11  263.61   264.5  265.51  266.38  267.14  267.91  268.91   269.9  270.68
  271.48  272.29
                                                                                
                                                                                
                                                                                
                                                                                
                                                                                
                                                                                
                                          232.18  231.34
                                                                                
                                                                                
                                                                                
                                                                                
                                                                                
                                                                                
                
       0    8.03   16.06   24.08   32.11   40.14   48.17    56.2   64.23   72.25
   80.28   88.31   96.34  104.37  112.39  120.42  128.45  136.48  144.51  152.53
  160.56  168.59  176.62  184.65  192.68   200.7  208.73  216.76  224.79  232.82
  240.84  248.87   256.9  264.93  272.96  280.98  289.01  297.04  305.07   313.1
  321.13  329.15  337.18  345.21  353.24  363.55   371.1  378.66  386.21  393.76
  401.31  408.87  416.42  423.97  431.52  439.07  446.63  454.18  461.73  469.28
  476.84  484.39  491.94  499.49     507     507     522     522  522.15   529.7
  537.26  544.81  552.36  559.91  567.47  571.39  581.06  590.74  600.42   610.1
  619.77  629.45  639.13   648.8  658.48  668.16  677.84  687.51  697.19  706.87
  719.71  726.99  734.28  741.56  748.85  756.13  763.42   770.7  777.99  785.27
  792.56  799.84  807.13  814.41   821.7  828.98  836.27  843.55  850.84  858.12
   865.4  872.69  879.97  887.26  894.54  901.83  909.11   916.4  923.68  930.97
  938.25  945.54  952.82  960.11  967.39  974.68  981.96  989.25  996.53 1003.82
  1011.1 1019.15 1025.08
  277.36  276.99  276.69  276.18  275.88  275.55  275.02  274.81  274.54  274.26
  273.82  273.33  273.11  272.73  272.42  272.27  272.14  271.85  271.69  271.44
  271.47  271.17  271.03  270.75  270.71  270.57  270.47  270.36  270.22  269.89
  269.52  268.88  268.18  267.48  266.69   265.7  264.61  263.54  262.58  261.89
  261.01  260.31  259.33  258.55  258.08  257.06  256.02  254.81  253.44   251.9
  250.24  248.41  246.58  244.72  242.44  240.38  239.19  238.41  237.87  237.37
   236.9  236.08  234.81  233.18  233.18  233.18  232.34  232.34  232.34  233.26
  233.81  234.01  234.18  234.22  234.19  234.25  234.51  235.08  235.38  235.56
  235.93  235.82  235.62  235.58  235.66  236.19  236.82  237.11  237.49  237.71
   238.3  239.37  240.53  241.65  242.56  243.27  243.87  244.41  245.06  245.83
  246.59  247.19  247.95  248.81  249.59  250.29  250.97  251.76  252.56  253.32
  254.12  255.02  255.97  257.02  257.79  258.57   259.5  260.44  261.59  262.63
  263.11  263.61   264.5  265.51  266.38  267.14  267.91  268.91   269.9  270.68
  271.48  272.29  271.66
                                                                                
                                                                                
                                                                                
                                                                                
                                                                                
                                                                                
                                          232.18  231.34
                                                                                
                                                                                
                                                                                
                                                                                
                                                                                
                                                                                
                        
BR Coef=-1 , 0 , 0 ,, 0 ,,,0.8,0,,0,
WSPro=,,,, 1 ,,,, 0 ,,,, 0 ,,,,-1 ,-1 ,-1 , 0 , 0 , 0 , 0 , 0
BC Design=,, 0 ,, 0 ,,,,,,
BC Use User HTab Curves=0
BC User HTab FreeFlow(D)= 0

Type RM Length L Ch R = 1 ,21204.46,290.3,355.37,242.33
XS GIS Cut Line= 5
1578059.52373111704096.2772451941577741.14829612703917.497193262
1577552.02860747703840.8917496951577448.66225384703732.603188783
1577154.43639319703647.826245874
#Sta/Elev= 30
       0  275.18  104.37  270.68  184.65  269.01  224.79  268.96   256.9  266.72
  329.15  258.73  372.69  255.47  395.35   252.8     418  247.56  440.66  240.25
  455.77  237.62  485.98  234.83  501.08  231.67     505  226.77     508  225.27
     513  224.47     521  225.27     526  226.97  530.79  232.68  617.57  234.92
  685.31  235.57  704.66  236.53  733.46  240.61  777.16  244.32  820.87  249.64
  901.01  257.32     952  263.54  995.71     268 1010.28  270.44 1025.08  271.66
#Mann= 3 , 0 , 0
       0    .074       0  501.08    .045       0  530.79    .074       0
Bank Sta=501.08,530.79
XS Rating Curve= 0 ,0
Exp/Cntr=0.5,0.3

Type RM Length L Ch R = 1 ,20849.09,292.74,200.81,78.77
XS GIS Cut Line= 5
1578280.57311256 704046.452722521577954.76907104 703761.55365555
1577833.89565381 703655.855998681577569.23880047703675.095668837
1577332.83278328703564.559448555
#Sta/Elev= 30
       0  261.87    27.9  260.25   55.79  256.41   83.69  254.08  158.08  251.17
  204.57  250.47  278.97   248.1  325.46   247.3  334.76  246.59  381.25  241.39
  390.55  239.83  409.15  235.79   442.1  226.41   451.4  224.71  479.29  221.33
  507.19  220.17  533.09  221.11  572.28  221.49  614.42  220.45  635.48  221.73
  691.63  222.51  726.72  225.46  839.02  230.09  889.63  233.57  943.73  234.23
  982.36  240.61  997.82  245.64 1013.27  249.14 1082.82  253.67  1119.7  255.44
#Mann= 3 , 0 , 0
       0    .074       0  479.29    .045       0  533.09    .074       0
Bank Sta=479.29,533.09
XS Rating Curve= 0 ,0
Exp/Cntr=0.5,0.3

Type RM Length L Ch R = 1 ,20648.28,74.1,69.86,93.11
XS GIS Cut Line= 6
1578396.47765486703434.2410979571578190.67575933703533.330899477
1578058.02731515703572.0596143751577740.00100313703628.765030324
 1577623.0317878703631.364346266 1577401.0446948703536.583340228
#Sta/Elev= 30
       0  223.54   15.54  222.54   54.38  221.44   85.46  217.74   93.23  219.43
  132.08  224.05  155.38  224.89  194.23  223.35  235.71  219.78  257.58  220.54
   337.8   218.5  373.73  216.53  380.86   213.3  395.11   213.3  402.24  216.26
  423.62  218.61  473.51  219.71  484.73  219.32  498.93  217.72  520.23  219.84
  562.84     220  584.14  220.96  640.96  221.49  655.16  223.15  676.46  224.34
  738.67     226  814.27  229.48  852.33  229.67  958.88  238.56 1048.03  248.26
#Mann= 3 , 0 , 0
       0     .12       0   337.8    .045       0  423.62     .12       0
#XS Ineff= 2 , 0
       0  155.38     225               0
Permanent Ineff=
       F       F
Bank Sta=337.8,423.62
XS Rating Curve= 0 ,0
Exp/Cntr=0.5,0.3

Type RM Length L Ch R = 2 ,20615.86,,,
BEGIN DESCRIPTION:
Jackson Station Rd
MDE Bridge #CE032707FS-15
Bridge Deck taken from DEM
Bridge Opening from surveys
END DESCRIPTION:
Bridge Culvert--1,0,-1,-1, 0
Deck Dist Width WeirC Skew NumUp NumDn MinLoCord MaxHiCord MaxSubmerge Is_Ogee
26,22,2.6,0, 120, 134, , , 0.98, 0, 1.5,1.5,,
  155.38  163.15  170.92  178.69  186.46  194.23     202  209.77  217.54  226.35
  233.64  240.94  248.23  255.52  262.81  270.11   277.4  284.69  291.98  299.27
  306.57  313.86  321.15  328.44  335.74  343.03  350.32  357.61  361.29  368.42
  375.54  382.67   389.8  396.92  404.05  411.18  418.31  425.43  432.56  439.69
  446.82  453.94  461.07   468.2  477.98  484.73  499.28  506.38  513.48  520.58
  527.69  534.79  541.89  548.99  556.09  563.19  570.29  577.39   584.5   591.6
   598.7   605.8   612.9     620   627.1   634.2  641.31  648.41  655.51  662.61
  669.71  676.81  680.82  687.82  694.82  701.82  708.83  715.83  722.83  729.83
  736.83  743.83  750.84  757.84  764.84  771.84  778.84  785.84  790.57  798.18
   805.8  813.41  821.02  828.63  836.24  843.85  851.46  859.08  866.69   874.3
  881.91  889.52  897.13  904.74  912.35  919.97  927.58  935.19   942.8  950.41
  958.02  965.63  973.25  980.86  988.47  996.08 1003.69  1011.3 1018.91 1026.54
  220.18  220.09  220.09  219.86  219.67  219.47  219.11  218.92  218.77  218.36
  218.42   218.3  218.14  218.15  218.11  217.97  217.78  217.61  217.69  217.59
  217.55   217.6  217.69  217.56  217.45  217.28  217.39  217.51  217.48  217.31
  217.28  217.24  217.22  217.23  217.12  216.63  216.26  216.12  216.16  216.36
  216.71  217.44  218.41  218.99  219.16  219.32  219.43  219.68  220.02  220.31
  220.67  221.09  221.31  221.44  221.64  221.82   221.9  222.09  222.24  222.45
  222.71  223.01  223.16  223.28  223.64  223.87  224.11  224.16  224.35  224.59
  224.78   224.9  224.94  225.01  225.23  225.48  225.75  225.97  226.09  226.24
  226.39  226.73  226.95  227.07  227.14  227.13  227.01  226.97  227.11  227.15
  227.33  227.85  228.51  229.29  229.69  230.07  230.49   231.1  231.66     232
  232.57  233.21  233.77  234.29  234.51  235.02   235.4  235.87  236.34   236.4
  237.04  237.65  238.42  238.98  239.51  240.17  240.81  241.28  242.06  242.77
                                                                                
                                                                                
                                                                                
                                                                                
                                                                                
                                                                                
                                                                                
                                                                                
                                                                                
                                                                                
                                                                                
                                                                                
       0    7.77   15.54   23.31   31.08   38.85   46.61   54.38   62.15   69.92
   77.69   85.46   93.23     101  108.77  116.54  124.31  132.08  139.84  147.61
  155.38  163.15  170.92  178.69  186.46  194.23     202  209.77  217.54  226.35
  233.64  240.94  248.23  255.52  262.81  270.11   277.4  284.69  291.98  299.27
  306.57  313.86  321.15  328.44  335.74  343.03  350.32  357.61  361.29  368.42
  375.54  382.67   389.8  396.92  453.94  461.07   468.2  477.98  485.08  492.18
  499.28  506.38  513.48  520.58  527.69  534.79  541.89  548.99  556.09  563.19
  570.29  577.39   584.5   591.6   598.7   605.8   612.9     620   627.1   634.2
  641.31  648.41  655.51  662.61  669.71  676.81  680.82  687.82  694.82  701.82
  708.83  715.83  722.83  729.83  736.83  743.83  750.84  757.84  764.84  771.84
  778.84  785.84  790.57  798.18   805.8  813.41  821.02  828.63  836.24  843.85
  851.46  859.08  866.69   874.3  881.91  889.52  897.13  904.74  912.35  919.97
  927.58  935.19   942.8  950.41  958.02  965.63  973.25  980.86  988.47  996.08
 1003.69  1011.3 1018.91 1026.54
  225.02   224.5   223.9  223.48  223.13  222.88   222.5  222.12  221.83  221.33
  221.06  221.12  221.02  220.92  220.75  220.72  220.71  220.51  220.33  220.28
  220.18  220.09  220.09  219.86  219.67  219.47  219.11  218.92  218.77  218.36
  218.42   218.3  218.14  218.15  218.11  217.97  217.78  217.61  217.69  217.59
  217.55   217.6  217.69  217.56  217.45  217.28  217.39  217.51  217.48  217.31
  217.28  217.24  217.22  217.23  217.44  218.41  218.99  219.16  219.01   219.1
  219.43  219.68  220.02  220.31  220.67  221.09  221.31  221.44  221.64  221.82
   221.9  222.09  222.24  222.45  222.71  223.01  223.16  223.28  223.64  223.87
  224.11  224.16  224.35  224.59  224.78   224.9  224.94  225.01  225.23  225.48
  225.75  225.97  226.09  226.24  226.39  226.73  226.95  227.07  227.14  227.13
  227.01  226.97  227.11  227.15  227.33  227.85  228.51  229.29  229.69  230.07
  230.49   231.1  231.66     232  232.57  233.21  233.77  234.29  234.51  235.02
   235.4  235.87  236.34   236.4  237.04  237.65  238.42  238.98  239.51  240.17
  240.81  241.28  242.06  242.77
                                                                                
                                                                                
                                                                                
                                                                                
                                                                                
                                                                                
                                                                                
                                                                                
                                                                                
                                                                                
                                                                                
                                                                                
                                                                                
                                
BR Coef=-1 , 0 , 0 ,, 0 ,,,0.8,0,,0,
WSPro=,,,, 1 ,,,, 0 ,,,, 0 ,,,,-1 ,-1 ,-1 , 0 , 0 , 0 , 0 , 0
Multiple Barrel Culv=1,3,,50,0.025,0.9,1,2,3,213.3,213.2, 2,Culvert #1  , 0 ,10
     385     390   390.5   395.5
Culvert Bottom n=0.025
BC Design=,, 0 ,, 0 ,,,,,,
BC Use User HTab Curves=0
BC User HTab FreeFlow(D)= 0

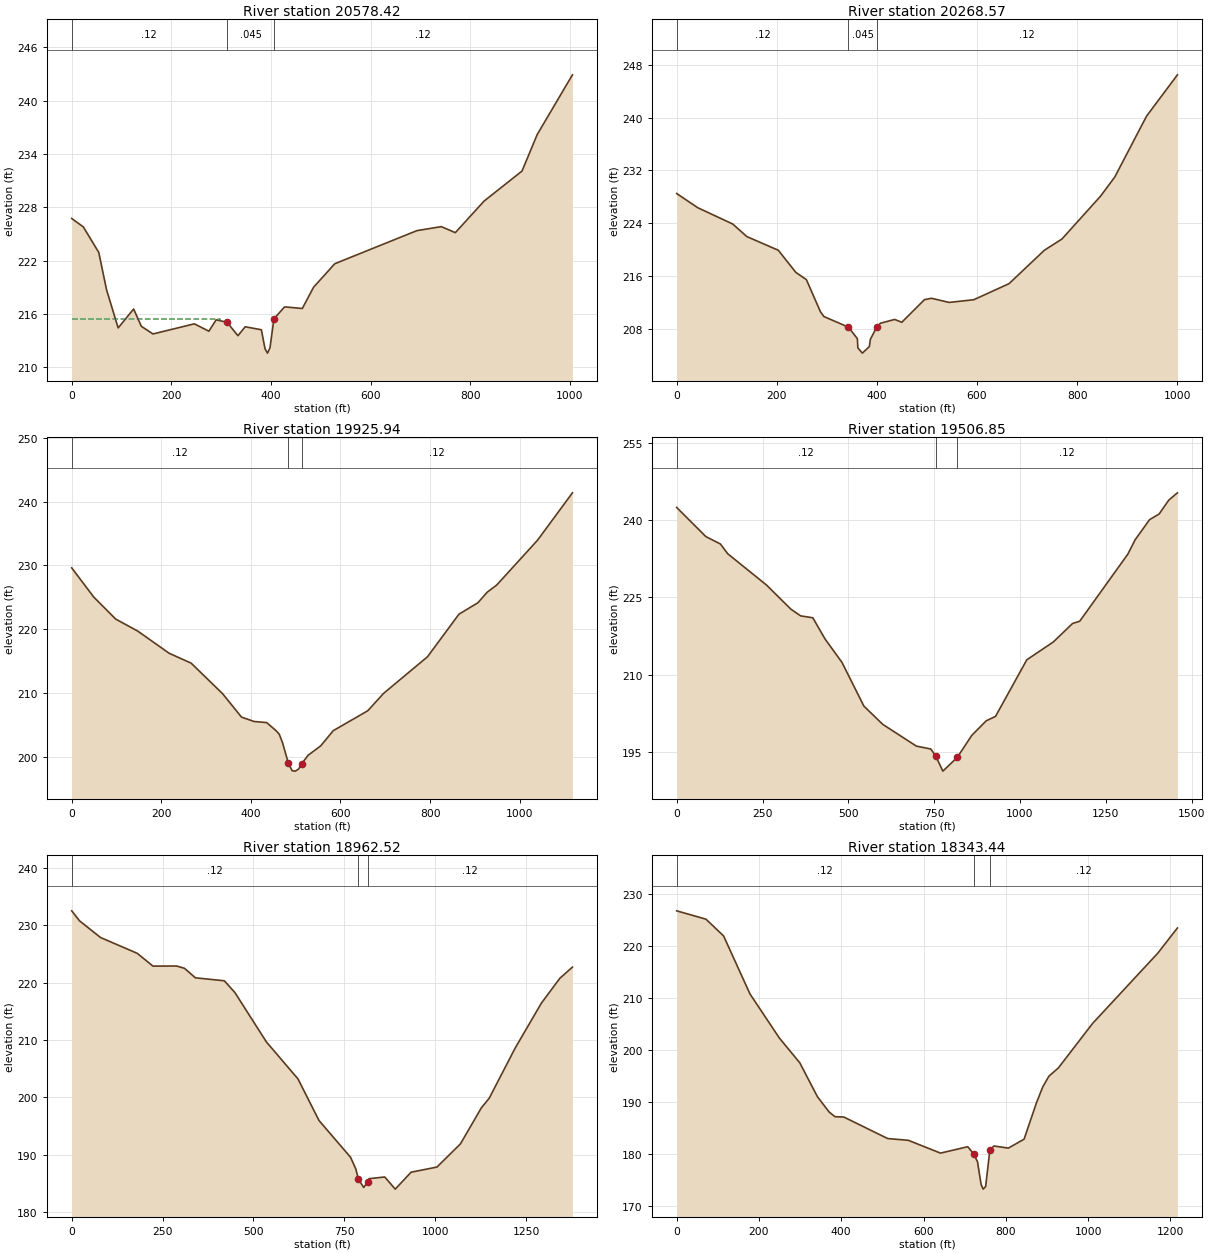
Type RM Length L Ch R = 1 ,20578.42,274.23,309.86,353.05
XS GIS Cut Line= 6
1578371.76549211 703369.55203262  1578169.680842703466.852049336
1578043.27114229703503.7592686561577732.19100975703559.220117956
 1577629.7044885703561.4975962491577417.65690266703470.960424706
#Sta/Elev= 30
       0  226.74   23.31  225.79   54.38  222.91   69.92  218.72   93.23  214.41
  124.31  216.54  139.84  214.59  163.15  213.73  246.17  214.87  275.33  214.04
  289.92  215.32   311.8  215.05  333.67  213.53  348.26  214.54  380.71   214.2
     388  212.07     393  211.57     398  212.17  405.87  215.43  427.25  216.78
  462.88   216.6  485.43  218.99  528.04  221.64  692.98  225.37  741.99  225.82
     770  225.14  827.77   228.7  903.88  232.08  934.33  236.19 1005.06  242.92
#Mann= 3 , 0 , 0
       0     .12       0   311.8    .045       0  405.87     .12       0
#XS Ineff= 2 , 0
       0  297.21  215.38               0
Permanent Ineff=
       F       F
Bank Sta=311.8,405.87
XS Rating Curve= 0 ,0
Exp/Cntr=0.5,0.3

Type RM Length L Ch R = 1 ,20268.57,298.37,342.61,343.93
XS GIS Cut Line= 4
1578436.93945797703211.5662018951578087.10283078703200.633807302
1577972.31268749703222.498596489 1577442.0915494703162.370426193
#Sta/Elev= 30
       0  228.48   42.02  226.33  112.05  223.85  140.07  221.95   203.1  219.87
  238.12  216.51  259.13  215.42  287.14  210.56  294.14  209.82  343.17  208.21
     361  206.47     362  205.07     371  204.27     385  205.27     387  206.37
  399.89  208.25  407.01   208.8  435.52  209.38  449.77  208.95  495.04  212.38
  509.13  212.59  544.35  211.96  593.67  212.37  664.12  214.81  734.57  219.87
  769.79  221.58  847.28  228.11  875.46     231  938.87  240.22 1000.48  246.48
#Mann= 3 , 0 , 0
       0     .12       0  343.17    .045       0  399.89     .12       0
Bank Sta=343.17,399.89
XS Rating Curve= 0 ,0
Exp/Cntr=0.3,0.1

Type RM Length L Ch R = 1 ,19925.94,424.7,419.1,405.56
XS GIS Cut Line= 4
1578582.57972936702934.8785857111578135.00967033702901.370666876
1578058.42014155702882.2232846771577469.63813883702843.928520262
#Sta/Elev= 30
       0   229.6   49.14  225.03   98.27  221.57  147.41  219.69  217.61  216.21
  266.74  214.66  336.94  209.87  379.06  206.21  407.14  205.52  435.21  205.35
  456.04  204.09  463.25  203.54  470.47  202.23  483.22  199.09  492.12   197.8
  499.33  197.74  506.55  198.07  513.29  198.88  527.77  200.23  555.83   201.7
  583.89  204.08  661.05  207.21  696.12  209.92  794.33  215.67  864.48  222.34
  906.57  224.12  927.61  225.79  948.66   226.9 1039.85  233.93 1117.79  241.36
#Mann= 3 , 0 , 0
       0     .12       0  483.22    .045       0  513.29     .12       0
Bank Sta=483.22,513.29
XS Rating Curve= 0 ,0
Exp/Cntr=0.3,0.1

Type RM Length L Ch R = 1 ,19506.85,513.7,544.32,556.78
XS GIS Cut Line= 4
1578908.11189672702579.2408866581578314.86174646702488.681041539
1577993.68750985702471.6623747351577457.60724992702443.256076023
#Sta/Elev= 30
       0  242.43   84.97  236.78  127.46  235.34   148.7  233.45     262  227.36
  332.81  222.69  361.14   221.4  396.54  221.03  431.95  216.94  481.51  212.37
  545.24   203.9  600.12  200.36  698.26  196.13  740.32  195.57  754.34  194.23
  775.37  191.28  817.43  193.96  859.49  198.21  901.55  201.04  928.76   201.9
 1019.89  212.88 1096.99  216.33 1153.07  219.92  1174.1  220.37  1314.3  233.39
 1335.32  236.15 1377.38  240.06 1405.42  241.17 1433.46  243.86 1458.58  245.27
#Mann= 3 , 0 , 0
       0     .12       0  754.34    .045       0  817.43     .12       0
Bank Sta=754.34,817.43
XS Rating Curve= 0 ,0
Exp/Cntr=0.3,0.1

Type RM Length L Ch R = 1 ,18962.52,425.35,619.09,428.23
XS GIS Cut Line= 4
1578950.79429699 702146.437371091578641.64160086702069.149197042
1577984.69212151701897.1830098031577614.60101931701810.862705514
#Sta/Elev= 30
       0  232.53   21.65  230.78   79.37  227.87  180.39  225.11  223.68  222.88
  288.62   222.9  310.26   222.5  340.37  220.84  419.97  220.32  448.91  218.28
  535.74  209.65  622.57   203.2  680.46  195.94  767.29  189.52  781.76  187.47
     789   185.7  803.47  184.24  813.99  185.23  817.94  185.78  861.36  186.08
   890.3  183.96  933.71  186.91 1004.94  187.81 1069.63  191.86 1127.13  198.14
  1148.7  199.82 1220.57  208.62 1292.45  216.43 1342.77  220.73 1377.77  222.71
#Mann= 3 , 0 , 0
       0     .12       0     789    .045       0  813.99     .12       0
Bank Sta=789,813.99
XS Rating Curve= 0 ,0
Exp/Cntr=0.3,0.1

Type RM Length L Ch R = 1 ,18343.44,590.48,764.19,689.56
XS GIS Cut Line= 4
1578802.34593293701642.4566355791578107.31245628701510.249180794
1577986.43706904701525.3586042081577627.58826318701378.041725993
#Sta/Elev= 30
       0  226.73   71.26  225.12  114.01   221.9  178.14  210.74  249.39  202.27
  299.27  197.48  342.02  190.97  370.53  188.02  384.78  187.11  406.15  187.05
  513.04   182.9  562.92  182.57   641.3   180.1   707.5  181.33   721.6  179.99
  731.31  178.42     740  174.07     745  173.17     751  173.67  761.25  180.65
  770.99  181.47  806.26  181.07  844.45  182.78  874.71  189.81  889.85  192.84
  904.98  194.92  927.68  196.48 1010.92  205.05 1169.82  218.61 1217.22  223.43
#Mann= 3 , 0 , 0
       0     .12       0   721.6    .045       0  761.25     .12       0
Bank Sta=721.6,761.25
XS Rating Curve= 0 ,0
Exp/Cntr=0.3,0.1

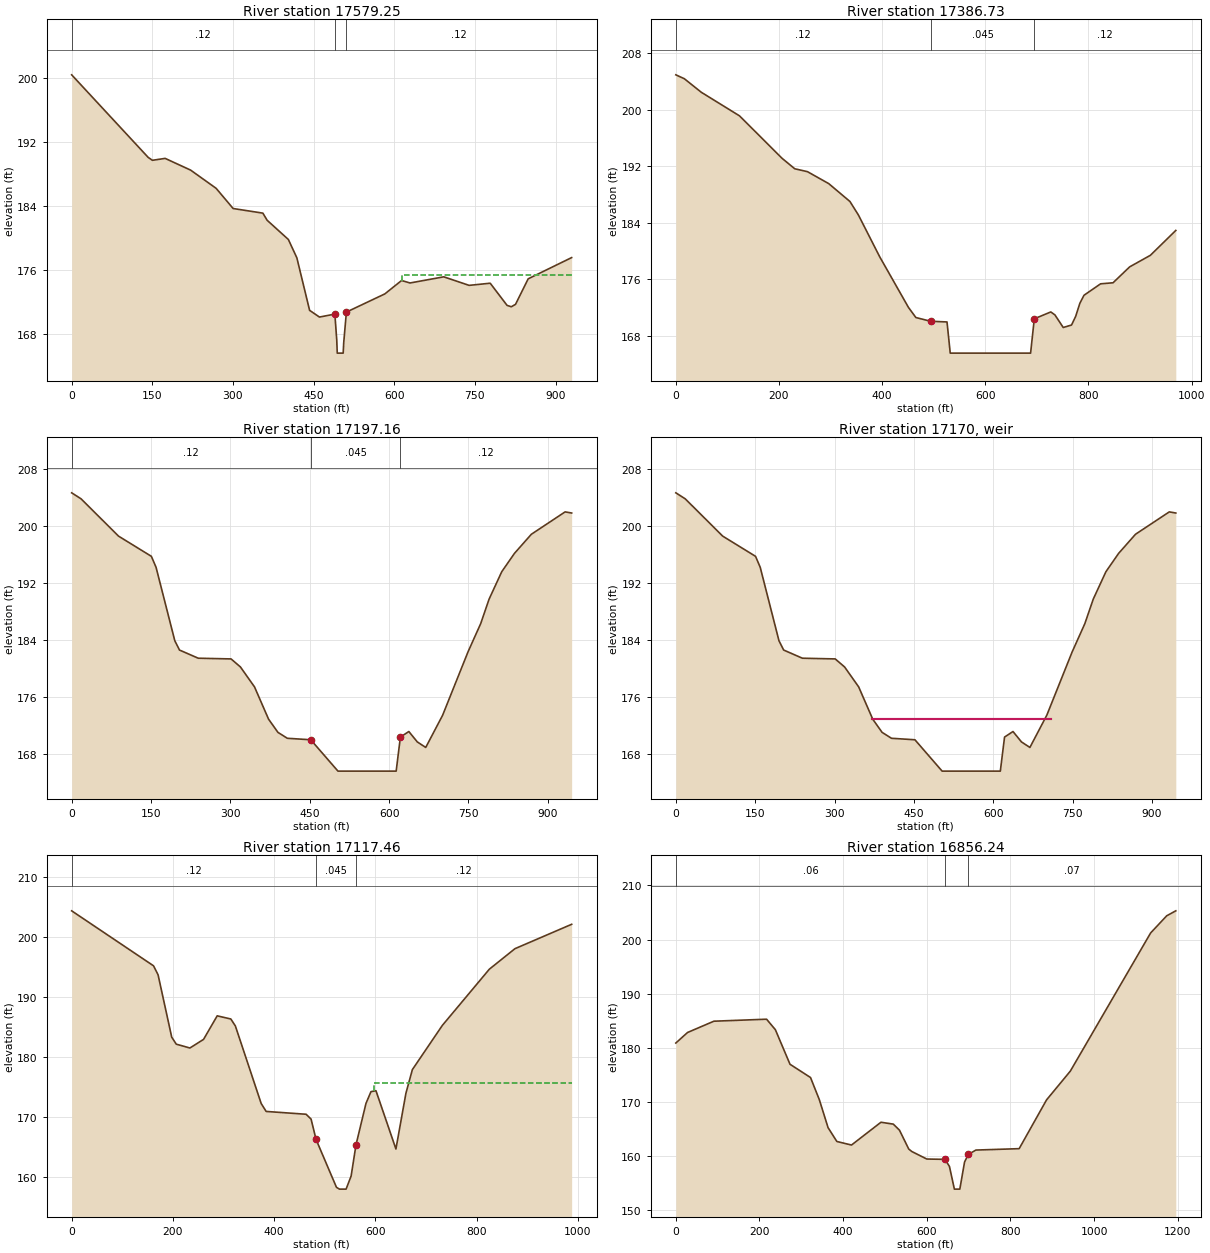
Type RM Length L Ch R = 1 ,17579.25,202.77,192.52,184.37
XS GIS Cut Line= 4
1579076.38757983701361.9624045941578674.48907481701151.352130309
1578517.98052236 701118.504656361578235.87868716700975.521534383
#Sta/Elev= 30
       0  200.44  142.25   190.1  150.16  189.73  173.86  189.97  221.28   188.5
   268.7  186.22  300.31  183.69  355.63  183.11  363.53  182.22  403.05  179.81
  418.85  177.51  442.56  170.93  460.89  170.09   489.5  170.46     493  167.27
     494  165.57     505  165.57     506  166.87  510.96  170.71  582.48  172.99
  613.66  174.67  629.35  174.36  692.14  175.13  739.22  174.06  778.46  174.33
  809.85  171.55   817.7  171.38  825.55  171.68  849.09  174.88  929.93  177.54
#Mann= 3 , 0 , 0
       0     .12       0   489.5    .045       0  510.96     .12       0
#XS Ineff= 2 , 0
                          615.18          175.39
Permanent Ineff=
       F       F
Bank Sta=489.5,510.96
XS Rating Curve= 0 ,0
Exp/Cntr=0.3,0.1

Type RM Length L Ch R = 1 ,17386.73,149,189.56,233.87
XS GIS Cut Line= 4
1579151.74354954701211.250465199 1578786.5569272700985.182556137
1578519.91272676700925.2842212621578288.04820462700793.894325405
#Sta/Elev= 30
       0  204.97   16.47  204.42    49.4   202.5  123.49  199.16  205.82  193.16
  230.52  191.67  255.21  191.26  296.38  189.57  337.54  187.04  354.01  185.12
  395.17  179.22  451.02  172.04  465.37  170.61  494.07  170.08  525.74169.9841
     532  165.57  687.78  165.57  694.95  170.43  726.92   171.4  734.97  170.98
  751.06   169.2  767.15  169.55   775.2  170.78  783.24  172.62  791.29  173.76
  823.47  175.38  847.61  175.53  879.79  177.78  920.02  179.42  969.29  182.94
#Mann= 3 , 0 , 0
       0     .12       0  494.07    .045       0  694.95     .12       0
Bank Sta=494.07,694.95
XS Rating Curve= 0 ,0
Exp/Cntr=0.5,0.3

Type RM Length L Ch R = 1 ,17197.16,63.26,79.71,112.07
XS GIS Cut Line= 4
1579188.70098348701116.0509930551578806.36870669700819.315494627
1578758.81494091700786.978933886 1578405.0149236700592.959569559
#Sta/Elev= 30
       0  204.71   17.72  203.87   88.61  198.62  150.64  195.78   159.5  194.24
  194.94  183.91   203.8   182.6  239.24  181.45  301.27  181.35  318.99  180.22
  345.58  177.42  372.16  172.88  389.88  171.02   407.6  170.19  451.91  169.98
  503.33  165.57  613.33  165.57  621.31  170.36  637.28  171.14  653.25  169.68
  669.21   168.9  701.15  173.43  749.05  182.33     773   186.3  788.97  189.76
  812.92  193.62  836.87  196.19   868.8  198.88  932.67  202.03  944.99  201.87
#Mann= 3 , 0 , 0
       0     .12       0  451.91    .045       0  621.31     .12       0
Bank Sta=451.91,621.31
XS Rating Curve= 0 ,0
Exp/Cntr=0.5,0.3

Type RM Length L Ch R = 5 ,17170   ,,,
BEGIN DESCRIPTION:
Reservoir
END DESCRIPTION:
IW Pilot Flow=0
#Inline Weir SE= 2
     370  172.97     710  172.97
IW Dist,WD,Coef,Skew,MaxSub,Min_El,Is_Ogee,SpillHt,DesHd
20,5,2.6,0,0.98,, 0 ,,,0,0,

Type RM Length L Ch R = 1 ,17117.46,423.37,261.22,275.82
XS GIS Cut Line= 4
1579217.43849742 701072.13175194 1578941.1332753700849.928251579
1578715.06536618700625.7925468531578454.21777882700449.961950898
#Sta/Elev= 30
       0  204.43  161.69  195.25  170.67  193.75  197.62  183.34   206.6  182.17
  233.55  181.53   260.5  182.97  287.45   186.9   314.4  186.37  323.38   185.2
  374.28  172.27  384.14  170.94     463  170.47  472.86  169.66  482.71  166.26
     523  158.27     529  157.97     542  157.97     552  160.17  561.57  165.36
  581.29  172.28  591.14  174.24     601   174.4  640.43  164.67  660.14  173.96
  672.91  177.92  732.01  185.29  824.87  194.68  875.52  198.11  987.49  202.18
#Mann= 3 , 0 , 0
       0     .12       0  482.71    .045       0  561.57     .12       0
#XS Ineff= 2 , 0
                          596.54          175.76
Permanent Ineff=
       F       F
Bank Sta=482.71,561.57
XS Rating Curve= 0 ,0
Exp/Cntr=0.5,0.3

Type RM Length L Ch R = 1 ,16856.24,112.22,109.68,80.65
XS GIS Cut Line= 6
1579667.68175755700651.989092708 1579177.2084621700651.989092708
1579090.34673381700623.0351833111578981.81460905700534.695081711
1578864.92647259700346.7516601681578635.11116926700243.109464556
#Sta/Elev= 30
       0  180.84      28  182.79      91  184.88     217  185.25     238  183.31
     273  176.91     322  174.46     343  170.38     364  165.18     385  162.62
     420  161.96  490.47  166.18  519.99  165.83  534.75  164.71  556.88  161.22
  564.26  160.76  600.09  159.37  643.61  159.31  654.24  157.99     666   153.8
     679   153.8  690.34  158.82  699.37  160.23  717.42  161.03  820.88  161.29
  886.41  170.32   943.3  175.65 1135.27  201.22 1173.67  204.39 1195.41  205.31
#Mann= 3 , 0 , 0
       0     .06       0  643.61    .045       0  699.37     .07       0
Bank Sta=643.61,699.37
XS Rating Curve= 0 ,0
Exp/Cntr=0.5,0.3