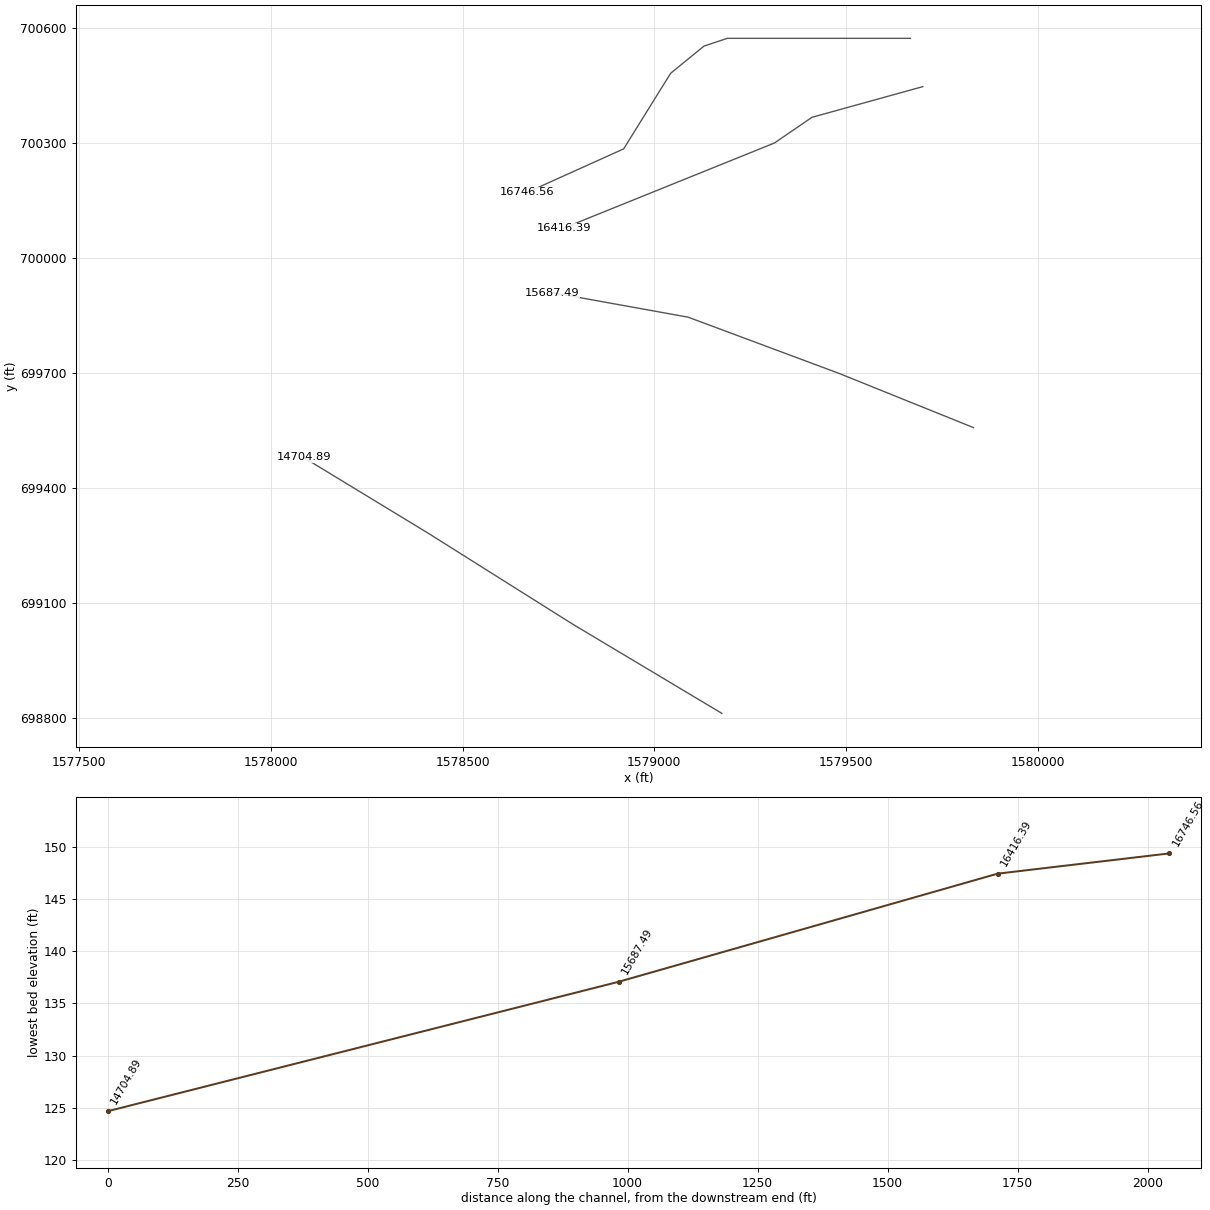
HEC-RAS study MillCreek.prj: MillCreek

--- MillCreek.g01 (geometry) --- (continued)

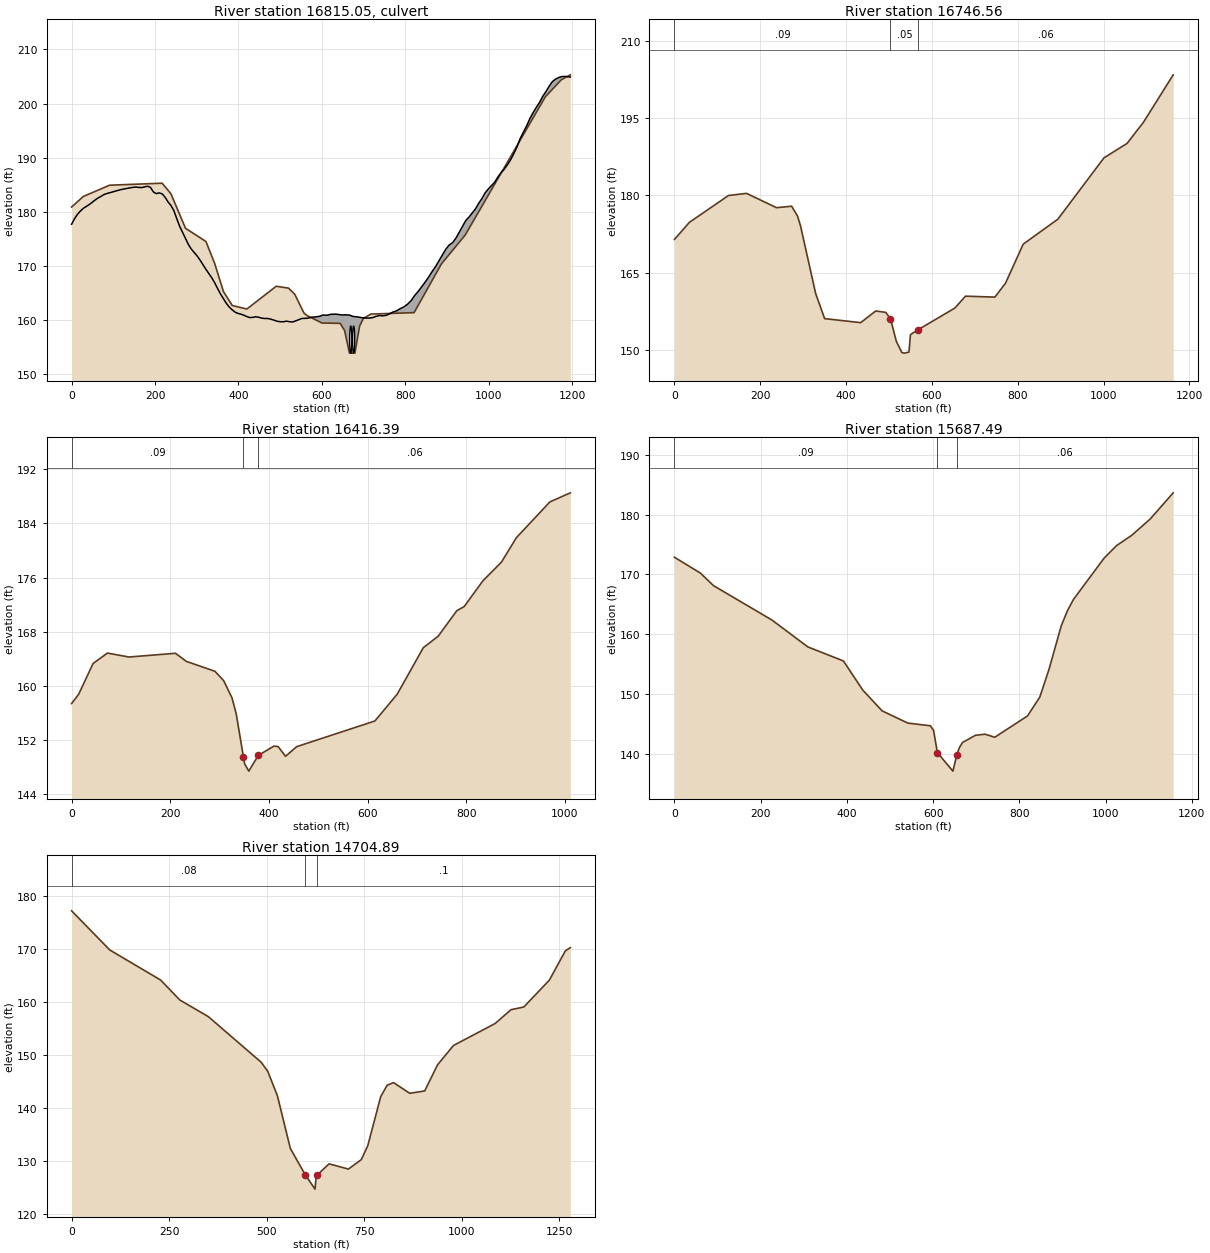
Type RM Length L Ch R = 2 ,16815.05,,,
BEGIN DESCRIPTION:
Reservoir Rd
MDE Bridge #CE032707FS-8
Bridge Deck taken from DEM
Bridge Opening from surveys
END DESCRIPTION:
Bridge Culvert--1,0,-1,-1, 0
Deck Dist Width WeirC Skew NumUp NumDn MinLoCord MaxHiCord MaxSubmerge Is_Ogee
40,25,2.6,0, 157, 156, , , 0.98, 0, 0.5,0.5,,
       0       7      14      21      28      35      42      49      56      63
      70      77      84      91      98     105     112     119     126     133
     140     147     154     161     168     175     182     189     196     203
     210     217     224     231     238     245     252     259     266     273
     280     287     294     301     308     315     322     329     336     343
     350     357     364     371     378     385     392     399     406     413
     420     427     434     441     448     455     462     469     476   485.6
  492.98  500.36  507.74  515.12   522.5  529.88  537.26  544.63  552.01  559.39
  566.82  575.84  584.87  593.89  602.92  611.94  620.97     630  639.02  648.05
  657.07   666.1  675.12  684.15  696.26   704.5  712.74  720.98  729.23  737.47
  745.71  753.95  762.19  770.44  778.68  786.92  797.97  806.21  814.46   822.7
  830.95  839.19  847.43  855.68  863.92  872.17  880.41  888.66   896.9  905.15
  913.39   921.7  929.38  937.06  944.74  952.42   960.1  967.78  975.46  983.13
  990.81  998.49 1006.17 1013.85 1021.53 1029.21 1036.89 1044.57 1052.24 1059.92
  1067.6 1075.28 1082.96 1090.64 1098.32    1106 1113.68 1121.36 1129.03 1136.71
 1144.39 1152.07 1159.75 1167.43 1175.11 1182.93 1195.41
  177.66  178.67  179.48  180.09  180.59  180.94  181.29  181.69  182.12   182.5
  182.79  183.13  183.33  183.47  183.63  183.79  183.94  184.08  184.19  184.29
  184.39  184.48  184.54  184.47  184.44  184.57  184.69  184.48  183.64  183.32
  183.46  183.28  182.67   181.8  181.14  180.19  178.69  177.26  176.13  175.02
  173.89  173.05  172.42  171.77     171  170.14   169.3  168.52  167.73  166.81
  165.73  164.73  163.85     163  162.31   161.8  161.38  161.14  161.01  160.81
  160.57  160.38  160.41  160.53  160.45  160.29  160.21  160.22  160.12  159.89
  159.69  159.61  159.61  159.72  159.61  159.57  159.77     160  160.22  160.23
  160.28  160.45  160.51  160.61  160.86  160.81  160.98  161.02  160.97  160.86
  160.89  160.84  160.58  160.52  160.35  160.29  160.28  160.36  160.59  160.76
  160.71   160.8  161.09  161.42  161.62     162  162.44  162.93  163.59  164.52
  165.24  166.08  166.95  167.88  168.88   169.8  170.88  171.97  173.05  173.82
  174.26  175.16  176.21  177.27  178.35  178.98  179.73  180.48   181.5  182.37
  183.43  184.16   184.8  185.43  186.37  187.19  187.85  188.67  189.59  190.74
  192.01  193.56  194.72  195.87  197.21   198.3  199.27  200.19  201.31  202.19
  203.17  204.04  204.51  204.81  204.99  205.02   204.9
                                                                                
                                                                                
                                                                                
                                                                                
                                                                                
                                                                                
                                                                                
                                                                                
                                                                                
                                                                                
                                                                                
                                                                                
                                                                                
                                                                                
                                                                                
                                                        
       0       7      14      21      28      35      42      49      56      63
      70      77      84      91      98     105     112     119     126     133
     140     147     154     161     168     175     182     189     196     203
     210     217     224     231     238     245     252     259     266     273
     280     287     294     301     308     315     322     329     336     343
     350     357     364     371     378     385     392     399     406     413
     420     427     434     441     448     455     462     469     476   485.6
  492.98  500.36  507.74  515.12   522.5  529.88  537.26  544.63  552.01  559.39
  566.82  575.84  584.87  593.89  602.92  611.94  620.97     630  639.02  648.05
  657.07   666.1  675.12  684.15  696.26   704.5  712.74  720.98  729.23  737.47
  745.71  753.95  762.19  770.44  778.68  786.92  797.97  806.21  814.46   822.7
  830.95  839.19  847.43  855.68  863.92  872.17  880.41  888.66   896.9  905.15
  913.39   921.7  929.38  937.06  944.74  952.42   960.1  967.78  975.46  983.13
  990.81  998.49 1006.17 1013.85 1021.53 1029.21 1036.89 1044.57 1052.24 1059.92
  1067.6 1075.28 1082.96 1090.64 1098.32    1106 1113.68 1121.36 1129.03 1136.71
 1144.39 1152.07 1159.75 1167.43 1175.11 1182.93
  177.66  178.67  179.48  180.09  180.59  180.94  181.29  181.69  182.12   182.5
  182.79  183.13  183.33  183.47  183.63  183.79  183.94  184.08  184.19  184.29
  184.39  184.48  184.54  184.47  184.44  184.57  184.69  184.48  183.64  183.32
  183.46  183.28  182.67   181.8  181.14  180.19  178.69  177.26  176.13  175.02
  173.89  173.05  172.42  171.77     171  170.14   169.3  168.52  167.73  166.81
  165.73  164.73  163.85     163  162.31   161.8  161.38  161.14  161.01  160.81
  160.57  160.38  160.41  160.53  160.45  160.29  160.21  160.22  160.12  159.89
  159.69  159.61  159.61  159.72  159.61  159.57  159.77     160  160.22  160.23
  160.28  160.45  160.51  160.61  160.86  160.81  160.98  161.02  160.97  160.86
  160.89  160.84  160.58  160.52  160.35  160.29  160.28  160.36  160.59  160.76
  160.71   160.8  161.09  161.42  161.62     162  162.44  162.93  163.59  164.52
  165.24  166.08  166.95  167.88  168.88   169.8  170.88  171.97  173.05  173.82
  174.26  175.16  176.21  177.27  178.35  178.98  179.73  180.48   181.5  182.37
  183.43  184.16   184.8  185.43  186.37  187.19  187.85  188.67  189.59  190.74
  192.01  193.56  194.72  195.87  197.21   198.3  199.27  200.19  201.31  202.19
  203.17  204.04  204.51  204.81  204.99  205.02
                                                                                
                                                                                
                                                                                
                                                                                
                                                                                
                                                                                
                                                                                
                                                                                
                                                                                
                                                                                
                                                                                
                                                                                
                                                                                
                                                                                
                                                                                
                                                
BR Coef=-1 , 0 , 0 ,, 0 ,,,0.8,0,,0,
WSPro=,,,, 1 ,,,, 0 ,,,, 0 ,,,,-1 ,-1 ,-1 , 0 , 0 , 0 , 0 , 0
Multiple Barrel Culv=1,5,,30,0.024,0.9,1,2,3,153.8,152.6, 2,Culvert #1  , 0 ,37.5
     669     534     676     542
Culvert Bottom n=0.024
BC Design=,, 0 ,, 0 ,,,,,,
BC Use User HTab Curves=0
BC User HTab FreeFlow(D)= 0

Type RM Length L Ch R = 1 ,16746.56,220.37,330.17,262.32
XS GIS Cut Line= 6
1579667.68175755700571.9890927231579190.19067492700571.989092723
 1579129.5119673700551.7628568411579042.69354045700481.096695468
1578919.99616213700283.8279469461578667.99978951700170.182523996
#Sta/Elev= 30
       0  171.45      35  174.77     126  179.98     168  180.39     238  177.61
     273   177.9     287  175.96     294  174.02     329  160.97     350  156.07
     434  155.29     469  157.55  492.25  157.29  503.44  156.04     517  151.67
     530  149.47     536  149.37   546.5  149.57     550  152.97  568.53  153.95
  653.39  158.12  678.12  160.43  746.75  160.25  771.49  162.96  812.71  170.53
  893.39  175.38 1000.89  187.29 1054.64  190.09 1093.04  194.22 1162.15  203.41
#Mann= 3 , 0 , 0
       0     .09       0  503.44     .05       0  568.53     .06       0
Bank Sta=503.44,568.53
XS Rating Curve= 0 ,0
Exp/Cntr=0.5,0.3

Type RM Length L Ch R = 1 ,16416.39,705.68,728.9,420.92
XS GIS Cut Line= 4
1579699.85275094700446.0964057741579410.92036742700366.124049604
1579312.88973729700299.0504605771578763.40225796700077.191666082
#Sta/Elev= 30
       0   157.4   14.53   158.8   43.58  163.32   72.63  164.85  116.21  164.27
  210.63  164.82  232.42  163.63  290.53  162.17  308.28  160.78  325.24  158.23
  333.72  155.89  348.45  149.48  350.69  148.53  359.17  147.43  378.48  149.75
  410.06  151.12  418.58  151.06  433.67  149.62  456.32  151.04  614.85  154.83
  660.15  158.79  712.99  165.64  743.18  167.34  780.93   171.1  796.03  171.73
  833.77  175.51  871.52  178.28  901.71  181.88  969.65  187.16 1011.16   188.5
#Mann= 3 , 0 , 0
       0     .09       0  348.45     .05       0  378.48     .06       0
Bank Sta=348.45,378.48
XS Rating Curve= 0 ,0
Exp/Cntr=0.3,0.1

Type RM Length L Ch R = 1 ,15687.49,912.38,982.6,875.57
XS GIS Cut Line= 4
1579831.87948108699557.2835407411579482.15049352699698.334458381
1579087.98080592699845.1819890591578734.38740973699908.944732621
#Sta/Elev= 30
       0  172.87   60.38  170.21   90.57  168.12  226.44  162.35  309.46  157.86
  392.04  155.51  436.86  150.64  481.68  147.16  541.44  145.11  593.73  144.66
   601.2  143.88     610  140.17     646  137.07  655.11   139.8  660.96     141
  668.43  141.87  698.31  143.07  720.72  143.25  743.13  142.74  819.07  146.31
  847.53  149.45  868.87  154.09  897.32  161.39  911.54  163.89  925.77  165.82
   996.9  172.73 1025.35   174.8 1060.91  176.54 1103.59  179.26 1157.03  183.65
#Mann= 3 , 0 , 0
       0     .09       0     610     .05       0  655.11     .06       0
Bank Sta=610,655.11
XS Rating Curve= 0 ,0
Exp/Cntr=0.3,0.1

Type RM Length L Ch R = 1 ,14704.89,974.41,1164.17,1084.96
XS GIS Cut Line= 4
1579176.05329055 698812.338522391578787.12173833 699044.93484284
1578411.53587663699281.3442177181578085.51972258699479.623048261
#Sta/Elev= 30
       0  177.27   97.88  169.87  228.38  164.18  277.31  160.42  350.72  157.26
  486.26  148.63   502.8  146.94  527.62   142.3   560.7  132.37  598.74   127.4
     624  124.67  626.87  127.03  628.79  127.28  659.96  129.45  709.58  128.46
  742.67  130.25  759.21  132.88   792.3  142.13  808.84  144.31  825.38   144.8
  866.74  142.78  905.16  143.23  937.94  148.15   978.9  151.82 1085.41  155.96
 1126.37  158.58 1159.15  159.09 1224.69  164.17 1265.66   169.7 1278.55  170.32
#Mann= 3 , 0 , 0
       0     .08       0  598.74     .05       0  628.79      .1       0
Bank Sta=598.74,628.79
XS Rating Curve= 0 ,0
Exp/Cntr=0.3,0.1