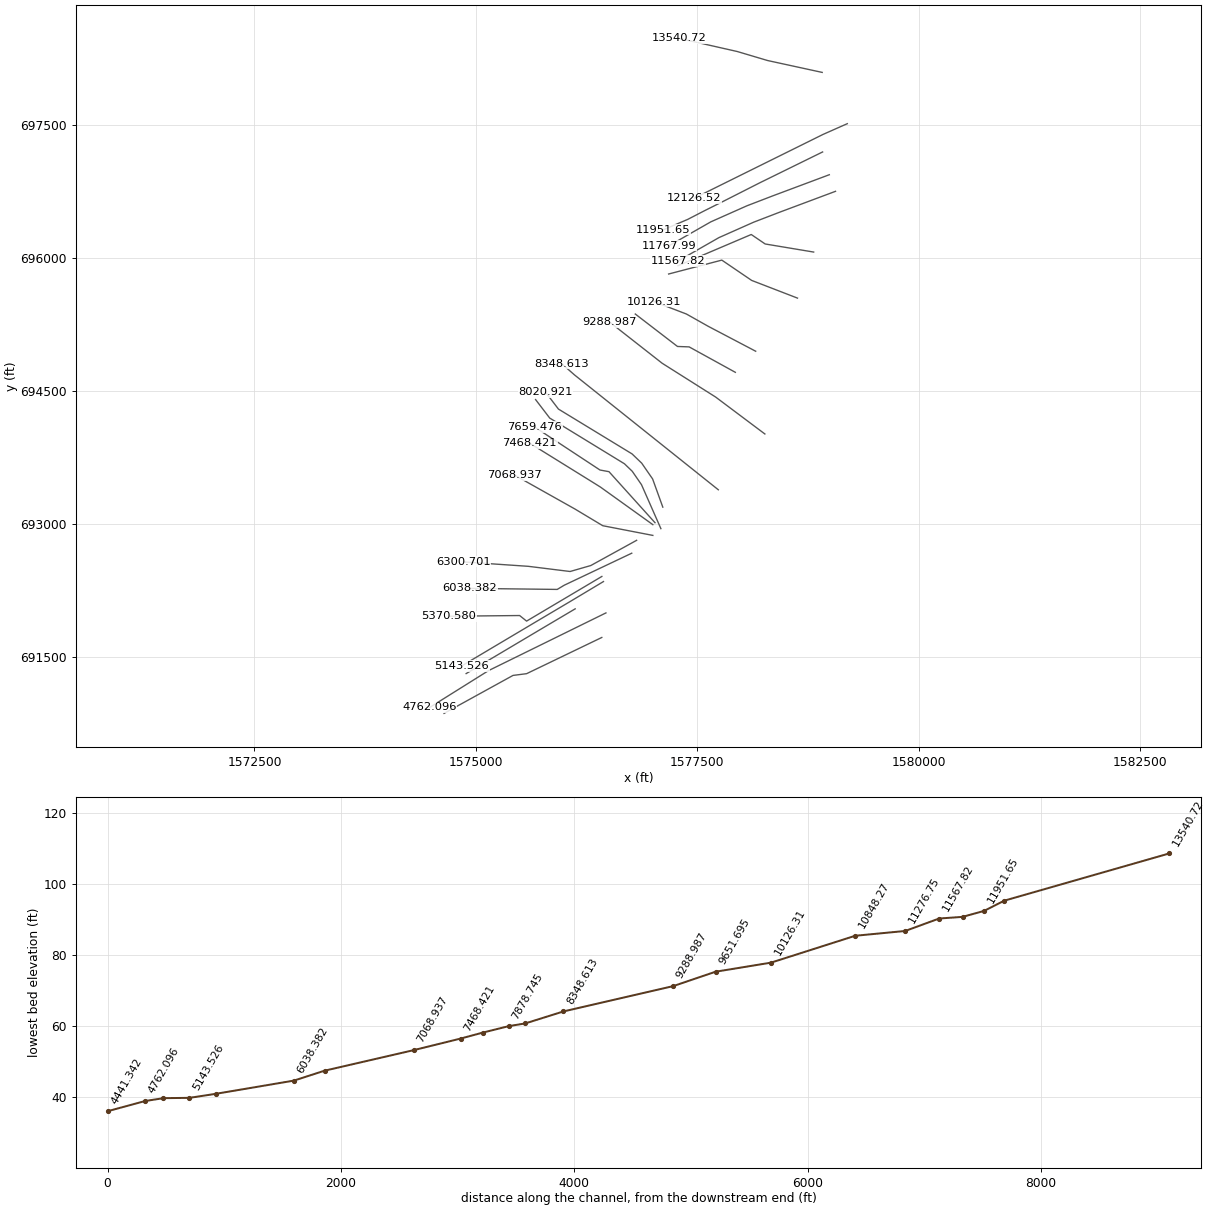
HEC-RAS study MillCreek.prj: MillCreek

--- MillCreek.g01 (geometry) --- (continued)

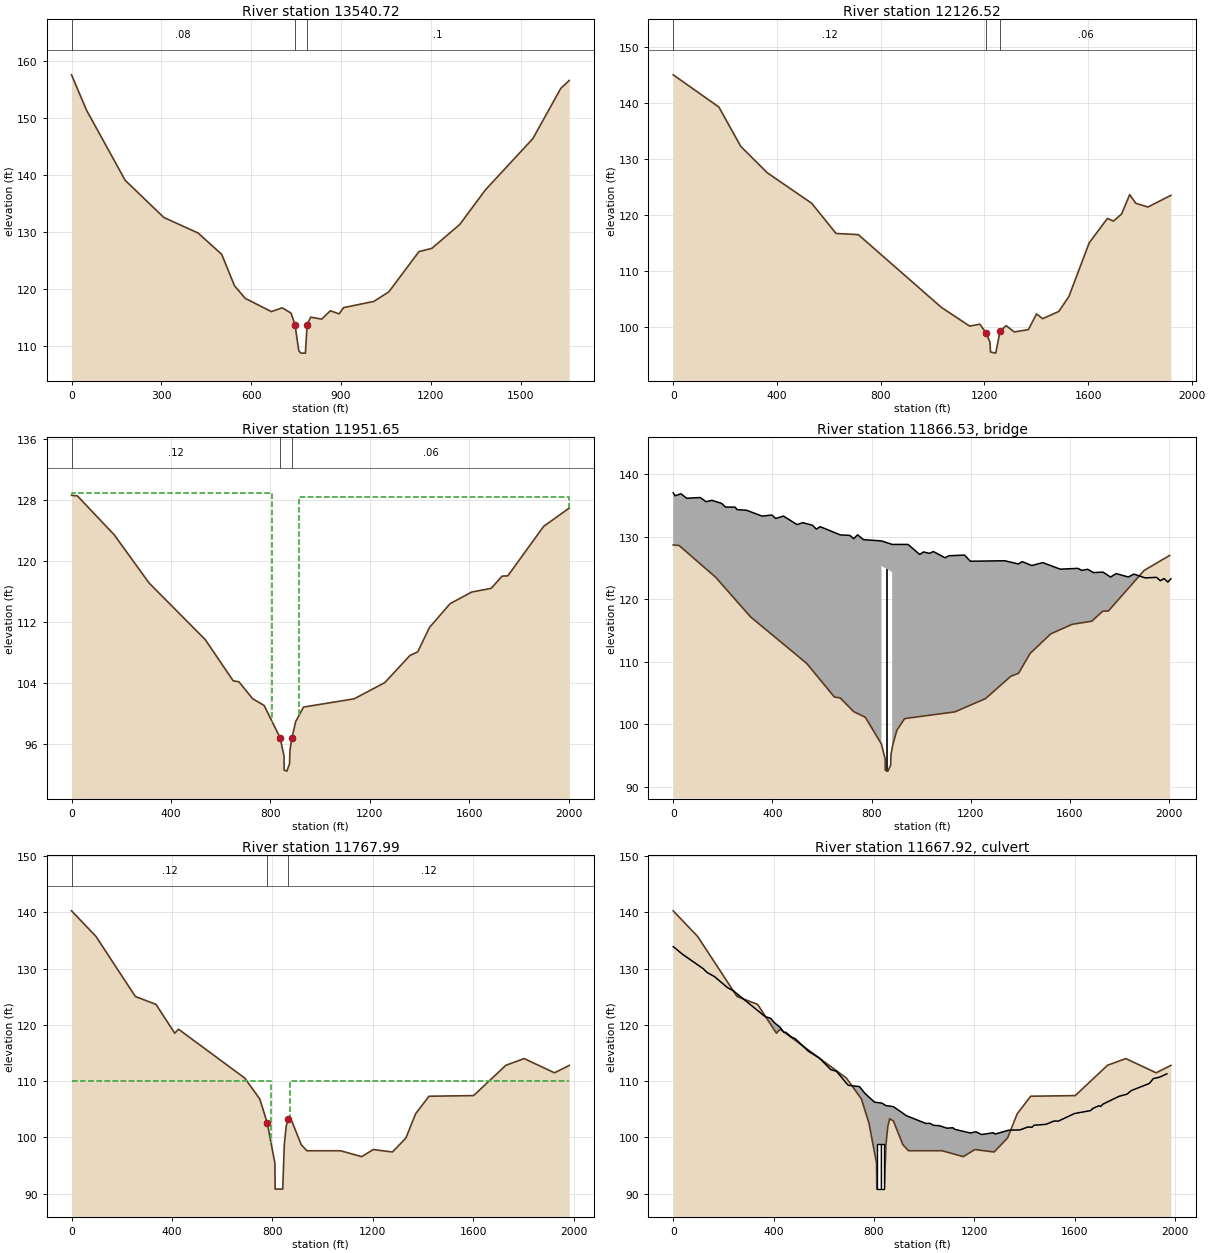
Type RM Length L Ch R = 1 ,13540.72,1167.19,1414.2,1463.72
XS GIS Cut Line= 4
1578909.83231932698094.8880109491578293.43153271698229.048189178
1577951.02289343698330.7782921491577293.49905716698479.651613578
#Sta/Elev= 30
       0  157.54   50.15  151.32   179.1  139.02  308.05   132.5  422.67  129.76
  501.47  126.02  544.45  120.48  580.27  118.28  667.34  115.96  703.86  116.63
  733.07  115.69  746.38  113.64     759  109.07     766  108.67     781  108.67
   786.9  113.69  798.79  114.99   835.3  114.64  864.51  116.11  893.72  115.56
  908.32  116.66 1009.57  117.75 1059.81  119.44 1160.29   126.5 1203.35  127.07
 1296.65  131.27 1382.78  137.37 1540.67  146.34 1633.98  155.16  1662.2  156.55
#Mann= 3 , 0 , 0
       0     .08       0  746.38     .05       0   786.9      .1       0
Bank Sta=746.38,786.9
XS Rating Curve= 0 ,0
Exp/Cntr=0.3,0.1

Type RM Length L Ch R = 1 ,12126.52,179.27,174.87,176.02
XS GIS Cut Line= 3
1579193.07325605697516.0710982831578918.76770228697394.543126106
1577467.37887278696675.793251291
#Sta/Elev= 30
       0  145.04  176.09   139.3  260.31  132.29  362.51  127.57  534.36  122.11
   628.1  116.73  714.02  116.52 1034.29  103.54 1143.64  100.19  1182.7  100.54
 1206.13   99.03 1221.76   97.34    1224   95.57    1244   95.37 1260.81    99.3
 1284.25  100.27 1315.49   99.15 1370.17   99.57 1401.42  102.37 1424.85  101.52
 1487.34  102.81  1526.4  105.49 1604.51  115.05 1674.81  119.41 1698.24  118.94
 1729.49   120.2 1760.73  123.66 1784.17  122.12 1831.04  121.45 1919.63  123.53
#Mann= 3 , 0 , 0
       0     .12       0 1206.13    .045       0 1260.81     .06       0
Bank Sta=1206.13,1260.81
XS Rating Curve= 0 ,0
Exp/Cntr=0.5,0.3

Type RM Length L Ch R = 1 ,11951.65,202.25,183.66,164.53
XS GIS Cut Line= 6
1578914.33437532697196.8214099411578203.11962943696847.508596003
1577793.41858882696639.511847377 1577579.3235676696532.464336768
1577392.48532474696435.9312446421577116.06732592696317.939011902
#Sta/Elev= 30
       0  128.67    23.4   128.6  171.61  123.49  312.02  117.16  538.23  109.72
  650.07  104.33  673.45  104.19  727.99  101.99  774.74  101.09  839.33   96.83
  854.98   94.38   855.2   92.61     866   92.47  876.98   93.44  878.46   95.15
  886.28    96.8  901.93      99  933.24  100.88 1136.63  101.96 1259.67  104.08
 1361.41  107.65 1392.72  108.13 1439.68  111.32 1522.73  114.45  1609.4  115.97
 1688.19  116.47 1732.08  118.07    1755   118.1 1899.22   124.6 2002.07     127
#Mann= 3 , 0 , 0
       0     .12       0  839.33    .045       0  886.28     .06       0
#XS Ineff= 2 , 0
       0     807     129     916       0   128.5
Permanent Ineff=
       F       F
Bank Sta=839.33,886.28
XS Rating Curve= 0 ,0
Exp/Cntr=0.5,0.3

Type RM Length L Ch R = 3 ,11866.53,,,
BEGIN DESCRIPTION:
Chessie System
MDE  Bridge #CE032707FS-7
Bridge Deck taken from DEM
Bridge Opening from surveys
END DESCRIPTION:
Bridge Culvert--1,0,-1,-1, 0
Deck Dist Width WeirC Skew NumUp NumDn MinLoCord MaxHiCord MaxSubmerge Is_Ogee
60,25,2.6,0, 60, 60, , , 0.98, 0, ,,,
       0     7.8    31.2    54.6  109.21  132.61  156.01  195.01  210.61  249.61
  257.42  296.42  358.82  397.82  413.42  444.63  499.23  522.63  561.63  577.23
  592.84  673.55  712.51  728.09  743.67  767.05     840     840     883     883
  946.96  994.13 1009.86 1033.45 1049.17 1096.35 1112.08 1174.98 1198.57 1336.98
 1391.76 1407.41 1446.54 1490.09    1561 1631.91 1647.67 1671.31 1694.94 1733.13
 1763.69 1786.61 1835.25 1858.03  1903.6 1949.17 1964.37 1979.56 1994.75 2007.04
  137.02  136.55  136.87  136.15  136.27   135.6  135.82  135.34  134.74  134.73
  134.34  134.22  133.29  133.47  132.91   133.3  131.94  132.24  131.83  131.21
   131.6  130.29   130.2  129.68   130.3  129.53  129.32  129.32  128.76  128.76
  128.76  127.16  127.56  127.33  127.62  126.62  126.95  127.05  126.07  126.15
  125.63  126.01  125.38  125.85   124.8  124.93  124.61  124.78  124.25  124.33
  123.54  124.09  123.55  124.01   123.4  123.49  122.95   123.3  122.73  123.25
                                                                                
                                                                                
                                                          125.32  124.32
                                                                                
                                                                                
                                                                                
       0     7.8    31.2    54.6  109.21  132.61  156.01  195.01  210.61  249.61
  257.42  296.42  358.82  397.82  413.42  444.63  499.23  522.63  561.63  577.23
  592.84  673.55  712.51  728.09  743.67  767.05     815     815     858     858
  946.96  994.13 1009.86 1033.45 1049.17 1096.35 1112.08 1174.98 1198.57 1336.98
 1391.76 1407.41 1446.54 1490.09    1561 1631.91 1647.67 1671.31 1694.94 1733.13
 1763.69 1786.61 1835.25 1858.03  1903.6 1949.17 1964.37 1979.56 1994.75 2007.04
  137.02  136.55  136.87  136.15  136.27   135.6  135.82  135.34  134.74  134.73
  134.34  134.22  133.29  133.47  132.91   133.3  131.94  132.24  131.83  131.21
   131.6  130.29   130.2  129.68   130.3  129.53  129.32  129.32  128.76  128.76
  128.76  127.16  127.56  127.33  127.62  126.62  126.95  127.05  126.07  126.15
  125.63  126.01  125.38  125.85   124.8  124.93  124.61  124.78  124.25  124.33
  123.54  124.09  123.55  124.01   123.4  123.49  122.95   123.3  122.73  123.25
                                                                                
                                                                                
                                                          125.32  124.32
                                                                                
                                                                                
                                                                                
Pier Skew, UpSta & Num, DnSta & Num=  ,860, 2 ,835, 2 , 0 , 0 , 0 ,,
       7       5
      81   127.1
       7       5
      81   127.1
BR Coef=-1 , 1 , 0 ,, 0 ,,,0.8,0,2,0,
WSPro=,,,, 1 ,,,, 0 ,,,, 0 ,,,,-1 ,-1 ,-1 , 0 , 0 , 0 , 0 , 0
BC Design=,, 0 ,, 0 ,,,,,,
BC Use User HTab Curves=0
BC User HTab FreeFlow(D)= 0

Type RM Length L Ch R = 1 ,11767.99,205.41,200.17,200.01
XS GIS Cut Line= 5
1578990.11637375696939.7696874441578351.02269918696700.804226547
1578059.41980349 696588.649266631577652.61781257696407.848381802
1577181.73668174696138.773449898
#Sta/Elev= 30
       0  140.26   97.15  135.72  254.09  125.04   336.3  123.63  411.03  118.51
  425.98  119.22  689.81  110.54  749.81  106.81  779.81  102.51  809.81   95.43
  810.94    90.8  841.07    90.8  847.31   98.67  854.81  101.94  862.31  103.31
  877.31  102.89   914.8   98.69   937.3   97.62 1071.34   97.62  1155.6   96.57
 1201.56   97.83 1278.16    97.4 1331.79   99.89 1370.09  104.18 1423.71  107.31
 1601.15  107.42 1730.15  112.82 1802.71     114 1923.64  111.47 1982.25  112.79
#Mann= 3 , 0 , 0
       0     .12       0  779.81    .045       0  862.31     .12       0
#XS Ineff= 2 , 0
       0  794.81     110  869.81       0     110
Permanent Ineff=
       F       F
Bank Sta=779.81,862.31
XS Rating Curve= 0 ,0
Exp/Cntr=0.5,0.3

Type RM Length L Ch R = 2 ,11667.92,,,
BEGIN DESCRIPTION:
US Route 40
MDE Bridge #CE032707FS-6
Bridge Deck taken from DEM
Bridge Opening from surveys
END DESCRIPTION:
Bridge Culvert--1,0,-1,-1, 0
Deck Dist Width WeirC Skew NumUp NumDn MinLoCord MaxHiCord MaxSubmerge Is_Ogee
46,108,2.6,0, 60, 60, , , 0.98, 0, 1,1,,
       0   37.37  119.57  134.52  164.41  216.73  239.15  366.19  388.61  403.56
  425.98  440.93   448.4  470.82  485.77  538.08  582.92  627.76  650.18  696.84
  741.84  764.34  801.84  831.84  846.84  876.84  929.34 1006.57 1021.89 1037.21
 1060.19 1090.83 1113.81 1121.47 1182.75 1205.73 1228.71 1274.68 1282.34 1335.96
 1381.92 1412.56 1428.82 1436.88 1485.25  1517.5 1533.63 1598.12 1662.62 1670.68
 1694.87 1702.93 1710.99 1775.49 1807.74 1823.87 1896.43 1912.55 1936.74  1966.1
  133.91  132.53  129.98  129.32  128.57   126.6  126.06  121.46  121.15  120.36
  119.56  118.66  118.67  117.84  117.55  115.32  114.07  112.03  111.75  109.26
  109.02  107.78  106.26  106.08  105.65  105.46  103.84  102.47   102.5  102.14
  102.07  101.63  101.71  101.43  100.78  100.99   100.5  100.82  100.59  101.27
  101.33  101.84  101.79  102.15  102.32  102.91  102.88  104.23  104.76  105.12
  105.61   105.5  105.89  107.29  107.68   108.3  109.58  110.45  110.69  111.29
                                                                                
                                                                                
                                                                                
                                                                                
                                                                                
                                                                                
       0   37.37  119.57  134.52  164.41  216.73  239.15  366.19  388.61  403.56
  425.98  440.93   448.4  470.82  485.77  538.08  582.92  627.76  650.18  696.84
  741.84  764.34  801.84  831.84  846.84  876.84  929.34 1006.57 1021.89 1037.21
 1060.19 1090.83 1113.81 1121.47 1182.75 1205.73 1228.71 1236.37 1259.36 1274.68
 1282.34 1335.96 1381.92 1412.56 1428.82 1436.88 1485.25  1517.5 1533.63 1598.12
 1662.62 1670.68 1694.87 1702.93 1710.99 1775.49 1807.74 1823.87 1831.93 1836.96
  133.91  132.53  129.98  129.32  128.57   126.6  126.06  121.46  121.15  120.36
  119.56  118.66  118.67  117.84  117.55  115.32  114.07  112.03  111.75  109.26
  109.02  107.78  106.26  106.08  105.65  105.46  103.84  102.47   102.5  102.14
  102.07  101.63  101.71  101.43  100.78  100.99   100.5  100.69  100.58  100.82
  100.59  101.27  101.33  101.84  101.79  102.15  102.32  102.91  102.88  104.23
  104.76  105.12  105.61   105.5  105.89  107.29  107.68   108.3  108.33  104.02
                                                                                
                                                                                
                                                                                
                                                                                
                                                                                
                                                                                
BR Coef=-1 , 0 , 0 ,, 0 ,,,0.8,0,,0,
WSPro=,,,, 1 ,,,, 0 ,,,, 0 ,,,,-1 ,-1 ,-1 , 0 , 0 , 0 , 0 , 0
Multiple Barrel Culv=2,8,13,158,0.012,0.5,1,8,2,90.8,90.8, 2,Culvert #1  , 0 ,21
     820     810     834     824
Culvert Bottom n=0.012
BC Design=,, 0 ,, 0 ,,,,,,
BC Use User HTab Curves=0
BC User HTab FreeFlow(D)= 0

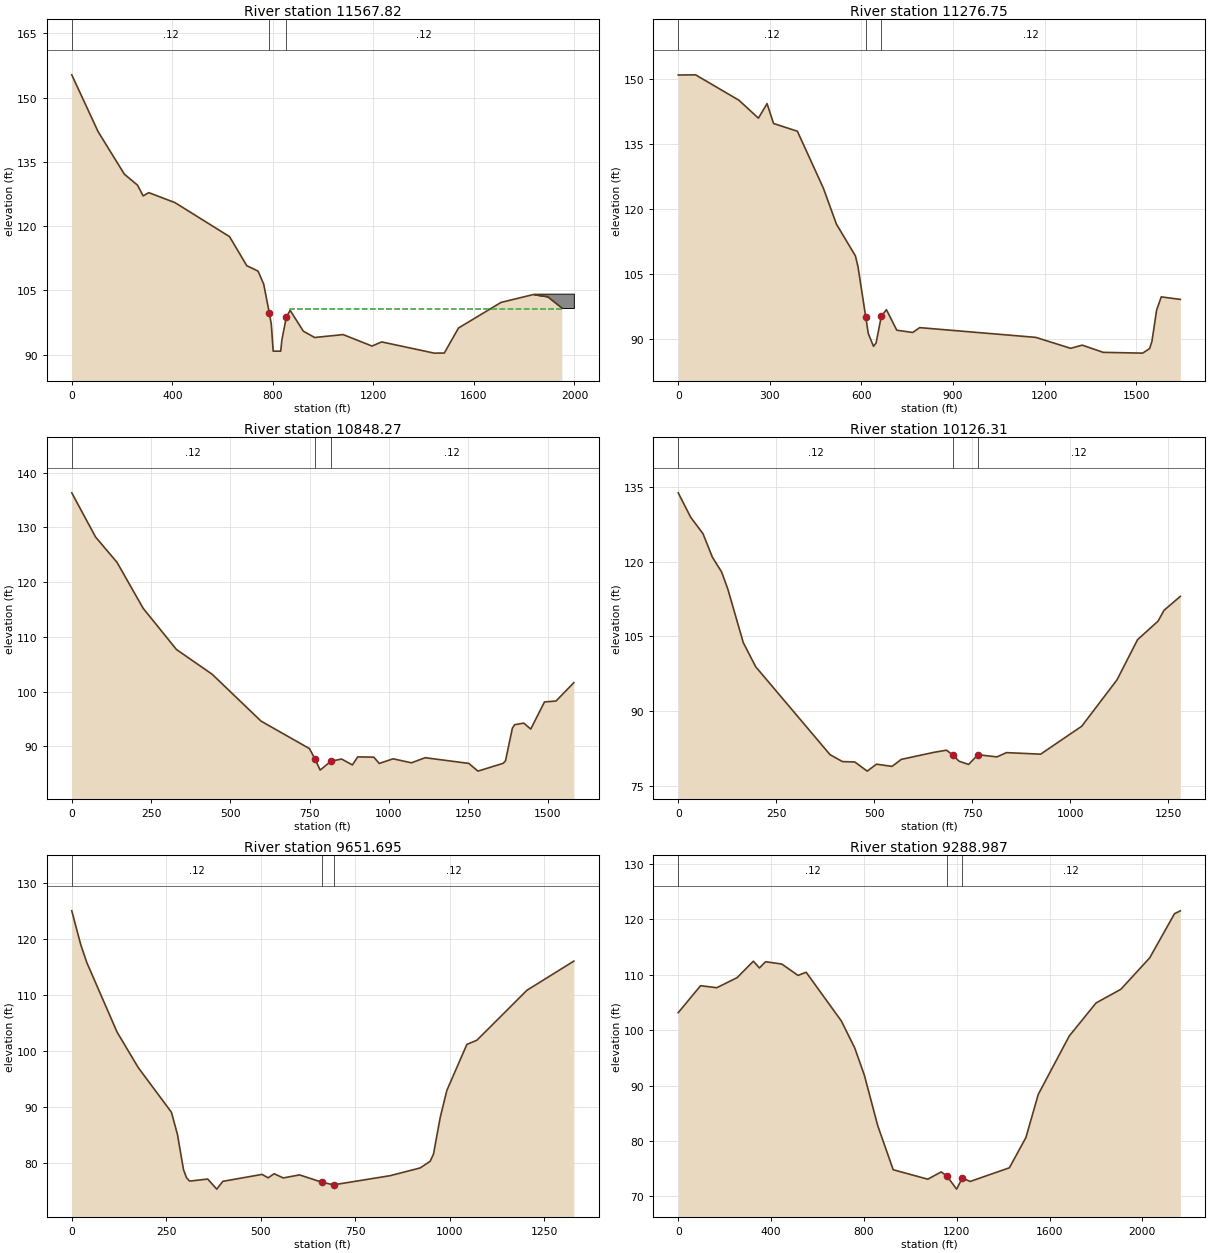
Type RM Length L Ch R = 1 ,11567.82,382.35,291.07,140
XS GIS Cut Line= 5
 1579060.1625118 696752.436992661578421.94522832696513.799225807
1578135.98143002696403.8131494971577743.07569063696229.188376427
1577280.96446943695965.124821484
#Sta/Elev= 30
       0   155.3  104.63  142.06  209.25  132.11  261.57  129.55  283.99  127.04
  306.41   127.8  411.03  125.46  627.76  117.53  696.37  110.75  741.37  109.48
  763.87   106.4  786.37   99.59  793.87   97.12  801.37    90.8  831.37    90.8
  835.95   93.42  853.87   98.79  868.87  100.33  921.37   95.46  966.37   93.99
 1079.68   94.67 1194.58   91.99 1232.89   92.96 1441.91   90.34 1482.22   90.36
 1538.66    96.2 1707.97  102.18 1836.96  104.02  1893.4  103.52 1949.96  100.87
#Mann= 3 , 0 , 0
       0     .12       0  786.37    .045       0  853.87     .12       0
#XS Ineff= 2 , 0
       0  786.37      96  869.01       0  100.61
Permanent Ineff=
       F       F
#Block Obstruct= 1 ,-1
  1839.9 1997.61  104.22
Bank Sta=786.37,853.87
XS Rating Curve= 0 ,0
Exp/Cntr=0.5,0.3

Type RM Length L Ch R = 1 ,11276.75,471.01,428.47,430.92
XS GIS Cut Line= 4
1578813.40693799696066.5574488941578265.96321496696157.798069388
1578108.65180036696264.7698313591577281.19375926695912.392262548
#Sta/Elev= 30
       0  150.96   56.77     151   198.7  145.15  262.57  141.01  290.96  144.36
  312.25  139.78  390.31  137.99  475.47  124.86  518.05  116.59  580.39  109.25
  588.86  106.76  614.25   95.14  622.72   91.31  639.65    88.4  648.11   89.17
  665.04   95.28  681.97   96.85  715.83   92.12  768.06   91.59  790.88   92.71
 1171.29   90.46 1285.42   87.94 1323.46   88.67 1391.93   87.01 1521.28   86.83
  1544.1   87.88 1551.71   89.56 1566.93   96.72 1582.14    99.8 1644.59   99.22
#Mann= 3 , 0 , 0
       0     .12       0  614.25    .045       0  665.04     .12       0
Bank Sta=614.25,665.04
XS Rating Curve= 0 ,0
Exp/Cntr=0.3,0.1

Type RM Length L Ch R = 1 ,10848.27,691.35,721.97,745.77
XS GIS Cut Line= 4
1578630.83910355695546.5782783931578113.51111072695746.337761104
1577776.32444909695975.6250321871577175.81531659695818.701047719
#Sta/Elev= 30
       0  136.31   75.04  128.24  142.57  123.62  225.11  115.22  330.16  107.69
  442.72  103.17  596.88   94.61  749.25    89.6  766.18   87.78  783.11   85.67
  816.97   87.28  850.83   87.69  884.69   86.61  901.62   88.08  952.41   88.03
  969.55   86.88 1012.96   87.73 1070.84      87 1114.25   87.93 1251.72   86.89
 1280.66   85.48 1360.25   86.91 1367.48   87.36 1389.19   93.33 1396.42   93.96
 1425.36   94.25 1447.07   93.16 1490.48   98.12 1526.65   98.28 1582.99  101.64
#Mann= 3 , 0 , 0
       0     .12       0  766.18    .045       0  816.97     .12       0
Bank Sta=766.18,816.97
XS Rating Curve= 0 ,0
Exp/Cntr=0.3,0.1

Type RM Length L Ch R = 1 ,10126.31,311.82,474.62,358.32
XS GIS Cut Line= 4
 1578158.7894017694946.7974807171577623.62856026695227.876527697
1577377.10083812695366.7653575391577009.20953944695507.703597069
#Sta/Elev= 30
       0  133.86   31.63  128.97   63.25  125.64   86.97  120.95  110.69  117.95
  126.51  114.53  166.04  103.74  197.67    98.9  387.43   81.22  419.06   79.83
  450.69   79.75  482.31   77.91  506.03   79.31  545.57   78.86  569.29   80.27
  652.69   81.69  684.83   82.12   700.9   81.13  716.97   79.89  741.07   79.26
  765.18   81.21  813.38   80.77  837.49   81.63  924.93   81.32 1029.87   86.94
 1119.82   96.26  1172.3  104.34 1224.77  108.08 1239.76  110.24 1281.41  113.04
#Mann= 3 , 0 , 0
       0     .12       0   700.9    .045       0  765.18     .12       0
Bank Sta=700.9,765.18
XS Rating Curve= 0 ,0
Exp/Cntr=0.3,0.1

Type RM Length L Ch R = 1 ,9651.695,335.57,362.71,273.92
XS GIS Cut Line= 4
1577929.17531168694708.6845067891577407.40914662 694995.89523983
1577275.77089401695000.682085395 1576799.4797617695366.875770003
#Sta/Elev= 30
       0  125.05   23.97  118.96   39.95  115.79  119.86   103.4  175.79   97.07
  263.68   89.08  279.67    85.1  295.65   78.81  303.64   77.39  311.63   76.79
  359.57   77.16  383.54   75.36  399.52   76.75   503.4   77.99  519.38   77.38
  535.36   78.11  559.33   77.36   602.6    77.9   662.2   76.58  692.61   76.13
   842.1   77.76  921.57   79.14  948.06   80.33  956.89   81.63  974.55   88.13
  992.21   92.99 1045.19   101.2 1071.68  101.95 1204.13  110.87 1328.11  116.07
#Mann= 3 , 0 , 0
       0     .12       0   662.2    .045       0  692.61     .12       0
Bank Sta=662.2,692.61
XS Rating Curve= 0 ,0
Exp/Cntr=0.3,0.1

Type RM Length L Ch R = 1 ,9288.987,772.77,940.37,742.4
XS GIS Cut Line= 4
1578262.51770245694012.5987745371577706.96205503694429.265264019
1577102.79528436694811.2097101211576509.04548761695276.487650946
#Sta/Elev= 30
       0  103.15   96.25  108.01  166.25  107.65  253.75  109.47  323.75  112.43
     350  111.21  376.25  112.34  446.25  111.92  516.25  109.87  551.25  110.44
  702.73  101.66   760.7   96.77   802.1   91.86  860.07   82.71  926.33   74.81
 1075.39    73.1 1133.36   74.42 1158.21   73.64 1199.62   71.31 1224.46   73.33
 1257.59   72.69    1427   75.16 1498.15   80.61 1551.51   88.41 1684.91   98.93
 1800.52   104.9 1907.24  107.36 2031.74  113.04 2138.46     121 2163.55  121.52
#Mann= 3 , 0 , 0
       0     .12       0 1158.21    .045       0 1224.46     .12       0
Bank Sta=1158.21,1224.46
XS Rating Curve= 0 ,0
Exp/Cntr=0.3,0.1

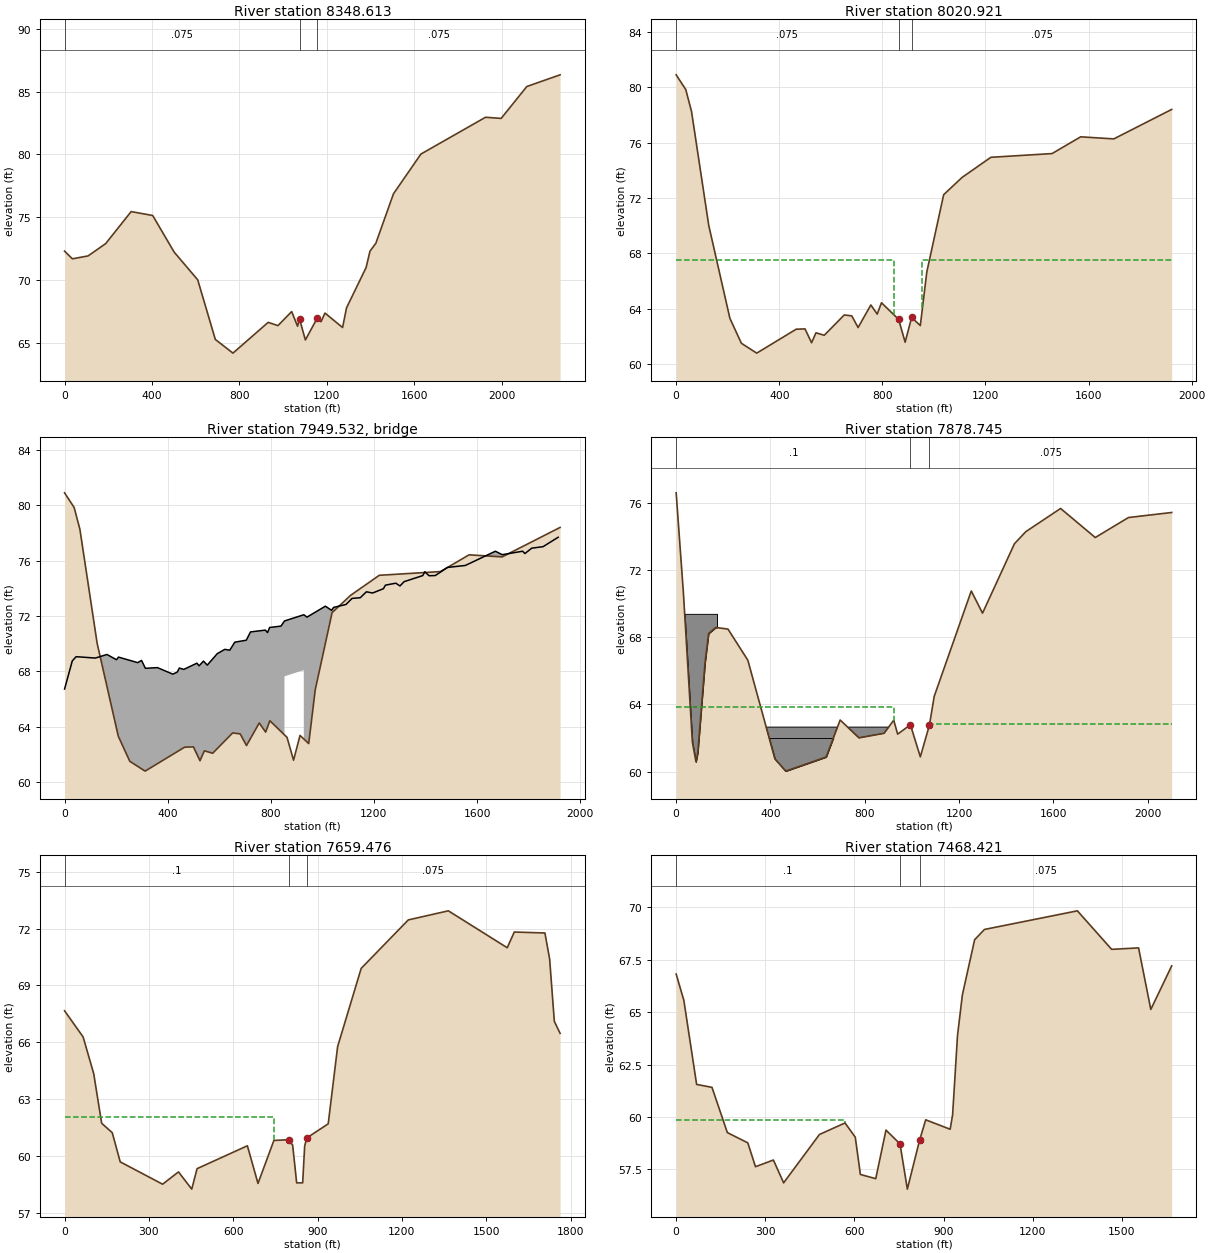
Type RM Length L Ch R = 1 ,8348.613,296.61,327.69,351.84
XS GIS Cut Line= 3
1577736.83408436693382.584301472 1576113.2119617694679.265420198
1575970.85102595694804.265498266
#Sta/Elev= 30
       0    72.3   35.83   71.69   107.5   71.92  188.13    72.9  304.59   75.45
  403.13   75.14  501.67   72.22  609.17   70.02   689.8   65.27  770.42   64.18
  931.68   66.63  976.47   66.37 1039.18   67.49 1066.05   66.32 1075.01    66.9
 1101.89   65.23 1155.64   66.95 1173.55   66.68 1191.47   67.37 1272.09   66.22
 1290.01   67.78 1379.59   70.99 1397.51    72.3 1424.39   72.93 1505.01   76.87
 1630.43   80.03 1926.06   82.96 1997.72   82.87 2115.13   85.41 2267.32   86.34
#Mann= 3 , 0 , 0
       0    .075       0 1075.01    .045       0 1155.64    .075       0
Bank Sta=1075.01,1155.64
XS Rating Curve= 0 ,0
Exp/Cntr=0.5,0.3

Type RM Length L Ch R = 1 ,8020.921,140.38,142.18,142.63
XS GIS Cut Line= 6
1577110.11344559693186.4794456961576995.17092177693504.586502999
1576871.93964417693683.0593878331576763.24229229693787.408845678
 1575932.0800916694293.5490311981575784.98087426694485.909546256
#Sta/Elev= 30
       0   80.91   37.21   79.85   59.54   78.27  126.53   70.02   208.4   63.32
  253.06   61.51   312.6    60.8  465.83   62.53  499.86   62.55  525.38   61.55
  542.39   62.27  574.53   62.09  652.16   63.56  681.27   63.49   705.8   62.65
  755.23   64.28  779.95   63.62  796.43   64.44  863.03   63.24  888.27   61.59
  913.51   63.38  947.16   62.79   972.4   66.67 1037.79   72.25 1109.42    73.5
 1220.84   74.95 1458.29   75.22 1569.24   76.43 1697.75   76.28 1922.28   78.41
#Mann= 3 , 0 , 0
       0    .075       0  863.03    .045       0  913.51    .075       0
#XS Ineff= 2 , 0
       0   846.2    67.5  955.57       0    67.5
Permanent Ineff=
       F       F
#Block Obstruct= 2 , 0
          676.21   63.18
Bank Sta=863.03,913.51
XS Rating Curve= 0 ,0
Exp/Cntr=0.5,0.3

Type RM Length L Ch R = 3 ,7949.532,,,
BEGIN DESCRIPTION:
Coudon Blvd
MDE Bridge #CE032707FS-5
Cecil County Bridge #CE-0113
Bridge Deck taken from DEM
Bridge Opening from surveys
END DESCRIPTION:
Bridge Culvert--1,0,-1,-1, 0
Deck Dist Width WeirC Skew NumUp NumDn MinLoCord MaxHiCord MaxSubmerge Is_Ogee
45,46,2.6,0, 60, 60, , , 0.98, 0, 0,0,,
       0   29.86   44.79  119.45  164.25  201.57  209.04   283.7  298.63  313.56
  360.24  419.79   436.8  445.31  462.32  513.36  521.87  538.88  553.58   592.4
  621.51  640.92  660.32  704.84  721.32  778.99  787.23  795.47  839.55     853
     853     928     928   940.5 1011.77 1035.64  1043.6 1091.35 1115.23 1147.06
 1170.94 1194.81 1236.75  1244.8 1285.01  1301.1 1317.19 1389.58 1397.62 1413.71
 1437.84 1485.43 1554.59 1671.18 1697.61 1776.92 1785.74 1812.17 1856.23 1914.77
   66.73   68.76   69.07   68.97   69.23   68.85   69.04   68.64    68.8   68.23
   68.28   67.81   67.95   68.25   68.15    68.6   68.41   68.75   68.46   69.29
    69.6   69.54   70.12   70.26   70.86   70.99   70.81   71.18   71.28   71.65
   71.65    72.1    72.1   71.93   72.72   72.42   72.63   72.84   73.28   73.33
   73.76   73.67   73.98   74.24   74.38   74.18   74.49   74.93   75.21   74.92
   74.93   75.52   75.66   76.69   76.44   76.69   76.52   76.91   77.02    77.7
                                                                                
                                                                                
                                                                                
   67.65    68.1
                                                                                
                                                                                
     190  219.86  234.79  309.45  354.25  391.57  399.04   473.7  488.63  503.56
  550.24  609.79   626.8  635.31  652.32  703.36  711.87  728.88  743.58   782.4
  811.51  830.92  850.32  894.84  911.32  968.99  977.23  985.47     998     998
    1073    1073 1080.03 1096.85 1105.26 1113.68  1130.5 1201.77 1225.64 1281.35
 1305.23 1337.06 1360.94 1384.81 1426.75  1434.8 1475.01  1491.1 1507.19 1579.58
 1587.62 1603.71 1627.84 1675.43 1744.59 1861.18 1887.61 1966.92 1975.74 2104.77
   66.73   68.76   69.07   68.97   69.23   68.85   69.04   68.64    68.8   68.23
   68.28   67.81   67.95   68.25   68.15    68.6   68.41   68.75   68.46   69.29
    69.6   69.54   70.12   70.26   70.86   70.99   70.81   71.18   71.17   71.17
    71.7    71.4   71.93   71.79    72.1   72.11   71.93   72.72   72.42   72.84
   73.28   73.33   73.76   73.67   73.98   74.24   74.38   74.18   74.49   74.93
   75.21   74.92   74.93   75.52   75.66   76.69   76.44   76.69   76.52    77.7
                                                                                
                                                                                
                                                                           67.14
    67.7
                                                                                
                                                                                
BR Coef=-1 , 0 , 0 ,, 0 ,,,0.8,0,,0,
WSPro=,,,, 1 ,,,, 0 ,,,, 0 ,,,,-1 ,-1 ,-1 , 0 , 0 , 0 , 0 , 0
BC Design=,, 0 ,, 0 ,,,,,,
BC Use User HTab Curves=0
BC User HTab FreeFlow(D)= 0

Type RM Length L Ch R = 1 ,7878.745,198.47,219.27,197.28
BEGIN DESCRIPTION:
Blocked Obstruction was put into the left overbank for this section due to the amout of conveyance.  It is felt that the upstream bridge is not overtopped by that much to justify the full conveyance in the overbank.
END DESCRIPTION:
XS GIS Cut Line= 6
1577088.34930138692943.7518652081576869.56212109693440.106556147
1576764.77555448693591.866411299 1576676.9057993693676.221376255
1575833.31624724694192.2301477491575673.77077758694400.866531193
#Sta/Elev= 30
       0   76.59   30.59   70.67   68.83   61.76   84.12   60.58   91.77   61.14
  122.36   66.46  137.65   68.22  168.24   68.58  219.84   68.48  304.01   66.63
  418.78   60.76  464.69   60.03  636.01   60.87  695.55   63.07  775.37   62.01
  881.62   62.28  922.81   63.06  939.29   62.23  993.45   62.79 1035.52   60.88
 1074.15   62.77 1094.41   64.48 1251.58   70.75 1299.33   69.43 1434.65   73.56
 1482.91   74.28 1630.41   75.66  1777.4   73.93 1918.13   75.12 2101.47   75.42
#Mann= 3 , 0 , 0
       0      .1       0  993.45    .045       0 1074.15    .075       0
#XS Ineff= 2 , 0
       0  925.76   63.86 1074.15       0   62.85
Permanent Ineff=
       F       F
#Block Obstruct= 3 ,-1
   14.93  173.24   69.39  330.95  919.05   62.65   346.6  679.79      62
Bank Sta=993.45,1074.15
XS Rating Curve= 0 ,0
Exp/Cntr=0.5,0.3

Type RM Length L Ch R = 1 ,7659.476,168.25,191.05,172.73
BEGIN DESCRIPTION:
Blocked Obstruction was put into the left overbank for this section due to the amout of conveyance.  It is felt that the upstream bridge is not overtopped by that much to justify the full conveyance in the overbank.
END DESCRIPTION:
XS GIS Cut Line= 4
 1577022.0382328693010.7851362081576502.35579076693586.954800203
1576400.67879121693605.7838741991575662.57909092694091.573983073
#Sta/Elev= 30
       0   67.66   65.99   66.28  103.69   64.34  131.97   61.72  169.68   61.22
  197.96   59.68  348.79    58.5  405.35   59.15  452.48   58.24  471.34   59.32
  650.44   60.53  688.15   58.54  744.71   60.81  797.27   60.85  811.51   60.56
  825.75   58.57   847.1   58.57  854.22   60.51  861.34   60.94  937.98   61.69
   971.5   65.77  1055.3    69.9  1222.9   72.46 1365.36   72.94 1574.87   70.99
 1600.01   71.82 1708.95   71.77 1725.71    70.4 1742.47    67.1 1762.94   66.47
#Mann= 3 , 0 , 0
       0      .1       0  797.27    .045       0  861.34    .075       0
#XS Ineff= 2 , 0
          745.97   62.03
Permanent Ineff=
       F       F
#Block Obstruct= 2 , 0
          745.97   60.75
Bank Sta=797.27,861.34
XS Rating Curve= 0 ,0
Exp/Cntr=0.3,0.1

Type RM Length L Ch R = 1 ,7468.421,356.4,399.48,375.63
BEGIN DESCRIPTION:
Blocked Obstruction was put into the left overbank for this section due to the amout of conveyance.  It is felt that the upstream bridge is not overtopped by that much to justify the full conveyance in the overbank.
END DESCRIPTION:
XS GIS Cut Line= 4
1576997.76874116692988.7527659541576405.56667435693413.376397431
1576311.21446297693472.3465295731575607.50421946693908.725507364
#Sta/Elev= 30
       0   66.82   25.84   65.57   68.91   61.55  120.59   61.41  172.27   59.25
  241.18   58.76  267.02   57.62  327.31   57.94  361.77   56.85  482.36   59.16
  568.49   59.71  602.94   59.03  620.17   57.25  671.85   57.05  706.31   59.37
  753.47   58.71  778.23   56.55  819.51   58.89  839.97   59.86  922.33   59.41
  930.57    60.1  947.04   63.88  963.52   65.83  1004.7   68.46 1037.65   68.95
 1350.64   69.84 1465.96      68 1556.56   68.07 1597.74   65.13    1668   67.21
#Mann= 3 , 0 , 0
       0      .1       0  753.47    .045       0  819.51    .075       0
#XS Ineff= 2 , 0
          568.03   59.83
Permanent Ineff=
       F       F
#Block Obstruct= 2 , 0
          711.63   58.96
Bank Sta=753.47,819.51
XS Rating Curve= 0 ,0
Exp/Cntr=0.3,0.1

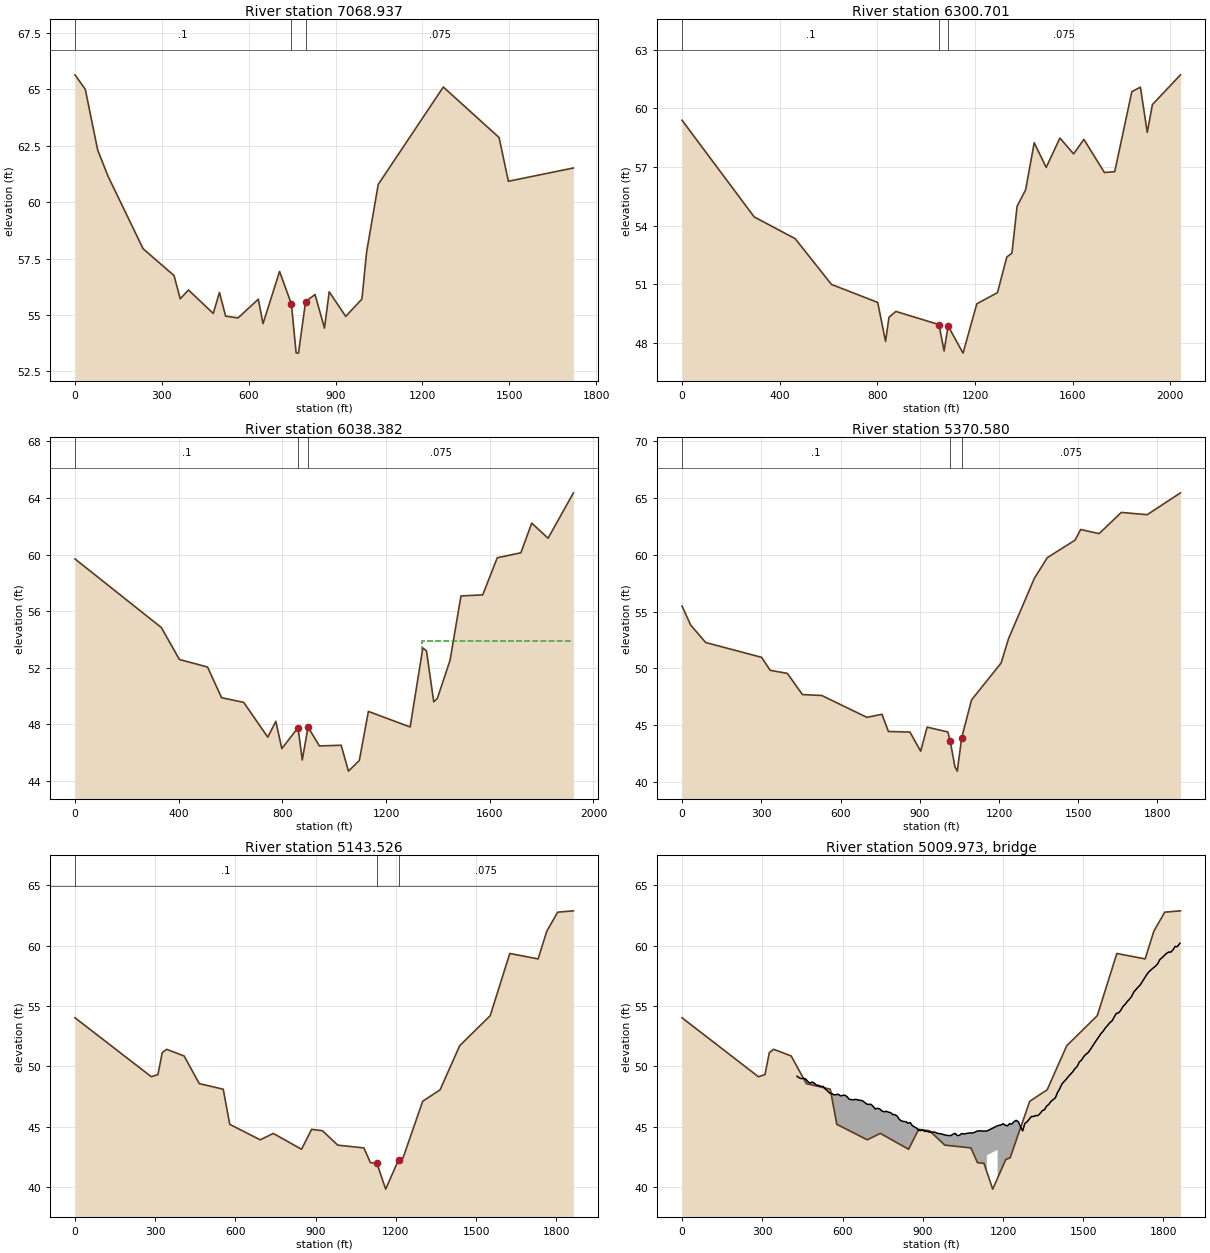
Type RM Length L Ch R = 1 ,7068.937,576.08,768.24,794.26
XS GIS Cut Line= 4
1576997.76874116692867.4204851991576432.07254447692976.909572944
1576117.36484055693165.7339984331575438.45650733 693547.04203026
#Sta/Elev= 30
       0   65.65   35.65   65.01   78.43   62.32  114.08   61.16  235.29   57.94
  342.24   56.75  363.63   55.72  392.15   56.11   477.7   55.07  499.09      56
  520.48   54.95  563.26   54.87  633.34    55.7  649.66   54.62  706.81   56.93
  747.62   55.49  763.95   53.32  772.11   53.31   796.6   55.59  829.26   55.91
  861.91   54.42  878.24   56.03  935.38   54.94  991.37   55.71 1007.43   57.79
 1047.57   60.79 1272.37   65.11 1465.06   62.87 1497.17   60.93 1721.87   61.52
#Mann= 3 , 0 , 0
       0      .1       0  747.62    .045       0   796.6    .075       0
Bank Sta=747.62,796.6
XS Rating Curve= 0 ,0
Exp/Cntr=0.3,0.1

Type RM Length L Ch R = 1 ,6300.701,131.18,262.32,258.27
XS GIS Cut Line= 5
1576814.42625715692811.8810496631576297.19781424692527.326810688
1576063.41481721692459.889609635 1575591.3530973692518.335358873
 1574860.5492124692568.137836814
#Sta/Elev= 30
       0   59.39  295.61   54.45  463.39   53.34  612.19      51  801.61   50.08
  833.65   48.09  847.76   49.32  875.97   49.62 1052.31   48.95 1073.47    47.6
 1089.92   48.88 1151.06   47.49 1207.48   50.01 1292.13   50.58 1330.37    52.4
 1351.42    52.6 1372.46   54.99 1407.55   55.84 1442.63   58.24 1491.74   56.98
 1547.87   58.48    1604   57.67  1646.1   58.41 1730.29   56.72 1772.39   56.76
 1842.55   60.85 1877.63   61.08  1905.7   58.77 1926.75   60.19 2041.82   61.71
#Mann= 3 , 0 , 0
       0      .1       0 1052.31    .045       0 1089.92    .075       0
Bank Sta=1052.31,1089.92
XS Rating Curve= 0 ,0
Exp/Cntr=0.3,0.1

Type RM Length L Ch R = 1 ,6038.382,243.47,667.8,400.79
XS GIS Cut Line= 4
1576759.38746716692666.4213903991575996.70709156692304.737913296
1575918.08024871692257.5618075731574931.31337099692269.355834007
#Sta/Elev= 30
       0    59.7  333.13   54.85  402.86   52.59  511.32   52.06  565.55   49.89
  650.77   49.56  743.73    47.1  774.72   48.22  797.97   46.29  860.42   47.78
  876.75   45.49  899.02   47.81  942.79   46.48  1026.8   46.53  1054.8    44.7
  1096.8   45.45  1131.8   48.92 1292.81   47.82 1341.82   53.41 1355.82    53.2
 1383.82    49.6 1397.82   49.84 1446.82   52.54 1488.83   57.08 1572.83   57.16
 1628.84   59.78 1719.84   60.13 1761.85   62.23 1824.85   61.16 1922.62   64.37
#Mann= 3 , 0 , 0
       0      .1       0  860.42    .045       0  899.02    .075       0
#XS Ineff= 2 , 0
                         1339.55           53.88
Permanent Ineff=
       F       F
Bank Sta=860.42,899.02
XS Rating Curve= 0 ,0
Exp/Cntr=0.3,0.1

Type RM Length L Ch R = 1 ,5370.580,91.82,227.05,366.5
XS GIS Cut Line= 4
1576422.11832531692404.0007806721575572.12214015691899.809672624
1575493.49529731691962.7111468911574695.43284242691954.848462641
#Sta/Elev= 30
       0   55.48   32.56   53.82   89.53   52.28  301.14   50.98  333.69   49.84
   398.8   49.57  455.77   47.71  529.02   47.63  699.94   45.71  756.91   45.98
  781.33   44.47  862.72   44.42  903.41   42.74  927.83   44.85 1006.21   44.43
 1015.18   43.64 1033.11   41.37 1042.07   40.99 1058.65   43.91 1095.98   47.24
 1207.98   50.48 1235.98   52.61 1333.99   57.92 1382.99   59.73    1488   61.27
    1509    62.2    1579   61.84    1663    63.7 1761.01    63.5 1887.08   65.42
#Mann= 3 , 0 , 0
       0      .1       0 1015.18    .045       0 1058.65    .075       0
Bank Sta=1015.18,1058.65
XS Rating Curve= 0 ,0
Exp/Cntr=0.4,0.3

Type RM Length L Ch R = 1 ,5143.526,132.3,223.46,124.68
XS GIS Cut Line= 4
1576440.21469526692346.4214217511576062.47926587692119.953934461
1575680.18343496691893.4082568441574838.62754375691393.283612967
#Sta/Elev= 30
       0   54.03  285.66   49.15  310.14   49.33  326.47   51.15  342.79   51.42
  408.08   50.87  464.83   48.58  554.34   48.12  578.75   45.21  692.66   43.93
  741.48   44.46  847.26   43.15   884.8    44.8  925.52   44.68  982.52   43.49
 1080.23   43.26 1104.66   42.04 1129.09   41.98 1161.66   39.85 1210.51    42.3
  1226.8   42.44 1300.09   47.12 1365.23   48.07 1438.51   51.72 1552.51    54.2
  1625.8   59.35 1731.66    58.9 1764.23    61.2 1804.94   62.77 1863.75   62.88
#Mann= 3 , 0 , 0
       0      .1       0 1129.09    .045       0 1210.51    .075       0
Bank Sta=1129.09,1210.51
XS Rating Curve= 0 ,0
Exp/Cntr=0.4,0.3

Type RM Length L Ch R = 3 ,5009.973,,,
BEGIN DESCRIPTION:
State Route 7
MDE Bridge #CE032707FS-2
Bridge Deck taken from DEM
Bridge Opening from surveys
END DESCRIPTION:
Bridge Culvert--1,0,-1,-1, 0
Deck Dist Width WeirC Skew NumUp NumDn MinLoCord MaxHiCord MaxSubmerge Is_Ogee
80,40,2.6,0, 174, 173, , , 0.98, 0, 0,0,,
     430  438.14  446.27  454.41  462.55  470.68  478.82  486.96  495.09  503.23
  511.37   519.5  527.64  535.78  543.91  552.05  560.19  568.33  576.46   584.6
  592.74  600.87  609.01  617.15  625.28  633.42  641.56  649.69  657.83  665.97
   674.1  682.24  690.38  698.51  706.65  714.79  722.92  731.06   739.2  747.33
  755.47  763.61  771.74  779.88  788.02  796.16  804.29  812.43  820.57   828.7
  836.84  844.98  853.11  861.25  869.39  877.52  882.76  890.91  899.05  907.19
  915.33  923.48  931.62  939.76  947.91  956.05  964.19  972.33  980.48  988.62
  996.76  1004.9 1013.05 1021.19 1029.33 1037.48 1045.62 1053.76  1061.9 1070.05
 1078.19 1086.33 1094.48 1102.62 1110.76  1118.9 1127.05    1140    1140    1180
    1180 1192.19 1200.33 1208.48 1216.62 1224.76  1232.9 1241.05 1249.19 1257.33
 1265.48 1273.62 1281.76  1289.9 1298.05 1306.19 1314.33 1322.48 1330.62 1338.76
  1346.9 1355.05 1363.19 1371.33 1379.47 1387.62 1395.76  1403.9 1412.05 1420.19
 1428.33 1436.47 1444.62 1452.76  1460.9 1469.05 1477.19 1485.33 1493.47 1501.62
 1509.76  1517.9 1526.05 1534.19 1542.33 1550.47 1558.62 1566.76  1574.9 1583.05
 1591.19 1599.33 1607.47 1615.62 1623.76  1631.9 1640.05 1648.19 1656.33 1664.47
 1672.62 1680.76  1688.9 1697.04 1705.19 1713.33 1721.47 1729.62 1737.76  1745.9
 1754.04 1762.19 1770.33 1778.47 1786.62 1794.76  1802.9 1811.04 1819.19 1827.33
 1835.47 1843.62 1851.76 1861.68
   49.19   49.06   48.99   49.02   48.96   48.74   48.63   48.71   48.61   48.45
   48.43   48.34   48.35   48.13   47.99    47.8   47.76   47.65   47.67    47.7
   47.56   47.61   47.62    47.5   47.28   47.26   47.24   47.28   47.23    47.2
   47.17   47.04   46.89   46.86   46.87   46.69   46.48   46.54   46.49   46.32
   46.25   46.29   46.22   46.18   46.02   46.01    45.9   45.62   45.49   45.45
   45.43   45.31   45.36    45.1   44.99    44.9   44.75   44.69   44.75   44.63
   44.64   44.58   44.56   44.58   44.54   44.46   44.44   44.41   44.34   44.31
   44.28   44.28    44.4   44.46   44.28   44.31   44.45   44.41   44.45   44.48
   44.51   44.49   44.56   44.65   44.67   44.67   44.65   44.66   44.66    45.1
    45.1   45.16   45.26   45.14   45.09   45.26   45.23   45.43   45.54   45.43
   45.03   44.67   45.28   45.42   45.63   45.86   45.86   45.94   45.93   46.11
   46.34   46.42   46.72   46.86   47.11   47.26    47.4   47.85   48.15   48.54
   48.75   48.94   49.17   49.37   49.56   49.82   49.99   50.37   50.52    50.8
   51.01   51.13   51.38   51.66   51.95   52.21   52.46   52.73   52.93    53.2
   53.39   53.62   53.76   54.07   54.39   54.43   54.63   54.95   55.13   55.37
   55.56   55.79   56.15   56.36   56.57   56.75   57.04   57.34   57.61   57.84
      58   58.16    58.3   58.49   58.85      59   59.18   59.35   59.47   59.46
   59.64   59.93   59.91    60.2
                                                                                
                                                                                
                                                                                
                                                                                
                                                                                
                                                                                
                                                                                
                                                                                
                                                                   42.66    43.1
                                                                                
                                                                                
                                                                                
                                                                                
                                                                                
                                                                                
                                                                                
                                                                                
                                
       0    8.14   16.27   24.41   32.55   40.68   48.82   56.96   65.09   73.23
   81.37    89.5   97.64  105.78  113.91  122.05  130.19  138.33  146.46   154.6
  162.74  170.87  179.01  187.15  195.28  203.42  211.56  219.69  227.83  235.97
   244.1  252.24  260.38  268.51  276.65  284.79  292.92  301.06   309.2  317.33
  325.47  333.61  341.74  349.88  358.02  366.16  374.29  382.43  390.57   398.7
  406.84  414.98  423.11  431.25  439.39  447.52  452.76  460.91  469.05  477.19
  485.33  493.48  501.62  509.76  517.91  526.05  534.19  542.33  550.48  558.62
  566.76   574.9  583.05  591.19  599.33  607.48  615.62  623.76   631.9  640.05
  648.19  656.33  664.48  672.62  680.76   688.9  697.05  705.19  713.33  721.48
  729.62  737.76   745.9  754.05  762.19  770.33  778.48  786.62  794.76   802.9
  811.05  819.19  827.33  835.48  843.62  851.76   859.9  868.05  876.19  884.33
  892.48     910     910     950     950  965.76   973.9  982.05  990.19  998.33
 1006.47 1014.62 1022.76  1030.9 1039.05 1047.19 1055.33 1063.47 1071.62 1079.76
  1087.9 1096.05 1104.19 1112.33 1120.47 1128.62 1136.76  1144.9 1153.05 1161.19
 1169.33 1177.47 1185.62 1193.76  1201.9 1210.05 1218.19 1226.33 1234.47 1242.62
 1250.76  1258.9 1267.04 1275.19 1283.33 1291.47 1299.62 1307.76  1315.9 1324.04
 1332.19 1340.33 1348.47 1356.62 1364.76  1372.9 1381.04 1389.19 1397.33 1405.47
 1413.62 1421.76 1431.68
   49.19   49.06   48.99   49.02   48.96   48.74   48.63   48.71   48.61   48.45
   48.43   48.34   48.35   48.13   47.99    47.8   47.76   47.65   47.67    47.7
   47.56   47.61   47.62    47.5   47.28   47.26   47.24   47.28   47.23    47.2
   47.17   47.04   46.89   46.86   46.87   46.69   46.48   46.54   46.49   46.32
   46.25   46.29   46.22   46.18   46.02   46.01    45.9   45.62   45.49   45.45
   45.43   45.31   45.36    45.1   44.99    44.9   44.75   44.69   44.75   44.63
   44.64   44.58   44.56   44.58   44.54   44.46   44.44   44.41   44.34   44.31
   44.28   44.28    44.4   44.46   44.28   44.31   44.45   44.41   44.45   44.48
   44.51   44.49   44.56   44.65   44.67   44.67   44.65   44.67   44.68    44.7
   44.75   44.78   44.89   45.08   45.16   45.26   45.14   45.09   45.26   45.23
   45.43   45.54   45.43   45.03   44.67   45.28   45.42   45.63   45.86   45.86
   45.94   45.94   45.94   47.26   47.26    47.4   47.85   48.15   48.54   48.75
   48.94   49.17   49.37   49.56   49.82   49.99   50.37   50.52    50.8   51.01
   51.13   51.38   51.66   51.95   52.21   52.46   52.73   52.93    53.2   53.39
   53.62   53.76   54.07   54.39   54.43   54.63   54.95   55.13   55.37   55.56
   55.79   56.15   56.36   56.57   56.75   57.04   57.34   57.61   57.84      58
   58.16    58.3   58.49   58.85      59   59.18   59.35   59.47   59.46   59.64
   59.93   59.91    60.2
                                                                                
                                                                                
                                                                                
                                                                                
                                                                                
                                                                                
                                                                                
                                                                                
                                                                                
                                                                                
                                                                                
                   43.94   45.26
                                                                                
                                                                                
                                                                                
                                                                                
                                                                                
                        
BR Coef=-1 , 0 , 0 ,, 0 ,,,0.8,0,,0,
WSPro=,,,, 1 ,,,, 0 ,,,, 0 ,,,,-1 ,-1 ,-1 , 0 , 0 , 0 , 0 , 0
BC Design=,, 0 ,, 0 ,,,,,,
BC Use User HTab Curves=0
BC User HTab FreeFlow(D)= 0

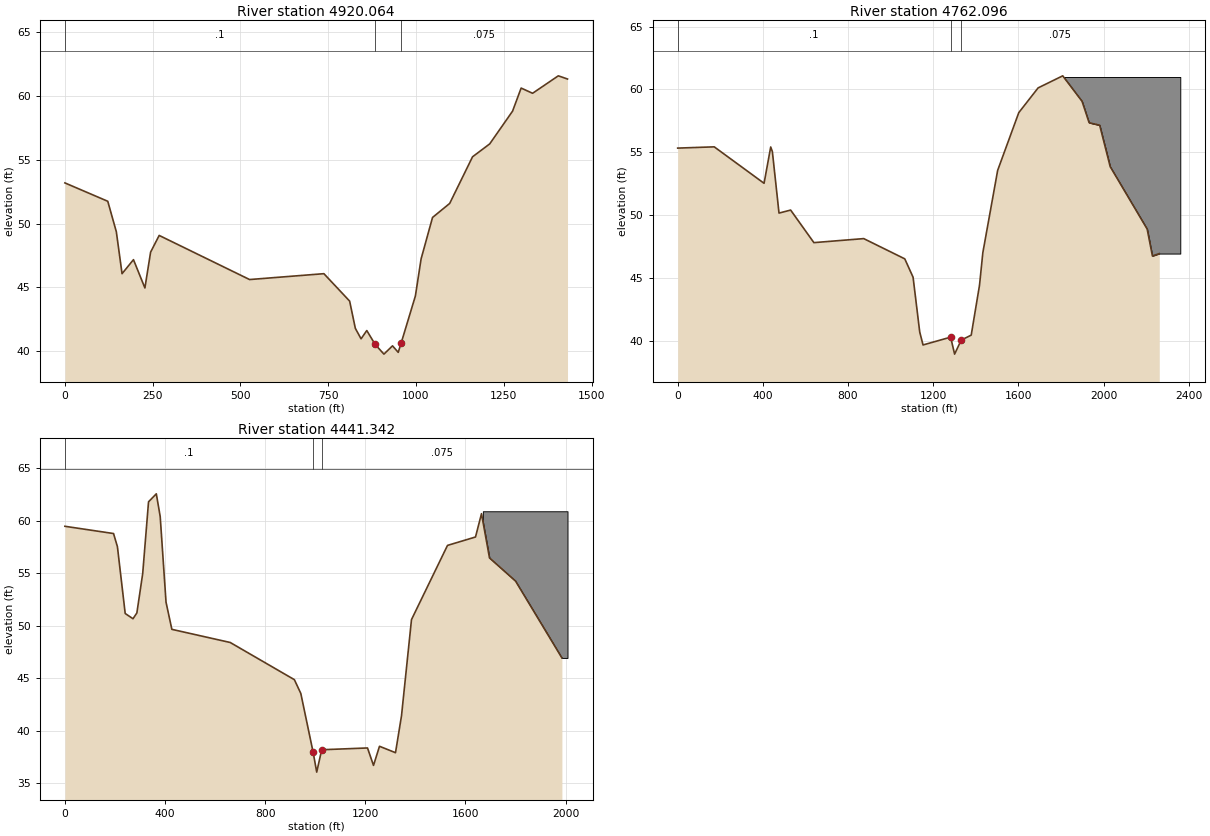
Type RM Length L Ch R = 1 ,4920.064,198.68,157.97,122.1
XS GIS Cut Line= 3
1576120.69830401692038.2144398241575731.21753483691807.411021009
1574889.71546428691307.318361983
#Sta/Elev= 30
       0   53.19  122.05   51.75  146.46   49.36  162.74   46.07  195.28   47.17
  227.83   44.95   244.1   47.76  268.51   49.07  526.02   45.61  737.73   46.07
  811.02   43.92   827.3   41.78  843.59   40.96  859.87   41.61  883.74   40.52
  908.73   39.76  933.16   40.41  949.44    39.9  957.59   40.61   998.3   44.32
 1014.59   47.23 1047.16   50.48 1096.01   51.58 1161.16   55.24 1210.01   56.25
 1275.16   58.82 1299.58   60.63 1332.16   60.22 1405.44   61.59 1431.62   61.34
#Mann= 3 , 0 , 0
       0      .1       0  883.74    .045       0  957.59    .075       0
Bank Sta=883.74,957.59
XS Rating Curve= 0 ,0
Exp/Cntr=0.4,0.3

Type RM Length L Ch R = 1 ,4762.096,241.29,320.75,191.6
XS GIS Cut Line= 4
1576468.03900793691992.3236156261575518.03407323691525.371977776
1575141.77066314691340.4289220271574477.37439826690924.454839855
#Sta/Elev= 30
       0   55.33   171.6   55.43  405.59   52.53  436.79   55.42  444.59   55.05
  475.79   50.16  530.39    50.4  639.59   47.81  873.59   48.13 1066.36   46.52
 1105.36   45.06 1136.56    40.7 1152.16   39.67  1281.7   40.29 1300.36   38.94
 1331.56   40.06 1378.36   40.45 1417.36   44.42 1432.96   47.01  1502.6   53.56
  1601.7   58.15 1692.55   60.12 1808.17   61.08 1899.02   59.05 1932.06   57.35
 1981.61   57.15 2031.16   53.85  2204.6   48.89 2229.37   46.75 2261.69   46.94
#Mann= 3 , 0 , 0
       0      .1       0  1281.7    .045       0 1331.56    .075       0
#Block Obstruct= 1 ,-1
 1807.59 2360.19   60.99
Bank Sta=1281.7,1331.56
XS Rating Curve= 0 ,0
Exp/Cntr=0.3,0.1

Type RM Length L Ch R = 1 ,4441.342,275.62,362.85,232.82
XS GIS Cut Line= 4
1576421.29204296691715.0365919471575572.12214015691306.177009121
1575418.79979663691286.5202984061574640.39405243690858.004004911
#Sta/Elev= 30
       0   59.48  194.23   58.79  209.77   57.54  240.84   51.18  271.92   50.68
  287.46   51.23  310.77   54.98  334.07   61.81  365.15   62.57  380.69   60.41
  403.99   52.25   427.3   49.67  660.38   48.42  916.76   44.88  942.47   43.57
  991.87   37.95 1005.99   36.08 1025.96   38.21 1208.92   38.38 1232.89   36.72
 1256.86   38.54 1320.79   37.93 1344.76   41.44 1384.71    50.6 1528.54   57.66
 1640.41   58.46 1664.38   60.68 1696.34   56.47 1800.22   54.27 1985.61   46.95
#Mann= 3 , 0 , 0
       0      .1       0  991.87    .045       0 1025.96    .075       0
#Block Obstruct= 1 ,-1
 1669.77 2007.99   60.91
Bank Sta=991.87,1025.96
XS Rating Curve= 0 ,0
Exp/Cntr=0.5,0.3