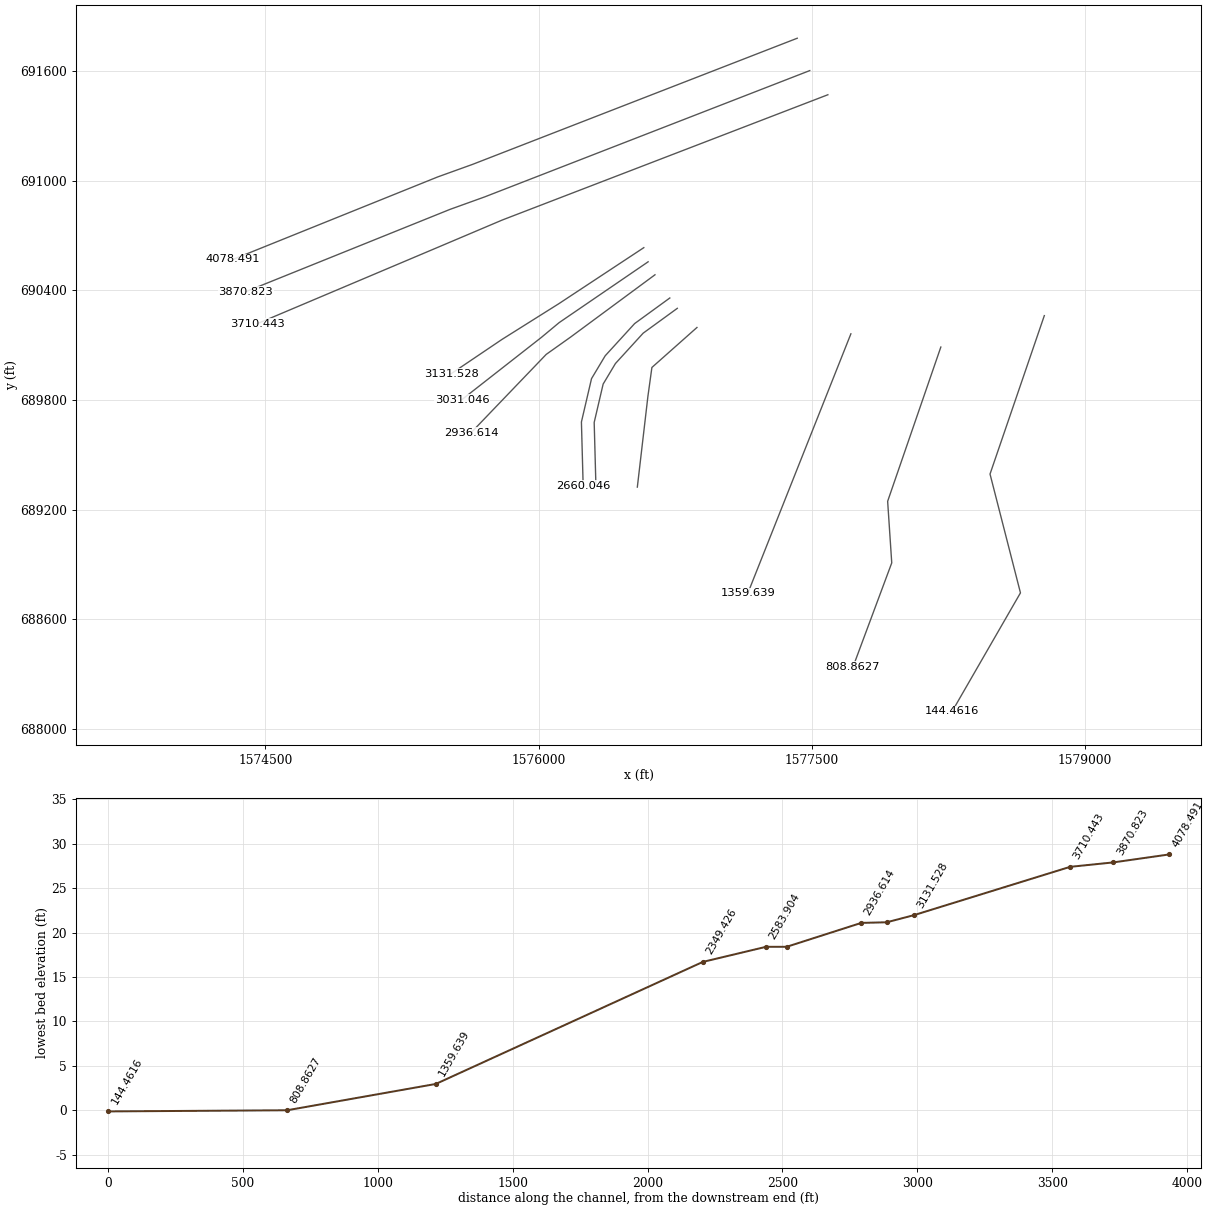
HEC-RAS study MillCreek.prj: MillCreek

--- MillCreek.g01 (geometry) --- (continued)

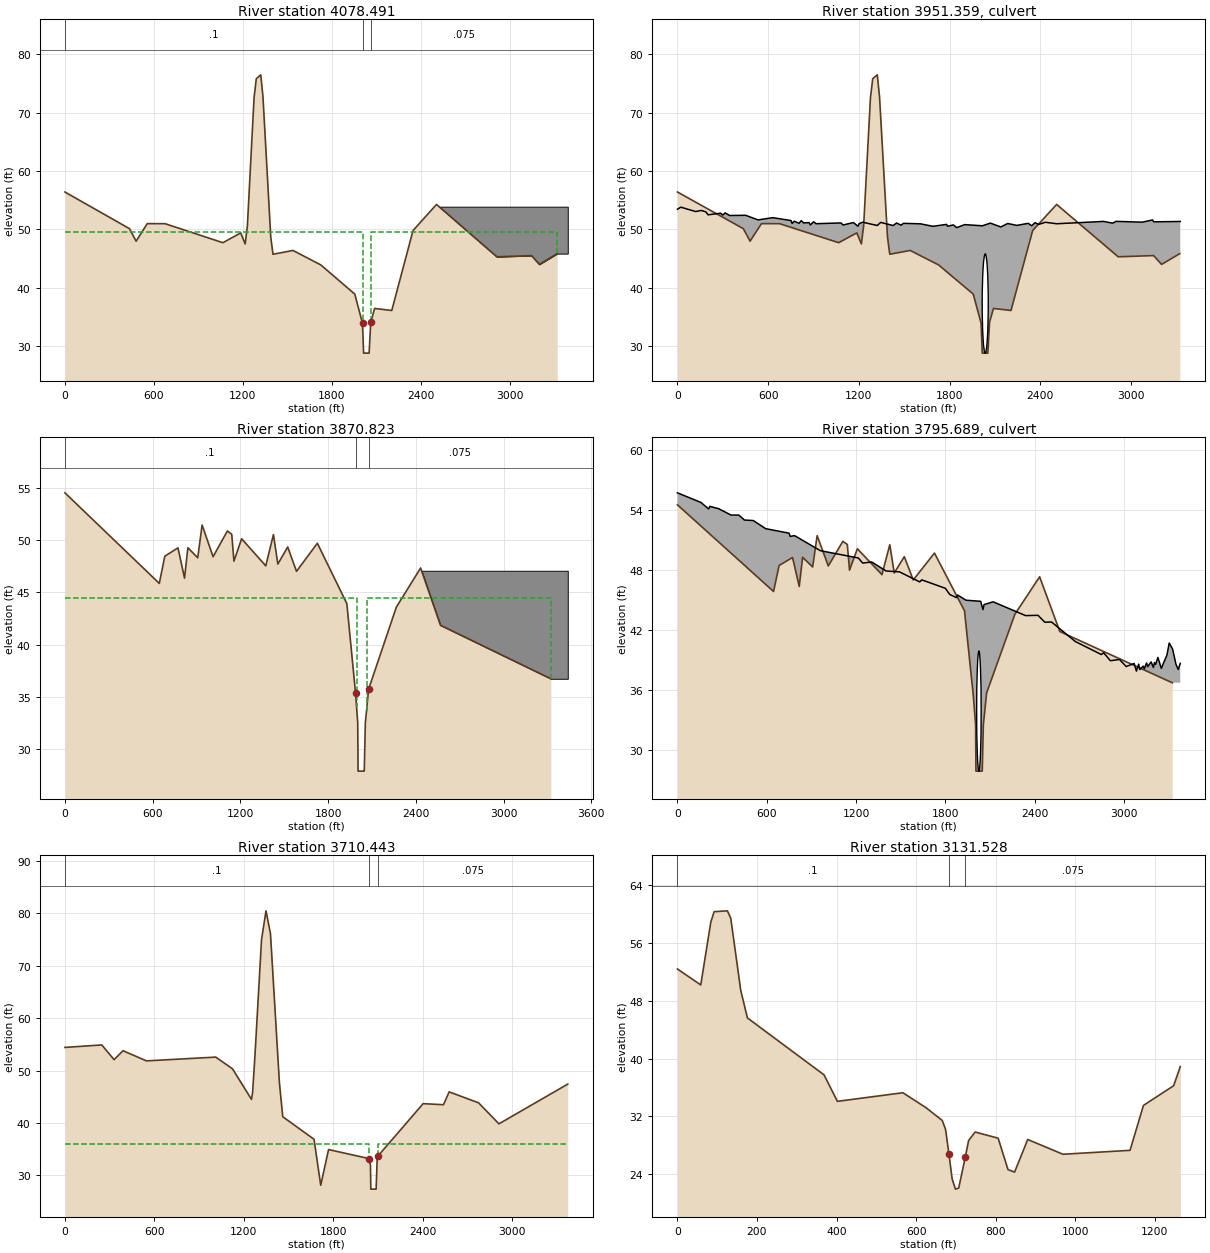
Type RM Length L Ch R = 1 ,4078.491,197.42,207.67,190
XS GIS Cut Line= 4
 1577419.3931109691779.7136055681575637.28323407691089.390823603
1575445.56150554691020.5676390081574321.68784773690569.055077806
#Sta/Elev= 30
       0   56.42   435.4   50.14  480.44   47.99  555.51      51  675.61   50.99
 1065.97   47.73 1186.08   49.41 1216.11   47.52 1231.12   50.62 1276.16   72.58
 1291.18   75.84  1321.2   76.51 1336.22   72.76 1388.76   48.71 1403.78   45.75
  1538.9    46.4 1726.57   43.92 1955.77   38.92 2007.83   33.91 2015.27    28.8
 2052.45    28.8 2063.46   34.08 2089.64   36.46 2205.37   36.11  2348.7   49.81
 2507.12   54.29 2914.48   45.31 3148.33   45.52 3201.14   44.01 3321.84   45.86
#Mann= 3 , 0 , 0
       0      .1       0 2007.83    .045       0 2063.46    .075       0
#XS Ineff= 2 , 0
       0 2007.83    49.5 2063.46       0    49.5
Permanent Ineff=
       F       F
#Block Obstruct= 1 ,-1
 2511.98 3392.81   53.91
Bank Sta=2007.83,2063.46
XS Rating Curve= 0 ,0
Exp/Cntr=0.5,0.3

Type RM Length L Ch R = 2 ,3951.359,,,
BEGIN DESCRIPTION:
Amtrak & gravel road
MDE Bridge #CE032707FS-3
Bridge Deck taken from DEM
Bridge Opening from surveys
END DESCRIPTION:
Bridge Culvert--1,0,-1,-1, 0
Deck Dist Width WeirC Skew NumUp NumDn MinLoCord MaxHiCord MaxSubmerge Is_Ogee
85,60,2.6,0, 60, 60, , , 0.98, 0, 0.5,0.5,,
       0   22.52  120.11  157.64  187.67  202.68  285.26  300.27  315.29  345.31
  450.41  532.98  630.57  750.68  758.19   773.2  803.23  818.24  833.26  870.79
   878.3  900.82  915.83 1080.98    1096 1163.56 1193.59 1201.09 1223.61  1321.2
 1343.72  1426.3 1448.82 1478.85 1493.86 1606.46 1689.04 1779.12 1786.63 1824.16
 1846.68 1899.23 2016.64  2068.7 2138.16 2183.42 2243.77 2319.21 2341.84 2364.47
  2387.1 2432.36  2507.8 2817.09 2877.44 2900.07 3073.58 3141.47 3149.02 3324.64
   53.47   53.82   53.07   53.26   53.02   52.51   52.79   52.48   52.84   52.39
   52.43   51.64   52.02   51.53   51.05   51.42   51.05   51.51   51.13   51.17
   50.77   51.31   50.99   51.12   50.77   51.19   50.55   50.99   51.25   50.68
   51.21   50.68   51.11   50.73   51.05   50.97   50.54   50.87   50.55   50.78
   50.32   50.83   50.63   51.09   50.43   51.02    50.7   51.05   50.64   51.16
   50.86   51.23   50.98   51.38   51.08   51.39   51.25   51.63   51.31   51.37
                                                                                
                                                                                
                                                                                
                                                                                
                                                                                
                                                                                
       0   22.52  120.11  157.64  187.67  202.68  285.26  300.27  315.29  345.31
  450.41  532.98  630.57  750.68  758.19   773.2  803.23  818.24  833.26  870.79
   878.3  900.82  915.83 1080.98    1096 1163.56 1193.59 1201.09 1223.61  1321.2
 1343.72  1426.3 1448.82 1478.85 1493.86 1606.46 1689.04 1779.12 1786.63 1824.16
 1846.68 1899.23 2016.64  2068.7 2138.16 2183.42 2243.77 2319.21 2341.84 2364.47
  2387.1 2432.36  2507.8 2817.09 2877.44 2900.07 3073.58 3141.47 3149.02 3324.64
   53.47   53.82   53.07   53.26   53.02   52.51   52.79   52.48   52.84   52.39
   52.43   51.64   52.02   51.53   51.05   51.42   51.05   51.51   51.13   51.17
   50.77   51.31   50.99   51.12   50.77   51.19   50.55   50.99   51.25   50.68
   51.21   50.68   51.11   50.73   51.05   50.97   50.54   50.87   50.55   50.78
   50.32   50.83   50.63   51.09   50.43   51.02    50.7   51.05   50.64   51.16
   50.86   51.23   50.98   51.38   51.08   51.39   51.25   51.63   51.31   51.37
                                                                                
                                                                                
                                                                                
                                                                                
                                                                                
                                                                                
BR Coef=-1 , 0 , 0 ,, 0 ,,,0.8,-1,,0,
WSPro=,,,, 1 ,,,, 0 ,,,, 0 ,,,,-1 ,-1 ,-1 , 0 , 0 , 0 , 0 , 0
Culvert=9,17,40,60,0.012,0.4,1,60,2,28.8,2035,28.6,2025,Culvert #1  , 0 ,85
Culvert Bottom n=0.012
BC Design=,, 0 ,, 0 ,,,,,,
BC Use User HTab Curves=0
BC User HTab FreeFlow(D)= 0

Type RM Length L Ch R = 1 ,3870.823,155.87,160.38,168.18
XS GIS Cut Line= 4
1577488.02295372691602.5415291041575703.70561671690911.363659546
1575513.09703885 690842.94006753 1574392.5174747690392.750897661
#Sta/Elev= 30
       0   54.51  645.59   45.85  683.12   48.45   773.2   49.25  818.24   46.35
  840.77   49.26  908.33    48.3  938.35   51.43 1013.42    48.4 1111.01   50.86
 1141.04   50.55 1156.05   47.98  1208.6   50.12 1373.75   47.53  1426.3   50.52
 1456.33    47.7 1523.89   49.33 1583.94      47 1726.57   49.69 1928.39   43.91
 1987.88   35.36 2002.76   32.55 2005.15    27.9 2047.38    27.9 2054.82   32.51
 2077.13   35.73  2266.9   43.58 2432.86   47.32 2568.65   41.85 3323.65   36.73
#Mann= 3 , 0 , 0
       0      .1       0 1987.88    .045       0 2077.13    .075       0
#XS Ineff= 2 , 0
       0    1995    44.5    2063       0    44.5
Permanent Ineff=
       F       F
#Block Obstruct= 1 ,-1
 2437.42 3439.41   47.06
Bank Sta=1987.88,2077.13
XS Rating Curve= 0 ,0
Exp/Cntr=0.5,0.3

Type RM Length L Ch R = 2 ,3795.689,,,
BEGIN DESCRIPTION:
Boundary Rd
MDE Bridge #CE032707FS-4
Bridge Deck taken from DEM
Bridge Opening from surveys
END DESCRIPTION:
Bridge Culvert--1,0,-1,-1, 0
Deck Dist Width WeirC Skew NumUp NumDn MinLoCord MaxHiCord MaxSubmerge Is_Ogee
50,25,2.6,0, 60, 60, , , 0.98, 0, 0.5,0.5,,
       0  157.44  209.92  217.42   277.4  359.87  412.35  449.84  509.81  592.28
  749.73  757.22  787.21  959.65 1214.56 1244.55 1304.52 1401.99 1491.96 1626.91
  1641.9 1799.35 1829.34 1874.32 1881.82 1938.13 2036.92 2052.11 2059.71 2120.51
 2338.54  2422.1 2467.69 2513.27  2672.8 2847.52 2862.71 2908.29 2969.07 3014.65
 3067.82 3083.02 3098.21 3105.81  3128.6 3136.19 3151.39 3158.98 3181.77 3196.97
 3204.56 3212.16 3227.35 3250.14 3288.13 3303.32 3326.11  3348.9 3364.09 3377.64
   55.71   54.75    54.1   54.36   54.12   53.49   53.49   52.99   52.94   52.13
   51.68   51.36   51.43   49.93    49.2   48.69    48.8    47.9   47.81   46.81
   47.01   46.17   45.55   45.24    45.5   44.98   44.87   44.04   44.54   44.82
   43.44   43.47   42.78    42.8   40.85   39.55   39.73   38.93   39.06   38.35
   38.66    37.9   38.59   38.05   38.39   38.14   38.71   38.34   38.82   38.26
   38.75   38.57   39.26   38.17    39.5    40.7    40.1   38.57   38.06   38.67
                                                                                
                                                                                
                                                                                
                                                                                
                                                                                
                                                                                
       0  157.44  209.92  217.42   277.4  359.87  412.35  449.84  509.81  592.28
  749.73  757.22  787.21  959.65 1214.56 1244.55 1304.52 1401.99 1491.96 1626.91
  1641.9 1799.35 1829.34 1874.32 1881.82 1938.13 2036.92 2052.11 2059.71 2120.51
 2338.54  2422.1 2467.69 2513.27  2672.8 2847.52 2862.71 2908.29 2969.07 3014.65
 3067.82 3083.02 3098.21 3105.81  3128.6 3136.19 3151.39 3158.98 3181.77 3196.97
 3204.56 3212.16 3227.35 3250.14 3288.13 3303.32 3326.11  3348.9 3364.09 3377.64
   55.71   54.75    54.1   54.36   54.12   53.49   53.49   52.99   52.94   52.13
   51.68   51.36   51.43   49.93    49.2   48.69    48.8    47.9   47.81   46.81
   47.01   46.17   45.55   45.24    45.5   44.98   44.87   44.04   44.54   44.82
   43.44   43.47   42.78    42.8   40.85   39.55   39.73   38.93   39.06   38.35
   38.66    37.9   38.59   38.05   38.39   38.14   38.71   38.34   38.82   38.26
   38.75   38.57   39.26   38.17    39.5    40.7    40.1   38.57   38.06   38.67
                                                                                
                                                                                
                                                                                
                                                                                
                                                                                
                                                                                
BR Coef=-1 , 0 , 0 ,, 0 ,,,0.8,0,,0,
WSPro=,,,, 1 ,,,, 0 ,,,, 0 ,,,,-1 ,-1 ,-1 , 0 , 0 , 0 , 0 , 0
Culvert=9,12,30,25,0.012,0.7,1,60,1,27.9,2025,27.4,2070,Culvert #1  , 0 ,50
Culvert Bottom n=0.012
BC Design=,, 0 ,, 0 ,,,,,,
BC Use User HTab Curves=0
BC User HTab FreeFlow(D)= 0

Type RM Length L Ch R = 1 ,3710.443,539.54,578.91,608.45
XS GIS Cut Line= 4
1577587.55488113691470.3930870291575800.59804133 690784.98498407
1575454.01990178690638.5435166811574454.50665188690217.180087805
#Sta/Elev= 30
       0   54.43  247.41    54.9  329.88   52.09  389.86    53.8   547.3   51.86
 1012.13   52.58 1124.59   50.35 1252.04   44.52 1259.54   45.86 1274.54   52.44
 1319.52   74.97 1349.51   80.48  1379.5   76.14 1439.48   47.71 1461.97   41.21
 1671.89   36.91 1716.88   28.14 1769.36   34.95 2041.93  33.216 2050.69   31.92
 2052.93    27.4 2088.68    27.4 2096.28   33.69 2103.88   33.81  2404.1    43.7
 2540.84    43.5 2578.82   45.95 2776.33   43.86 2913.07   39.85 3374.86   47.43
#Mann= 3 , 0 , 0
       0      .1       0 2041.93    .045       0 2103.88    .075       0
#XS Ineff= 2 , 0
       0    2040      36    2100       0      36
Permanent Ineff=
       F       F
Bank Sta=2041.93,2103.88
XS Rating Curve= 0 ,0
Exp/Cntr=0.5,0.3

Type RM Length L Ch R = 1 ,3131.528,85.77,100.48,121.59
XS GIS Cut Line= 4
 1576577.0667924690633.5377476511576110.39511608690326.668671161
1575798.16108261690131.0520756841575518.36585628689942.799941763
#Sta/Elev= 30
       0   52.38   58.64   50.18   83.78   58.82   92.16    60.3  125.67   60.42
  134.04    59.4  159.18   49.42  175.93   45.62  368.62   37.75  402.13   34.09
  566.79   35.28  624.61   33.23  665.91   31.44  674.17    30.2  682.43   26.88
  690.69   23.36  698.95   21.96  707.21   22.11  723.73    26.4  731.99   28.67
  748.51   29.85  806.34      29  831.12   24.66  847.64   24.31  880.68   28.82
  969.16   26.78  1137.9   27.32 1171.65   33.53 1247.58   36.25 1264.21   38.89
#Mann= 3 , 0 , 0
       0      .1       0  682.43    .045       0  723.73    .075       0
#XS Ineff= 2 , 0
       0                     808       0   28.25
Permanent Ineff=
       F       F
Bank Sta=682.43,723.73
XS Rating Curve= 0 ,0
Exp/Cntr=0.3,0.1

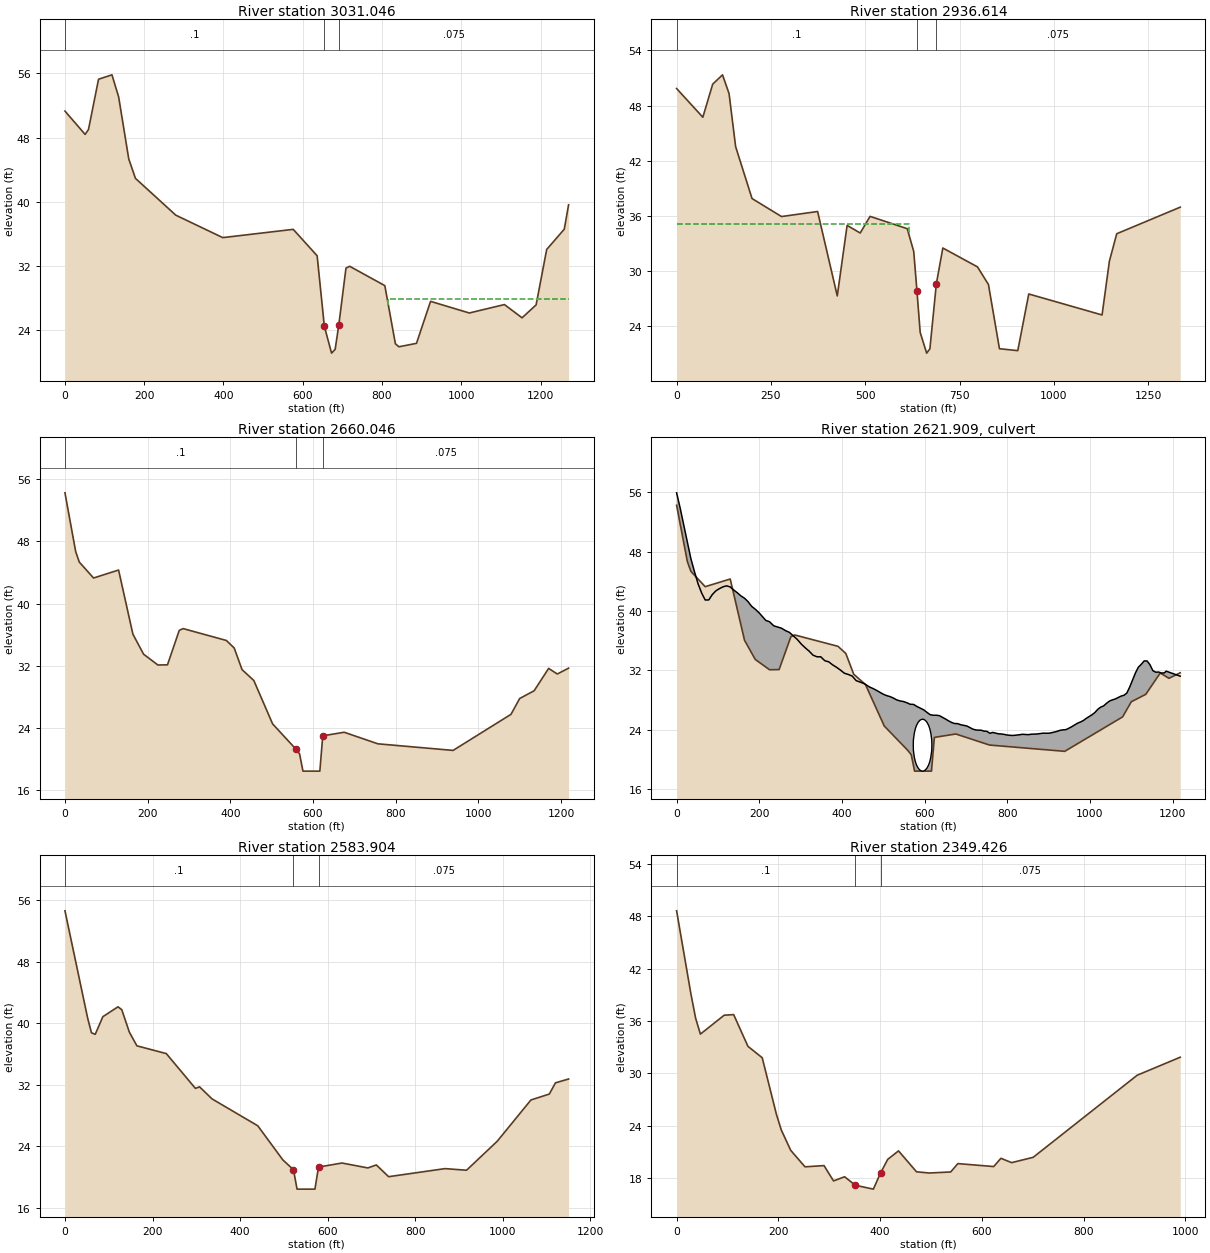
Type RM Length L Ch R = 1 ,3031.046,99.11,94.43,106.07
XS GIS Cut Line= 4
1576600.82567133690556.0959915221576112.56742515690223.410225749
1576014.43709137 690142.033851371575578.83414626 689802.16781728
#Sta/Elev= 30
       0   51.31   50.82   48.41   59.29   49.01    84.7   55.28  118.59   55.83
  135.53   53.06  160.94   45.35  177.88   42.93  279.53   38.35  398.11   35.55
  575.99   36.58   636.3   33.29  654.48   24.51  672.67   21.16  681.76   21.63
  690.86   24.63  709.05   31.75  718.31   31.98  807.09   29.57  833.73   22.33
  842.61   21.95     887   22.38  922.51   27.61 1020.18   26.16 1108.96   27.21
 1153.36   25.56 1188.87   27.17 1215.51   34.07  1259.9    36.6 1270.81   39.64
#Mann= 3 , 0 , 0
       0      .1       0  654.48    .045       0  690.86    .075       0
#XS Ineff= 2 , 0
       0                  815.97       0   27.85
Permanent Ineff=
       F       F
Bank Sta=654.48,690.86
XS Rating Curve= 0 ,0
Exp/Cntr=0.3,0.1

Type RM Length L Ch R = 1 ,2936.614,194.69,276.57,343.01
XS GIS Cut Line= 4
1576638.39398082690485.0613968521576173.59844789690142.920240685
1576041.26083083690049.3155847491575628.10924602689620.025266111
#Sta/Elev= 30
       0   49.86   69.54   46.74   95.61   50.33  121.69   51.35  139.07   49.31
  156.46   43.54  199.92    37.9  278.14   35.94  373.76   36.49  425.91   27.31
  451.98   34.98  486.75   34.15  512.83   35.96  611.44   34.62  628.59   32.14
  637.16   27.83  645.74   23.33  662.88   21.09  671.46   21.56  688.61   28.65
  705.75   32.52  797.53   30.47  826.68   28.55  855.82   21.57   904.4   21.36
  933.54   27.52 1127.85   25.24 1147.28   31.09 1166.71   34.07 1335.05   36.96
#Mann= 3 , 0 , 0
       0      .1       0  637.16    .045       0  688.61    .075       0
#XS Ineff= 2 , 0
       0  615.18   35.12  836.29       0    26.2
Permanent Ineff=
       F       F
Bank Sta=637.16,688.61
XS Rating Curve= 0 ,0
Exp/Cntr=0.5,0.3

Type RM Length L Ch R = 1 ,2660.046,72.19,76.14,70.43
XS GIS Cut Line= 6
1576719.87798256690358.0775528251576526.80014002690218.096116975
1576365.09212951690041.6873782281576290.06968252689916.649966627
1576234.59990959689679.4471061381576244.16925147689330.166126296
#Sta/Elev= 30
       0   54.27   25.94   46.69   34.58   45.35   69.17   43.29  129.69   44.32
  164.28   36.06  190.21   33.47   224.8   32.08  247.98    32.1  276.47   36.54
  285.96   36.77  390.42   35.24  409.41   34.27   428.4   31.48  456.89   30.08
  502.28   24.49  559.43   21.19  567.59   20.61  575.75    18.4  616.57    18.4
  623.61   22.95  675.46   23.41  756.95   21.92  938.95   21.07    1079   25.72
 1100.01   27.76 1135.02   28.76 1170.04   31.64 1191.04   30.92 1218.34   31.67
#Mann= 3 , 0 , 0
       0      .1       0  559.43    .045       0  623.61    .075       0
Bank Sta=559.43,623.61
XS Rating Curve= 0 ,0
Exp/Cntr=0.5,0.3

Type RM Length L Ch R = 2 ,2621.909,,,
BEGIN DESCRIPTION:
Perryville Comm Park Rd aka Firestone Rd
MDE Bridge #CE032707FS-1
Cecil County Bridge #CEP-01
Bridge Deck taken from DEM
Bridge Opening from surveys
END DESCRIPTION:
Bridge Culvert--1,0,-1,-1, 0
Deck Dist Width WeirC Skew NumUp NumDn MinLoCord MaxHiCord MaxSubmerge Is_Ogee
25,30,2.6,0, 152, 151, , , 0.98, 0, 0.5,0.5,,
       0    8.65   17.29   25.94   34.58   43.23   51.88   60.52   69.17   77.82
   86.46   95.11  103.75   112.4  121.05  129.69  138.34  146.98  155.63  164.28
  172.92  181.57  190.21  198.86  207.51  216.15   224.8  234.94  244.44  253.94
  263.43  272.93  282.42  291.92  301.42  310.91  320.41   329.9   339.4   348.9
  358.39  367.89  377.38  386.88  396.37  405.87  415.37  424.86  434.36  443.85
  453.35  467.18  475.34   483.5  491.67  499.83  507.99  516.16  524.32  532.48
  540.65  548.81  556.97  565.14   573.3  581.46  589.63  597.79  605.82  613.22
  620.63  628.04  635.45  642.85  650.26  657.67  665.08  672.48  679.89   687.3
  694.71  702.11  709.52  716.93  724.34  731.74  736.65  743.68  750.72  757.75
  764.78  771.81  778.84  785.87  792.91  799.94  806.97     814  821.03  828.06
  836.97  843.97  850.97  857.97  864.98  871.98  878.98  885.98  892.99  899.99
  906.99  913.99     921     928     935  942.01  949.01  956.01  963.01  970.02
  977.02  984.02  991.02  998.03 1005.03 1012.03 1019.03 1026.04 1033.04 1040.04
 1047.05 1054.05 1061.05 1068.05 1075.06 1082.06 1089.06 1096.06 1103.07 1110.07
 1117.07 1124.07 1131.08 1138.08 1145.08 1152.09 1159.09 1166.09 1173.09  1180.1
 1184.24 1218.34
   55.95   53.88   51.59   49.24   47.05   45.31   43.68   42.44   41.49    41.5
   42.23   42.73   43.03   43.27    43.4   43.25   42.83   42.46   42.04   41.73
   41.26   40.63   40.25    39.8   39.25   38.72   38.56   38.01   37.84   37.68
   37.36   37.12   36.65   36.17   35.55   35.05    34.6   34.05   33.83   33.82
    33.3   33.15   32.74   32.41   32.03   31.61   31.44   31.22   30.61   30.42
   30.22   29.74   29.54    29.3   29.04   28.78   28.59   28.46   28.26   28.01
   27.87   27.79   27.63   27.42    27.4   27.12    26.9   26.67   26.32   26.02
   25.94   25.94   25.89   25.67   25.44   25.19   24.97   24.82   24.81   24.66
   24.57   24.49   24.27   24.06   23.95   23.93   23.92    23.8   23.77   23.51
   23.62   23.53   23.43   23.41   23.35   23.27   23.23   23.21   23.25    23.3
   23.37   23.34   23.32   23.38   23.39   23.41   23.46   23.52   23.51   23.51
   23.58   23.67   23.78   23.91   23.97      24   24.19    24.4   24.64   24.87
   25.03   25.23   25.52   25.77   26.01   26.32   26.75   27.04    27.2   27.55
   27.85   28.01   28.13   28.32   28.52   28.63   28.93   29.74   30.71   31.66
   32.43   32.81   33.27   33.27   32.76   31.96   31.75   31.77   31.63   31.66
   31.89   31.21
                                                                                
                                                                                
                                                                                
                                                                                
                                                                                
                                                                                
                                                                                
                                                                                
                                                                                
                                                                                
                                                                                
                                                                                
                                                                                
                                                                                
                                                                                
                
       0    8.65   17.29   25.94   34.58   43.23   51.88   60.52   69.17   77.82
   86.46   95.11  103.75   112.4  121.05  129.69  138.34  146.98  155.63  164.28
  172.92  181.57  190.21  198.86  207.51  216.15   224.8  234.94  244.44  253.94
  263.43  272.93  282.42  291.92  301.42  310.91  320.41   329.9   339.4   348.9
  358.39  367.89  377.38  386.88  396.37  405.87  415.37  424.86  434.36  443.85
  453.35  467.18  475.34   483.5  491.67  499.83  507.99  516.16  524.32  532.48
  540.65  548.81  556.97  565.14   573.3  581.46  589.63  597.79  605.82  613.22
  620.63  628.04  635.45  642.85  650.26  657.67  665.08  672.48  679.89   687.3
  694.71  702.11  709.52  716.93  724.34  731.74  736.65  743.68  750.72  757.75
  764.78  771.81  778.84  785.87  792.91  799.94  806.97     814  821.03  828.06
  836.97  843.97  850.97  857.97  864.98  871.98  878.98  885.98  892.99  899.99
  906.99  913.99     921     928     935  942.01  949.01  956.01  963.01  970.02
  977.02  984.02  991.02  998.03 1005.03 1012.03 1019.03 1026.04 1033.04 1040.04
 1047.05 1054.05 1061.05 1068.05 1075.06 1082.06 1089.06 1096.06 1103.07 1110.07
 1117.07 1124.07 1131.08 1138.08 1145.08 1152.09 1159.09 1166.09 1173.09  1180.1
 1184.24
   55.95   53.88   51.59   49.24   47.05   45.31   43.68   42.44   41.49    41.5
   42.23   42.73   43.03   43.27    43.4   43.25   42.83   42.46   42.04   41.73
   41.26   40.63   40.25    39.8   39.25   38.72   38.56   38.01   37.84   37.68
   37.36   37.12   36.65   36.17   35.55   35.05    34.6   34.05   33.83   33.82
    33.3   33.15   32.74   32.41   32.03   31.61   31.44   31.22   30.61   30.42
   30.22   29.74   29.54    29.3   29.04   28.78   28.59   28.46   28.26   28.01
   27.87   27.79   27.63   27.42    27.4   27.12    26.9   26.67   26.32   26.02
   25.94   25.94   25.89   25.67   25.44   25.19   24.97   24.82   24.81   24.66
   24.57   24.49   24.27   24.06   23.95   23.93   23.92    23.8   23.77   23.51
   23.62   23.53   23.43   23.41   23.35   23.27   23.23   23.21   23.25    23.3
   23.37   23.34   23.32   23.38   23.39   23.41   23.46   23.52   23.51   23.51
   23.58   23.67   23.78   23.91   23.97      24   24.19    24.4   24.64   24.87
   25.03   25.23   25.52   25.77   26.01   26.32   26.75   27.04    27.2   27.55
   27.85   28.01   28.13   28.32   28.52   28.63   28.93   29.74   30.71   31.66
   32.43   32.81   33.27   33.27   32.76   31.96   31.75   31.77   31.63   31.66
   31.89
                                                                                
                                                                                
                                                                                
                                                                                
                                                                                
                                                                                
                                                                                
                                                                                
                                                                                
                                                                                
                                                                                
                                                                                
                                                                                
                                                                                
                                                                                
        
BR Coef=-1 , 0 , 0 ,, 0 ,,,0.8,0,,0,
WSPro=,,,, 1 ,,,, 0 ,,,, 0 ,,,,-1 ,-1 ,-1 , 0 , 0 , 0 , 0 , 0
Culvert=9,7,45,30,0.012,0.4,1,61,2,18.4,595,18.4,550,Culvert #1  , 0 ,25
Culvert Bottom n=0.012
BC Design=,, 0 ,, 0 ,,,,,,
BC Use User HTab Curves=0
BC User HTab FreeFlow(D)= 0

Type RM Length L Ch R = 1 ,2583.904,171.64,234.48,278.63
XS GIS Cut Line= 6
1576760.96571255690301.4048217831576573.61821546690165.577886358
1576421.47532076689999.6038194451576353.83826531689886.875393778
1576304.69106981689677.0784802141576314.14299491689332.083215177
#Sta/Elev= 30
       0   54.64   51.88   40.65   60.52   38.76   69.17   38.56   86.46   40.85
  121.05   42.14  129.69   41.77  146.98   38.85  164.28   37.06   231.4   36.05
  297.88   31.52  307.37   31.72  335.86   30.15  440.32   26.65  497.38   22.22
  521.87   20.92  530.03    18.4  570.85    18.4  579.01   21.27  632.47    21.8
  691.73   21.16  711.03   21.55  739.16   20.02  868.03   21.07  917.05   20.86
  987.08   24.63 1064.11   30.01 1106.12   30.78 1120.13   32.24 1150.14   32.74
#Mann= 3 , 0 , 0
       0      .1       0  521.87    .045       0  579.01    .075       0
Bank Sta=521.87,579.01
XS Rating Curve= 0 ,0
Exp/Cntr=0.5,0.3

Type RM Length L Ch R = 1 ,2349.426,930.23,989.79,901.36
XS GIS Cut Line= 4
1576868.81539968690196.5923184311576621.53892891689977.847748131
1576599.66101974689820.1455650331576541.56157811689323.072564527
#Sta/Elev= 30
       0   48.64   28.04   39.13   37.38   36.32   46.73   34.49   93.46   36.66
  112.15   36.73  140.19   33.09  168.23   31.78  196.26   25.27  205.61   23.51
   224.3   21.15  252.34   19.26  289.72    19.4  308.41   17.64  330.14   18.12
  351.34   17.14  386.68    16.7  400.81   18.55  414.95   20.12  436.15   21.09
  471.48   18.69   496.4   18.55  538.69   18.67  552.79   19.63  623.26   19.29
  637.36   20.24   658.5   19.74  700.79   20.35  905.17   29.77  989.81   31.84
#Mann= 3 , 0 , 0
       0      .1       0  351.34    .045       0  400.81    .075       0
Bank Sta=351.34,400.81
XS Rating Curve= 0 ,0
Exp/Cntr=0.3,0.1

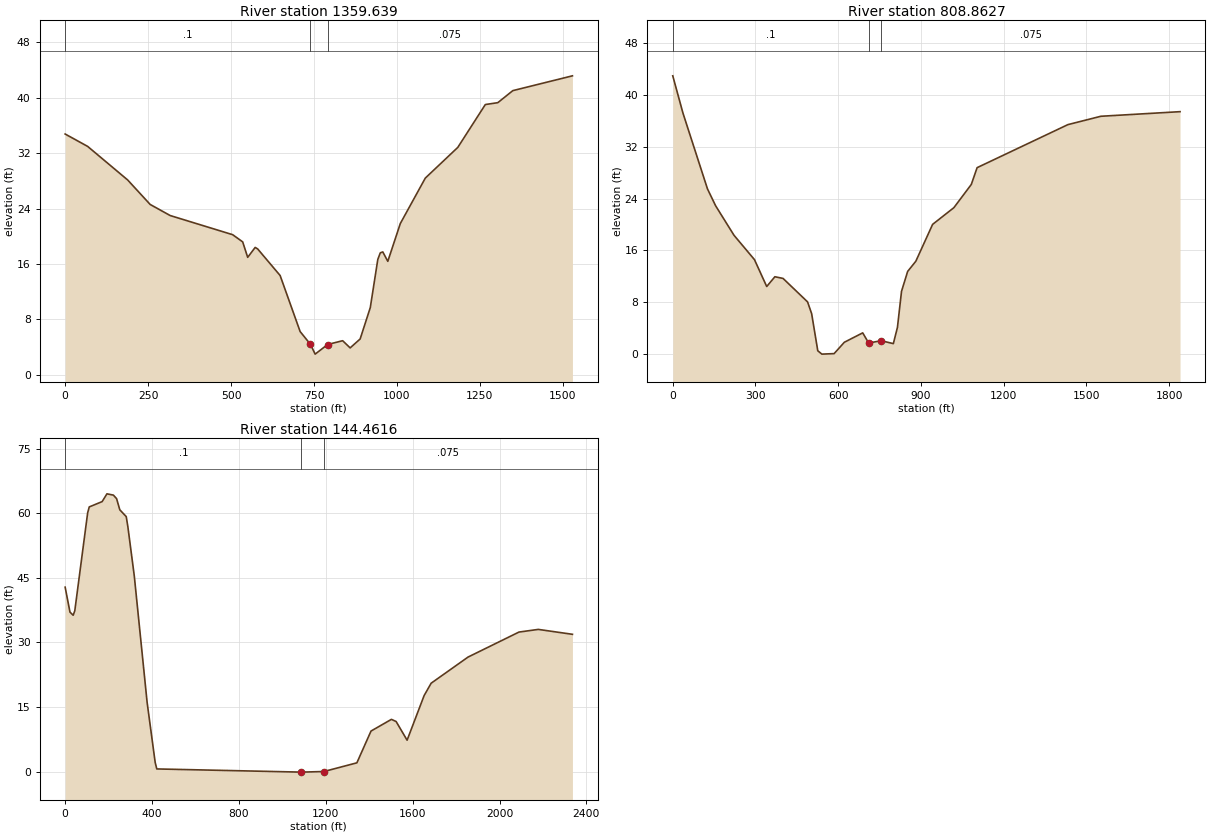
Type RM Length L Ch R = 1 ,1359.639,519.01,550.78,581.4
XS GIS Cut Line= 4
1577713.90659498690161.9043761941577488.00146799689595.062747046
1577376.24988449689314.6554341611577147.93430169688741.765484199
#Sta/Elev= 30
       0   34.77   67.82   32.98  188.39   28.13   256.2   24.59  316.49   22.99
  504.87   20.22  535.02   19.18  550.09   16.95  572.69   18.38  580.23   18.16
  647.88   14.32  708.16    6.22  739.31    4.37  753.37    2.96  791.05    4.35
  836.26     4.9  858.87    3.86  889.01    5.15  919.59    9.69  942.19   16.64
  949.73    17.6  957.27   17.73  972.34   16.37 1010.01   21.83 1085.37    28.4
 1183.33   32.84 1266.22   39.03 1303.89    39.3 1349.11   41.04 1528.76   43.18
#Mann= 3 , 0 , 0
       0      .1       0  739.31    .045       0  791.05    .075       0
Bank Sta=739.31,791.05
XS Rating Curve= 0 ,0
Exp/Cntr=0.3,0.1

Type RM Length L Ch R = 1 ,808.8627,525.47,664.4,685.34
XS GIS Cut Line= 4
1578207.68944293690089.5140609741577915.69490531689245.374385118
1577938.17419106688908.1877235321577725.28617898688338.180472255
#Sta/Elev= 30
       0   42.94   37.03   37.18  125.92   25.49  155.55   22.88  222.21   18.33
  296.28   14.58  340.72   10.43  370.35   11.94  399.98   11.68  488.86    8.06
  503.67    6.24  525.89     .52  540.71       0  585.15     .08  622.18    1.83
  688.85    3.28  710.46    1.71  755.51    2.07  799.95    1.62  814.77    4.13
  829.58    9.69   851.8   12.76  881.43   14.33  942.33   20.02  1019.5    22.6
 1082.64   26.18 1103.68   28.77  1432.9   35.41 1552.46    36.7 1839.62   37.41
#Mann= 3 , 0 , 0
       0      .1       0  710.46    .045       0  755.51    .075       0
Bank Sta=710.46,755.51
XS Rating Curve= 0 ,0
Exp/Cntr=0.3,0.1

Type RM Length L Ch R = 1 ,144.4616,83.7,144.46,121.42
XS GIS Cut Line= 4
1578775.75913006690261.4763555231578477.71018545689394.424283847
1578644.79810588688744.1352301091578270.61160778688096.978840277
#Sta/Elev= 30
       0   42.84   22.21   37.05   37.01   36.32   44.41   37.36  103.63   60.12
  111.03   61.49  170.25   62.72  192.45   64.53  222.06   64.23  236.86   63.41
  251.67   60.82  281.28   59.23  288.68   56.92  318.29   45.47   377.5   16.04
  414.51    2.13  421.92     .61 1087.82    -.13 1191.49     .01 1343.27    2.03
 1408.31    9.41 1502.27   12.13 1523.95   11.63 1574.54    7.29 1652.95   17.66
  1685.3   20.53  1855.1    26.6 2089.59   32.41 2178.54   33.03 2335.82   31.89
#Mann= 3 , 0 , 0
       0      .1       0 1087.82    .045       0 1191.49    .075       0
Bank Sta=1087.82,1191.49
XS Rating Curve= 0 ,0
Exp/Cntr=0.3,0.1

Chan Stop Cuts=-1
Use User Specified Reach Order=0