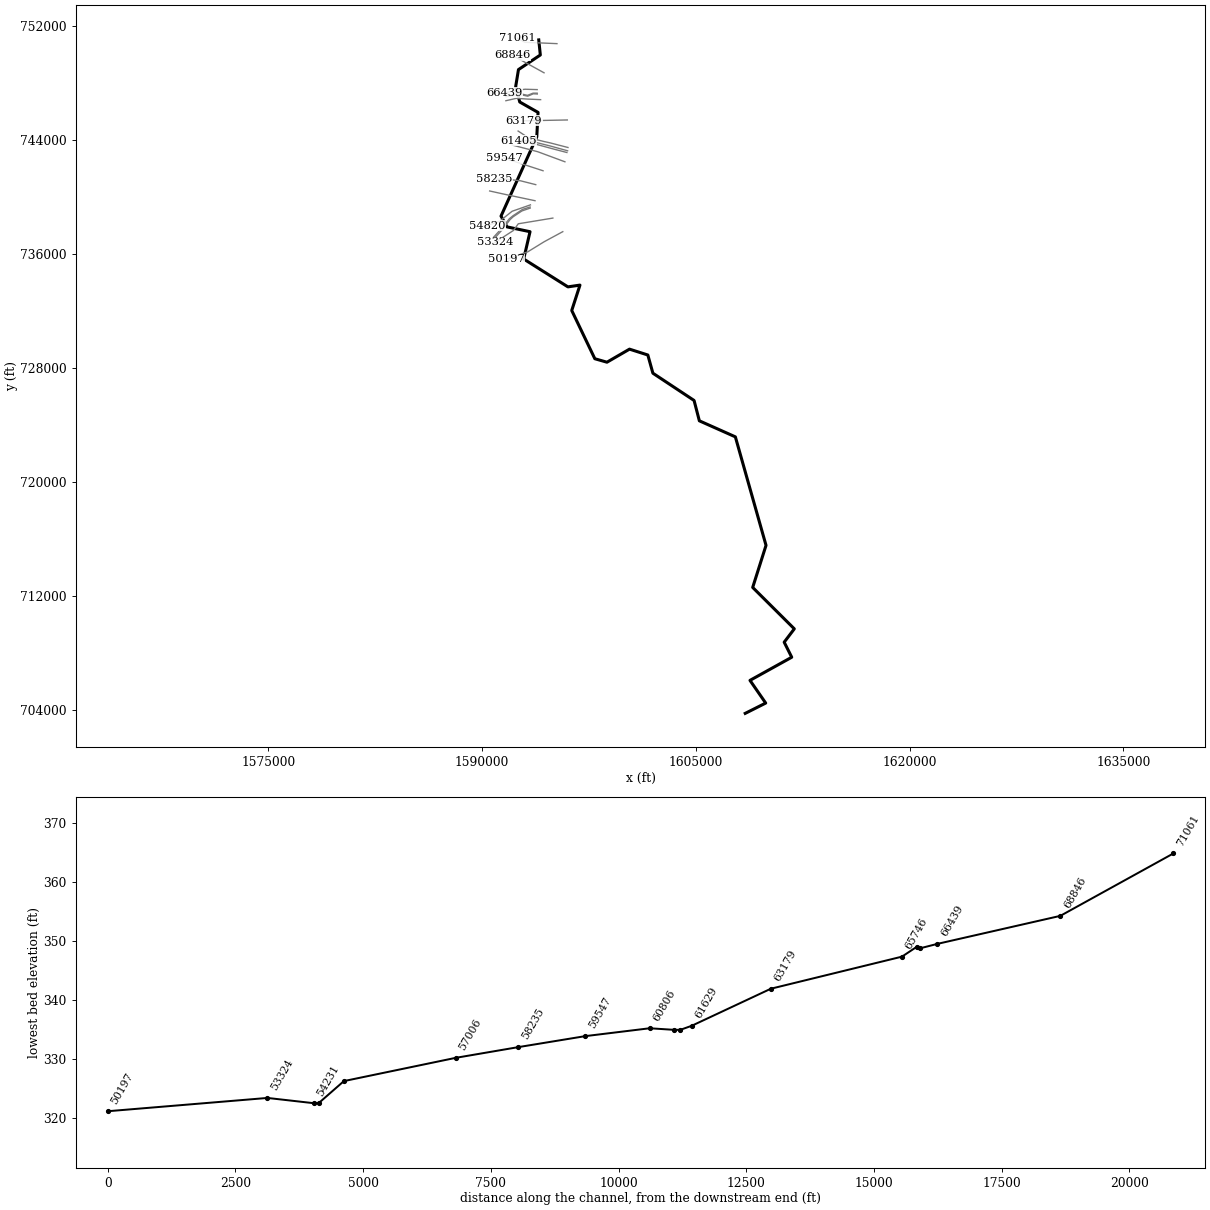
--- NortheastCreek.prj (project) ---

Proj Title=Northeast Creek
Current Plan=p05
Default Exp/Contr=0.3,0.1
English Units
Geom File=g04
Flow File=f03
Flow File=f01
Plan File=p05
Plan File=p01
Y Axis Title=Elevation
X Axis Title(PF)=Main Channel Distance
X Axis Title(XS)=Station
BEGIN DESCRIPTION:
Northeast Creek - Georeferenced HEC-RAS model.
Projection:  MD Stateplane.  Horizontal datum:  NAD83.  Vertrial datum: NAVD88.  Units:Feet.  Created by: Andy Richter, USACE- St Louis District as part of FEMA Map Modernization study for Cecil County, MD.
END DESCRIPTION:
DSS Export Rating Curves= 0
DSS Export Rating Curve Sorted= 0
DSS Export Volume Flow Curves= 0
DXF Filename=Northeast.
DXF OffsetX= 0
DXF OffsetY= 0
DXF ScaleX= 1
DXF ScaleY= 10

--- NortheastCreek.p05 (plan) ---

Plan Title=Northeast Creek Frequency Profiles
Program Version=4.00
Short Identifier=freq
Geom File=g04
Flow File=f03
Subcritical Flow
K Sum by GR= 0
Std Step Tol= 0.01
Critical Tol= 0.01
Num of Std Step Trials= 20
Max Error Tol= 0.3
Flow Tol Ratio= 0.001
Split Flow NTrial= 30
Split Flow Tol= 0.02
Split Flow Ratio= 0.02
Log Output Level= 0
Friction Slope Method= 1
Unsteady Friction Slope Method= 2
Unsteady Bridges Friction Slope Method= 1
Parabolic Critical Depth
Global Vel Dist= 0 , 0 , 0
Global Log Level= 0
CheckData=True
Encroach Param=-1 ,0,0, 2
Encroach River=Northeast Creek
Encroach Reach=Upper
Encroach Node=13828.13
       1 1405.47 1489.56
Encroach Node=13323.49
       1    1140    1230
Encroach Node=12071.43
       1    1101    1208
Encroach Node=11357.49
       1    1300    1685
Encroach Node=10891.71
       1      50     460
Encroach Node=10648.74
       1       0     450
Encroach Node=10225.80
       1       0     450
Encroach Node=8896.106
       1    1600    2800
Encroach Node=8469.816
       1    1878    2065
Encroach Node=8297.318
       1    1950    2110
Encroach Node=7971.989
       1 1916.23    2103
Encroach Node=6564.993
       1 1955.28  2076.7
Encroach Node=5990.414
       1 1679.66 2045.22
Encroach Node=5593.078
       1    1800    2225
Encroach Node=5484.180
       1    1875    2260
Encroach Node=5413.169
       1    1980    2325
Encroach Node=5342.771
       1    2000    2517
Encroach Node=5275.623
       1    2108    2800
Encroach Node=4788.791
       1    2050    2300
Encroach Node=3782.652
       1  1092.5    2040
Encroach Node=3674.989
       1     600    2145
Encroach Node=2751.049
       1    2000    2600
Encroach Node=109.1162
       1 2134.86 3180.95
Computation Interval=1HOUR
Output Interval=1HOUR
Run HTab= 0
Run UNet= 0
Run PostProcess= 0
Run WQNet= 0
UNET Theta= 1
UNET Theta Warmup= 1
UNET ZTol= 0.02
UNET ZSATol= 0.05
UNET MxIter= 20
UNET MaxInSteps= 0
UNET DtIC= 0
UNET DtMin= 0
UNET MaxCRTS= 20
UNET WFStab= 2
UNET SFStab= 1
UNET WFX= 1
UNET SFX= 1
UNET DSS MLevel= 4
UNET DZMax Abort= 100
UNET Convert EG Bridges=-1
UNET Use Existing IB Tables=-1
UNET Froude Reduction=False
UNET Froude Limit= 1
UNET Froude Power= 10
UNET Time Slicing=0,0, 5
Instantaneous Interval=1HOUR
Write IC File= 0
Echo Input=False
Echo Output=False
Write Detailed= 0
Detailed Automatic Start=False, 10
WQ ULTIMATE=-1
WQ Max Comp Step=1HOUR
WQ Output Interval=15MIN
WQ Output Selected Increments= 0
WQ Output face flow=0
WQ Output face velocity=0
WQ Output face area=0
WQ Output face dispersion=0
WQ Output cell volume=0
WQ Output cell surface area=0
WQ Output cell continuity=0
WQ Output face conc=0
WQ Output face dconc_dx=0
WQ Output face courant=0
WQ Output face peclet=0
WQ Output face adv mass=0
WQ Output face disp mass=0
WQ Output cell mass=0
WQ Output cell source sink temp=0
WQ Output cell source sink nsm=0
WQ Output MaxMinRange=-1
WQ Daily Max Min Mean=-1
WQ Daily Range=0
WQ Daily Time=0
WQ Create Restart=0
WQ Fixed Restart=0
WQ System Summary=False
Sorting and Armoring Iterations= 10
XS Update Threshold= 0.02
Hydraulics Update Threshold= 0.02
Energy Slope Method= 1
Volume Change Method= 0
XS Weighting Method= 0
Number of US Weighted Cross Sections= 1
Number of DS Weighted Cross Sections= 1
Upstream XS Weight=0.25
Main XS Weight=0.5
Downstream XS Weight=0.25
Number of DS XS's Weighted with US Boundary= 1
Upstream Boundary Weight= 1
Weight of XSs Associated with US Boundary= 0
Number of US XS's Weighted with DS Boundary= 1
Downstream Boundary Weight= 0.5
Weight of XSs Associated with DS Boundary= 0.5
Sediment Output Level= 4
Mass or Volume Output= 0
Output Increment Type= 1
Profile and TS Output Increment= 10
XS Output Flag= 0
XS Output Increment= 10
Disregard all LS=0
Disregard all Conn=0
Disregard all Breaches=0
Disregard all Pumps=0

--- NortheastCreek.p01 (plan) ---

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Plan Title=Northeast Creek Floodway Profiles
Short Identifier=floodway
Geom File=g04
Flow File=f01
Encroach Node=10099
       1 1421.97 1476.35
Encroach Node=9726
       1  1135.2 1222.61
Encroach Node=9170
       1  512.54  615.64
Encroach Node=8566
       1     390     500
Encroach Node=8098
       1  472.95     580
Encroach Node=7629
       1    1250    1950
Encroach Node=7162
       1     260     600
Encroach Node=6919
       1     180     500
Encroach Node=6497
       1       0     700
Encroach Node=6127
       1     245    1050
Encroach Node=5500
       1     838    1270
Encroach Node=4741
       1  1458.5    1665
Encroach Node=4569
       1    1488    1645
Encroach Node=4315
       1     390     620
Encroach Node=3907
       1  207.59     310
Encroach Node=3753
       1     300     425
Encroach Node=3698
       1     310     440
Encroach Node=2836
       1     700     890
Encroach Node=2261
       1    1110    1430
Encroach Node=1855
       1    1865    2180
Encroach Node=1747
       1    1970    2230
Encroach Node=1684
       1    2050    2340
Encroach Node=1631
       1    2200    2550
Encroach Node=1531
       1    2350    2640
BEGIN DESCRIPTION:
floodway starts at station 1531 and ends at 10099.  Downstream of detailed reach is tidal flooding and upstream of detailed reach is approximate study.
END DESCRIPTION:

--- NortheastCreek.f03 (steady flow) ---

Flow Title=Northeast Creek Frequency Flows
Program Version=4.00
Number of Profiles= 5
Profile Names=10yr,50yr,100yr,500yr,100ult
River Rch & RM=Northeast Creek,Upper           ,71061
    1790    3670    4830    8750    4830
River Rch & RM=Northeast Creek,Upper           ,68846
    1910    3880    5100    9190    5100
River Rch & RM=Northeast Creek,Upper           ,66439
    2010    4080    5350    9610    5360
River Rch & RM=Northeast Creek,Upper           ,61629
    2530    5090    6650   11800    6670
River Rch & RM=Northeast Creek,Upper           ,58235
    2630    5280    6890   12200    6940
River Rch & RM=Northeast Creek,Upper           ,54820
    2800    5600    7300   12900    7340
River Rch & RM=Northeast Creek,Upper           ,50197
    2940    5860    7640   13500    7700
River Rch & RM=Northeast Creek,Upper           ,48597
    3280    6520    8480   14900    8530
River Rch & RM=Northeast Creek,Upper           ,44066
    3440    6810    8850   15500    8910
River Rch & RM=Northeast Creek,Upper           ,40371
    3570    7060    9170   16100    9210
River Rch & RM=Northeast Creek,Upper           ,32120
    3790    7480    9710   17000    9750
River Rch & RM=Northeast Creek,Upper           ,30853
    3800    7500    9740   17000    9780
River Rch & RM=Northeast Creek,Upper           ,28434
    3830    7550    9790   17100    9830
River Rch & RM=Northeast Creek,Upper           ,26478
    3880    7640    9910   17300    9960
River Rch & RM=Northeast Creek,Upper           ,17061
    3933    7758   10088   17497   10285
River Rch & RM=Northeast Creek,Upper           ,10920
    3971    7887   10242   17835   10528
River Rch & RM=Northeast Creek,Upper           ,6497
    3988    7941   10309   17982   10592
River Rch & RM=Northeast Creek,Upper           ,6127
    5458   10906   14065   24323   14932
River Rch & RM=Northeast Creek,Upper           ,-978
    5537   11123   14365   24891   15299
River Rch & RM=Northeast Creek,Upper           ,-3619
    5578   11165   14506   25175   15513
Boundary for River Rch & Prof#=Northeast Creek,Upper           , 1
Up Type= 0
Dn Type= 3
Dn Slope=0.0001
DSS Import GetInterval= 0
DSS Import GetPeak= 0
DSS Import FillOption= 0

--- NortheastCreek.f01 (steady flow) ---

Flow Title=Northeast Creek Floodway Flows
Program Version=4.00
Number of Profiles= 2
Profile Names=100yr,100yr-encroached
River Rch & RM=Northeast Creek,Upper           ,71061
    4830    4830
River Rch & RM=Northeast Creek,Upper           ,68846
    5100    5100
River Rch & RM=Northeast Creek,Upper           ,66439
    5350    5350
River Rch & RM=Northeast Creek,Upper           ,61629
    6650    6650
River Rch & RM=Northeast Creek,Upper           ,58235
    6890    6890
River Rch & RM=Northeast Creek,Upper           ,54820
    7300    7300
River Rch & RM=Northeast Creek,Upper           ,50197
    7640    7640
River Rch & RM=Northeast Creek,Upper           ,48597
    8480    8480
River Rch & RM=Northeast Creek,Upper           ,44066
    8850    8850
River Rch & RM=Northeast Creek,Upper           ,40371
    9170    9170
River Rch & RM=Northeast Creek,Upper           ,32120
    9710    9710
River Rch & RM=Northeast Creek,Upper           ,30853
    9740    9740
River Rch & RM=Northeast Creek,Upper           ,28434
    9790    9790
River Rch & RM=Northeast Creek,Upper           ,26478
    9910    9910
River Rch & RM=Northeast Creek,Upper           ,17061
   10088   10088
River Rch & RM=Northeast Creek,Upper           ,10920
   10242   10242
River Rch & RM=Northeast Creek,Upper           ,6497
   10309   10309
River Rch & RM=Northeast Creek,Upper           ,6127
   14065   14065
River Rch & RM=Northeast Creek,Upper           ,-978
   14365   14365
River Rch & RM=Northeast Creek,Upper           ,-3619
   14506   14506
Boundary for River Rch & Prof#=Northeast Creek,Upper           , 1
Up Type= 0
Dn Type= 3
Dn Slope=0.0001
Set Internal Change=Northeast Creek ,Upper           ,1531    , 2 , 3 ,14.12
DSS Import GetInterval= 0
DSS Import GetPeak= 0
DSS Import FillOption= 0

--- NortheastCreek.g04 (geometry) ---

Geom Title=Northeast Creek Geometry
Program Version=4.00
BEGIN GEOM DESCRIPTION:
stationing referenced to West Cecil Road (State Route 7)
END GEOM DESCRIPTION:

River Reach=Northeast Creek ,Upper
Reach XY= 30
1593974.55999948751044.3600025331594084.39000131749984.309999481
1592550.64999965748959.1100025481592354.87999918747767.270002365
1592641.37999921746682.3900013271593925.86000256745951.809999481
1593835.12999916744231.3700008541591325.86000256738669.920000091
1591750.84000209737910.6900005641593361.45000267737573.579999954
1592917.37999916735656.4100017851596021.12999918733699.140001312
1596866.30999951733823.2900028381596289.01000023732040.770002395
1597910.12999916  728651.95000271598760.07999997728408.420000106
1600342.98999979729325.2300014791601629.37999916728914.579999939
1601984.52000241727636.3099994961604874.80999951725720.969999313
1605245.02000237724291.8900013271607772.21999931723165.780000716
1609924.17000008715545.1200008541608988.54000282712589.910001785
1611909.50000192709681.5799999391611198.50000191 708745.41000177
 1611728.5300007707687.750001922 1608799.2000027706062.510000259
1609901.12999916704468.4400005641608463.85000041703745.020002395

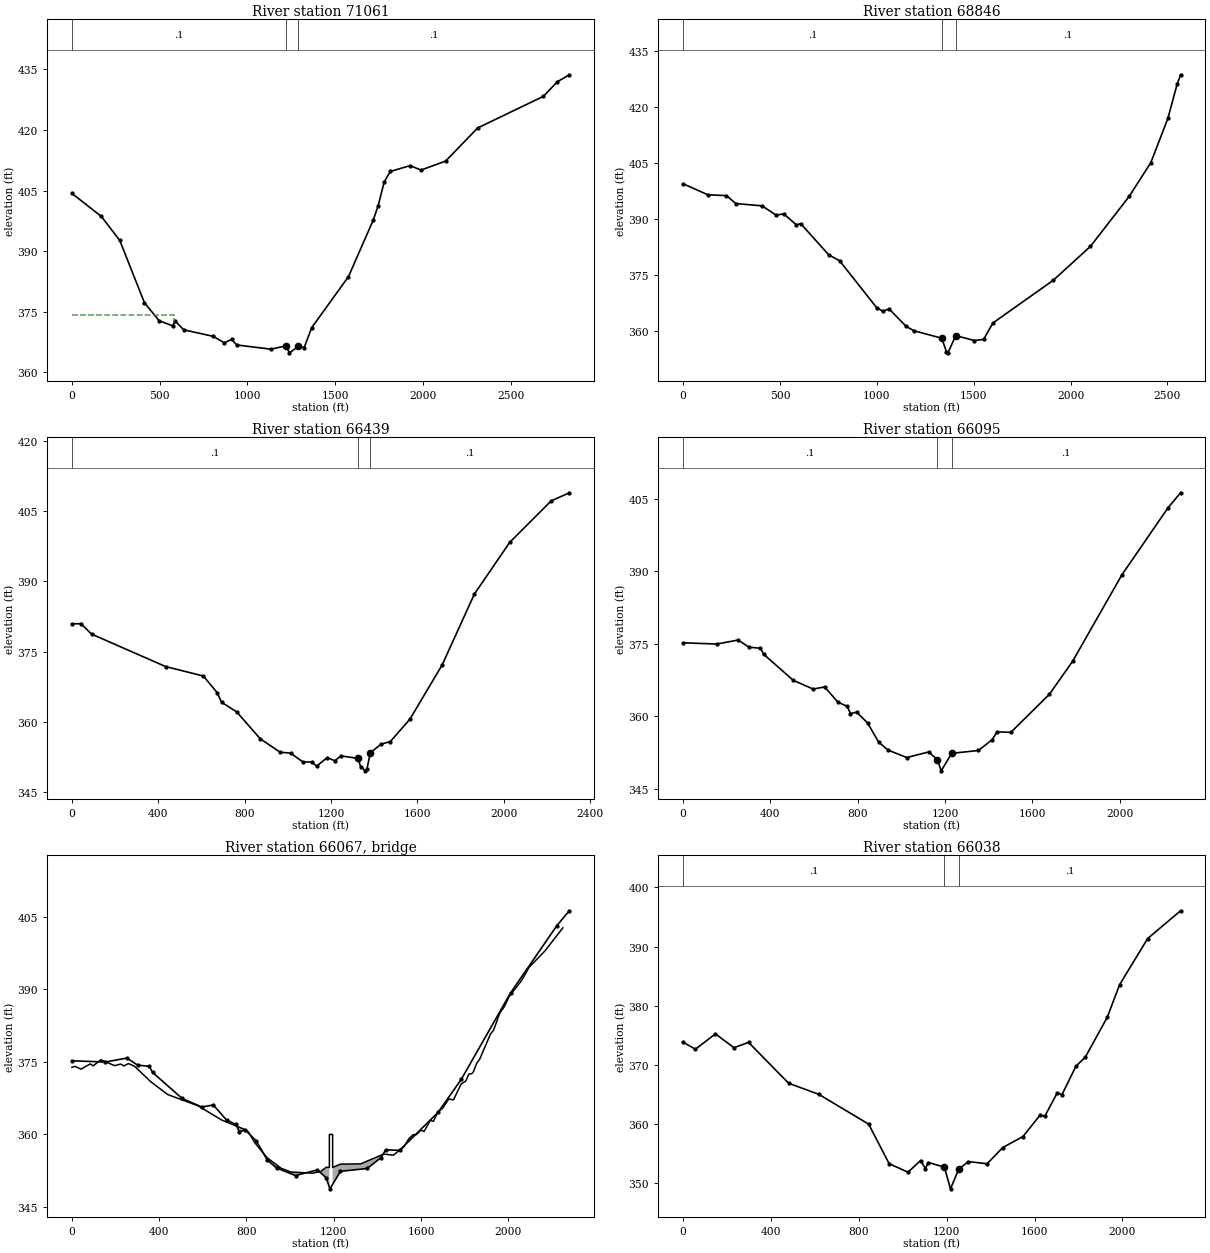
Type RM Length L Ch R = 1 ,71061   ,2080.06,2215.11,1818.48
XS GIS Cut Line= 3
1595252.83348469750781.5787487331592998.13755991750877.933275253
1592490.67038538751154.149585754
#Sta/Elev= 30
       0   404.3  168.15  398.58  273.25  392.63  413.38  377.24  497.45  372.77
  574.52   371.5  588.54  372.69  637.58  370.52  805.74   368.9  868.79   367.3
  910.83  368.14  938.86  366.77 1135.04  365.72 1219.11  366.55 1240.13  364.82
 1291.12  366.43 1324.21  366.14 1366.24  371.02 1576.44  383.69 1716.56  397.59
 1744.59  401.09 1779.62  407.09 1814.65  409.71 1926.75  411.16 1989.81  410.07
 2129.94  412.28 2312.54  420.49 2687.11  428.31 2766.81  431.93 2834.52  433.65
#Mann= 3 , 0 , 0
       0      .1       0 1219.11    .045       0 1291.12      .1       0
#XS Ineff= 2 , 0
          584.46  374.23
Permanent Ineff=
       F       F
Bank Sta=1219.11,1291.12
XS Rating Curve= 0 ,0
Exp/Cntr=0.3,0.1

Type RM Length L Ch R = 1 ,68846   ,2008.55,2407.14,2327.73
XS GIS Cut Line= 2
 1594347.1009331748733.0815124661592098.82864383 749972.84308818
#Sta/Elev= 30
       0  399.48   127.9  396.53  223.82  396.31  271.79  394.19  407.68  393.57
  479.62   391.1  519.59  391.42  583.54  388.53  607.52  388.78  751.41  380.47
  807.37   378.9  999.21  366.32 1031.19  365.38 1063.16  365.99  1151.1  361.34
 1191.06  360.17 1334.95  358.16 1358.93  354.58 1366.93  354.25  1406.9  358.86
 1502.82  357.55 1550.78  357.85 1598.75  362.23  1910.5  373.66 2102.35  382.73
  2302.2   396.1 2414.11  405.15 2502.04  416.97    2550  426.17 2567.44  428.64
#Mann= 3 , 0 , 0
       0      .1       0 1334.95    .045       0  1406.9      .1       0
Bank Sta=1334.95,1406.9
XS Rating Curve= 0 ,0
Exp/Cntr=0.3,0.1

Type RM Length L Ch R = 1 ,66439   ,320.68,343.52,248.51
XS GIS Cut Line= 5
1593865.19634056747553.1572990721593021.23559192747579.081007034
1592589.17377666 747530.114000351592374.40258981747471.479576141
1591584.29547124747336.583238631
#Sta/Elev= 30
       0  380.92   42.02  380.96   91.04  378.74   434.2   371.8  609.29  369.77
  672.32  366.25  693.33  364.16  763.36  362.11  872.54  356.36  964.12   353.5
 1013.43  353.29 1069.79   351.4 1112.06   351.4  1133.2  350.52 1182.51  352.33
 1217.73  351.67 1245.91   352.7 1324.89  352.18 1337.24  350.43    1359  349.51
 1366.26  349.85 1382.02  353.37 1431.57   355.2  1475.1  355.78 1565.73  360.57
 1714.86  372.16 1863.99  387.29 2027.32  398.33 2219.05  407.18 2303.36  408.94
#Mann= 3 , 0 , 0
       0      .1       0 1324.89    .045       0 1382.02      .1       0
Bank Sta=1324.89,1382.02
XS Rating Curve= 0 ,0
Exp/Cntr=0.5,0.3

Type RM Length L Ch R = 1 ,66095   ,58.7,57.21,63.48
XS GIS Cut Line= 5
1593865.19634056747302.5614452511593570.98554425747303.586933151
 1593185.4190827 747149.899602891592646.78201866747270.876911178
 1591638.6377812747129.736717254
#Sta/Elev= 30
       0  375.23     154  374.98     252   375.8  301.75  374.33   354.5   374.1
  369.57  372.84  505.21  367.45  595.64  365.67  648.39   366.1  709.28  362.96
  752.33  362.07  766.68  360.58  795.37  360.88  845.59  358.63  895.81  354.69
  938.86  353.04 1024.95   351.5  1125.4  352.66 1164.96  351.05 1182.79  348.75
  1230.6  352.37 1353.22  352.96 1416.84  355.22 1438.04  356.82 1501.66  356.71
 1678.36  364.58 1784.39  371.39 2010.57  389.29 2222.62   403.2 2279.31  406.26
#Mann= 3 , 0 , 0
       0      .1       0 1164.96    .045       0  1230.6      .1       0
Bank Sta=1164.96,1230.6
XS Rating Curve= 0 ,0
Exp/Cntr=0.5,0.3

Type RM Length L Ch R = 3 ,66067   ,,,
BEGIN DESCRIPTION:
Fell Road Bridge - Bridge Deck Out, but embankments still in place (15' wide opening), CE041807PF-6
END DESCRIPTION:
Bridge Culvert--1,0,-1,-1, 0
Deck Dist Width WeirC Skew NumUp NumDn MinLoCord MaxHiCord MaxSubmerge Is_Ogee
15,21,2.6,0, 60, 60, , , 0.98, 0, 0,0,,
       0      14   42.01   84.03   98.03  133.05  196.07  224.08  238.08  259.09
   287.1  363.51  439.91  577.44  686.65  795.46  809.78  838.44  895.74  960.21
 1003.19 1103.47 1139.29 1166.02    1180    1180    1195    1195 1229.93 1323.71
 1429.92 1472.41 1521.97 1543.22 1564.46 1578.62 1599.86 1614.03 1642.35 1656.51
 1677.75    1699 1727.32 1748.56 1783.97 1805.21 1819.37 1833.53 1840.62 1854.78
 1868.94 1918.51 1932.67 1960.99 1982.23 2003.48 2060.12 2095.53 2166.34    2250
  373.87  374.09   373.5  374.59  374.19  375.45  374.23  374.56  374.16  374.66
  374.11  370.83  368.24  365.94  362.98  360.97   360.5  358.27  355.14  352.98
  352.24  351.99   352.3  353.23  353.17     360     360  353.17  353.86  353.92
  355.95   355.7  357.45  359.06  359.97  359.96  360.91  360.61  362.91   362.7
  364.66  365.41  367.34  367.14  370.46  371.05   372.5  372.57  373.03  374.68
  375.57  380.78  381.58  385.12  386.45  388.52  391.79  394.58  397.88  402.73
                                                                                
                                                                                
                                             360     360
                                                                                
                                                                                
                                                                                
      35      49   77.01  119.03  133.03  168.05  231.07  259.08  273.08  294.09
   322.1  398.51  474.91  612.44  721.65  830.46  844.78  873.44  930.74  995.21
 1038.19 1138.47 1174.29 1201.02    1215    1215    1230    1230 1264.93 1358.71
 1464.92 1507.41 1556.97 1578.22 1599.46 1613.62 1634.86 1649.03 1677.35 1691.51
 1712.75    1734 1762.32 1783.56 1818.97 1840.21 1854.37 1868.53 1875.62 1889.78
 1903.94 1953.51 1967.67 1995.99 2017.23 2038.48 2095.12 2130.53 2201.34    2285
  373.87  374.09   373.5  374.59  374.19  375.45  374.23  374.56  374.16  374.66
  374.11  370.83  368.24  365.94  362.98  360.97   360.5  358.27  355.14  352.98
  352.24  351.99   352.3  353.23  353.17     360     360  353.17  353.86  353.92
  355.95   355.7  357.45  359.06  359.97  359.96  360.91  360.61  362.91   362.7
  364.66  365.41  367.34  367.14  370.46  371.05   372.5  372.57  373.03  374.68
  375.57  380.78  381.58  385.12  386.45  388.52  391.79  394.58  397.88  402.73
                                                                                
                                                                                
                                             360     360
                                                                                
                                                                                
                                                                                
BR Coef=-1 , 0 , 0 ,, 0 ,,,0.8,-1,,0,
WSPro=,,,, 1 ,,,, 0 ,,,, 0 ,,,,-1 ,-1 ,-1 , 0 , 0 , 0 , 0 , 0
BC Design=,, 0 ,, 0 ,,,,,,
BC Use User HTab Curves=0
BC User HTab FreeFlow(D)= 0

Type RM Length L Ch R = 1 ,66038   ,278.06,292.02,248.29
XS GIS Cut Line= 5
1593873.83757594747244.953203231   1593591.55719747259.355262786
1593199.82114226 747092.291360871592643.90160564747213.268669158
1591670.32231335747051.965591446
#Sta/Elev= 30
       0  373.82   56.07  372.65  147.19  375.24   231.3   372.9  297.87   373.8
  480.51  366.88  617.49  365.02  844.63  359.97  937.76  353.29 1023.73  351.84
 1081.04  353.82 1102.53  352.46 1116.86  353.48 1189.21  352.71 1217.15  349.03
 1254.88  352.38 1298.74  353.64 1383.88  353.27 1454.84  356.01 1547.08  357.88
 1625.13  361.51 1646.41  361.31 1703.18  365.28 1724.46  364.95 1788.32  369.78
  1830.9  371.31 1930.23  378.01    1987  383.57 2114.71  391.37 2264.31  396.06
#Mann= 3 , 0 , 0
       0      .1       0 1189.21    .045       0 1254.88      .1       0
Bank Sta=1189.21,1254.88
XS Rating Curve= 0 ,0
Exp/Cntr=0.5,0.3

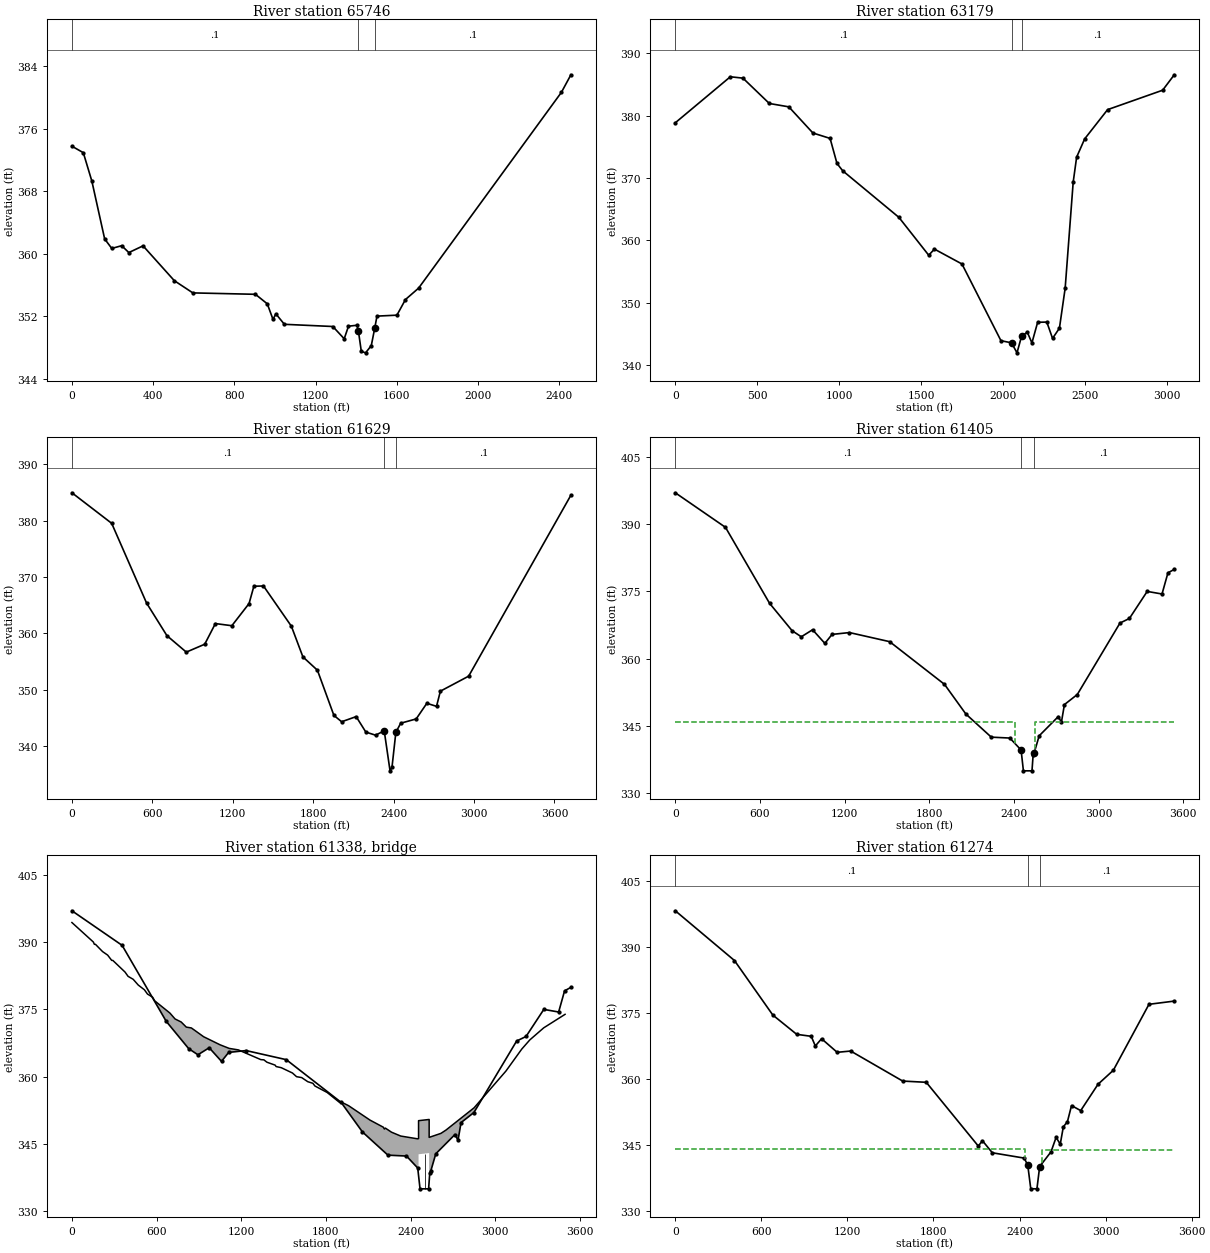
Type RM Length L Ch R = 1 ,65746   ,2110.34,2567.38,2274.28
XS GIS Cut Line= 4
  1594104.270546746847.456331283 1593170.9333439746888.855871215
1592406.52076535746940.2449531851591667.80272867746773.230440155
#Sta/Elev= 30
       0  373.79   56.06  372.96    98.1  369.33  161.16  361.93  196.19  360.71
  245.24  361.06  280.28  360.18  350.34  361.04   504.5  356.58  595.59  355.02
  903.89  354.84  962.32  353.62  990.38  351.63 1004.41  352.34 1046.51     351
 1285.04  350.72 1341.17  349.15 1362.22  350.76 1404.31  350.88 1411.33  350.09
 1425.36  347.54 1446.41  347.35 1474.47  348.27 1491.61  350.52 1502.53  352.05
 1600.75  352.17 1642.85  354.17 1707.57  355.63 2410.88  380.68 2457.75  382.93
#Mann= 3 , 0 , 0
       0      .1       0 1411.33    .045       0 1491.61      .1       0
Bank Sta=1411.33,1491.61
XS Rating Curve= 0 ,0
Exp/Cntr=0.3,0.1

Type RM Length L Ch R = 1 ,63179   ,1378.43,1549.19,1284.1
XS GIS Cut Line= 2
1595979.34661488 745421.055248291592933.25884444745361.957805648
#Sta/Elev= 30
       0  378.87  336.06  386.26  413.08  386.04  574.11  381.97  693.13  381.43
  840.16  377.23  945.18  376.36  987.19  372.34 1022.19  371.16 1365.26  363.68
 1547.29   357.6  1582.3  358.58 1750.33  356.19 1988.38  343.87 2052.83  343.53
  2086.4  341.92  2114.4   344.6 2149.41  345.23 2177.41  343.51 2212.42  346.83
 2268.43  346.86 2303.44  344.24 2345.44  345.88 2380.45   352.3 2429.46  369.34
 2450.46  373.35 2499.47  376.28 2639.49  380.98 2975.55   384.1 3046.65  386.58
#Mann= 3 , 0 , 0
       0      .1       0 2052.83    .045       0  2114.4      .1       0
Bank Sta=2052.83,2114.4
XS Rating Curve= 0 ,0
Exp/Cntr=0.3,0.1

Type RM Length L Ch R = 1 ,61629   ,202.84,224.43,213.76
XS GIS Cut Line= 5
1596025.70584112743487.3411502991594760.24972346743814.946540847
1594297.74799541743917.7247028651593212.15366176744193.941011444
1592524.82470517744643.595470428
#Sta/Elev= 30
       0  384.93  296.46  379.52  556.77  365.39  708.62  359.61  853.23  356.69
  990.62  358.09 1070.15  361.75 1193.08  361.37 1321.51   365.3 1357.37  368.37
 1429.08  368.41 1637.03  361.29 1723.08  355.85 1831.52  353.48 1954.31  345.48
 2012.09  344.35 2120.44  345.26 2192.67  342.52  2264.9  341.97 2329.91  342.74
 2373.25  335.65  2387.7  336.27 2416.59  342.47 2452.71  344.09 2568.28  344.85
 2647.73  347.62 2719.96  347.08 2748.85  349.77 2959.71  352.43 3722.51   384.5
#Mann= 3 , 0 , 0
       0      .1       0 2329.91    .045       0 2416.59      .1       0
Bank Sta=2329.91,2416.59
XS Rating Curve= 0 ,0
Exp/Cntr=0.5,0.3

Type RM Length L Ch R = 1 ,61405   ,131.99,131.25,127.58
XS GIS Cut Line= 6
1595998.61751939743257.5749435571594784.55048373743591.603969604
1593782.46340756743842.1257381591593307.11440852743944.903900176
1592925.47789194743984.646741897 1592551.6644097 743974.40527536
#Sta/Elev= 30
       0  397.04  355.75  389.32  667.93  372.37  827.65  366.25  892.99  364.89
  972.86  366.46 1059.98  363.42  1110.8  365.42 1234.22  365.83 1519.11   363.8
 1907.72  354.27 2059.12  347.65 2239.35  342.48 2370.89  342.28 2450.52  339.61
    2467  334.96 2527.76  334.96 2535.62   338.4 2542.46  338.87 2578.59  342.78
 2714.66  347.09 2736.15   345.8 2757.63  349.75 2848.83     352 3151.46  367.96
 3218.17  368.98 3344.22  375.02 3449.26  374.44 3491.28  379.17 3536.11  379.94
#Mann= 3 , 0 , 0
       0      .1       0 2450.52    .045       0 2542.46      .1       0
#XS Ineff= 2 , 0
         2409.91  345.86 2549.55          345.86
Permanent Ineff=
       F       F
Bank Sta=2450.52,2542.46
XS Rating Curve= 0 ,0
Exp/Cntr=0.5,0.3

Type RM Length L Ch R = 3 ,61338   ,,,
BEGIN DESCRIPTION:
Telegraph Road, CE041807PF-5, invert elevations adjusted based on bridge survey
END DESCRIPTION:
Bridge Culvert--1,0,-1,-1, 0
Deck Dist Width WeirC Skew NumUp NumDn MinLoCord MaxHiCord MaxSubmerge Is_Ogee
40,48,2.6,0, 60, 60, , , 0.98, 0, 0,0,,
       0  151.95  159.18  166.42  217.07  253.24  282.19  289.42  376.25  397.95
  434.13  470.31  513.72  535.43  571.61  586.08  694.61  730.79   774.2  810.38
  846.56  933.38 1049.15 1114.27 1179.39 1338.58 1360.28 1381.99 1439.88 1447.11
 1483.29 1562.88 1591.82    1628 1671.41 1707.59 1722.06 1808.89 1895.72 1910.19
 1960.84 2112.79 2206.85 2214.08 2221.32 2264.73 2329.85 2449.26 2456.46 2456.46
 2531.57 2531.57 2614.68 2650.64 2850.25 3075.75 3188.01 3245.22 3343.65 3494.71
  394.41  390.06  389.55  389.56  387.93  387.14  385.95  385.97  383.36   382.4
  381.74  380.45   379.4  378.45  377.75  376.95   374.2  372.89  372.21  371.07
  370.88  368.92  367.13  366.32  365.98  363.81  363.76  363.23  362.58  362.26
  362.01  360.82     360   359.8  358.88  358.52  357.92  356.47  354.27  354.32
  353.52   350.3  348.72  348.32  348.52  347.61  346.75  346.13  346.18  350.18
  350.45  346.45  347.34  348.08  353.06  361.26  366.17  368.22  370.91  373.92
                                                                                
                                                                                
                                                                                
                                                                                
                                                                          342.68
  342.95
       0  151.95  159.18  166.42  217.07  253.24  282.19  289.42  376.25  397.95
  434.13  470.31  513.72  535.43  571.61  586.08  694.61  730.79   774.2  810.38
  846.56  933.38 1049.15 1114.27 1179.39 1338.58 1360.28 1381.99 1439.88 1447.11
 1483.29 1562.88 1591.82    1628 1671.41 1707.59 1722.06 1808.89 1895.72 1910.19
 1960.84 2112.79 2206.85 2214.08 2221.32 2264.73 2329.85 2449.26 2456.46 2456.46
 2531.57 2531.57 2614.68 2650.64 2850.25 3075.75 3188.01 3245.22 3343.65 3494.71
  394.41  390.06  389.55  389.56  387.93  387.14  385.95  385.97  383.36   382.4
  381.74  380.45   379.4  378.45  377.75  376.95   374.2  372.89  372.21  371.07
  370.88  368.92  367.13  366.32  365.98  363.81  363.76  363.23  362.58  362.26
  362.01  360.82     360   359.8  358.88  358.52  357.92  356.47  354.27  354.32
  353.52   350.3  348.72  348.32  348.52  347.61  346.75  346.13  346.18  350.18
  350.45  346.45  347.34  348.08  353.06  361.26  366.17  368.22  370.91  373.92
                                                                                
                                                                                
                                                                                
                                                                                
                                                                          342.68
  342.95
Pier Skew, UpSta & Num, DnSta & Num=  ,2500, 2 ,2500, 2 , 0 , 0 , 0 ,,
       2       2
     330     350
       2       2
     330     350
BR Coef=-1 , 1 , 0 ,, 0 ,,,0.8,0,2,0,
WSPro=,,,, 1 ,,,, 0 ,,,, 0 ,,,,-1 ,-1 ,-1 , 0 , 0 , 0 , 0 , 0
BC Design=,, 0 ,, 0 ,,,,,,
BC Use User HTab Curves=0
BC User HTab FreeFlow(D)= 0

Type RM Length L Ch R = 1 ,61274   ,474.27,467.23,463.23
XS GIS Cut Line= 6
1595947.22843935743135.5258751211595009.61607555 743380.40028955
1593853.12339216743694.3821296991593307.11440852743816.431198135
1592940.84008986743882.2320881041592561.97273637743854.973009139
#Sta/Elev= 30
       0  398.21  412.38   386.9  680.07  374.49  846.47  370.11  947.76  369.66
  976.31  367.46 1019.83  369.11 1128.61  366.02 1222.89  366.31 1585.49  359.48
 1749.74   359.2 2112.52   344.7 2141.54  345.91 2210.45  343.17 2432.81  341.96
 2457.49  340.32 2478.35  334.99 2521.38  334.97  2540.4  340.04 2619.31  343.38
 2655.17  346.68 2683.86  345.12 2705.38  349.07 2734.02  350.25 2762.47  353.91
 2826.48  352.76 2947.38  358.76 3054.06  361.94 3302.57  376.94 3478.89  377.67
#Mann= 3 , 0 , 0
       0      .1       0 2457.49    .045       0  2540.4      .1       0
#XS Ineff= 2 , 0
         2435.81  344.03    2558          343.76
Permanent Ineff=
       F       F
Bank Sta=2457.49,2540.4
XS Rating Curve= 0 ,0
Exp/Cntr=0.5,0.3

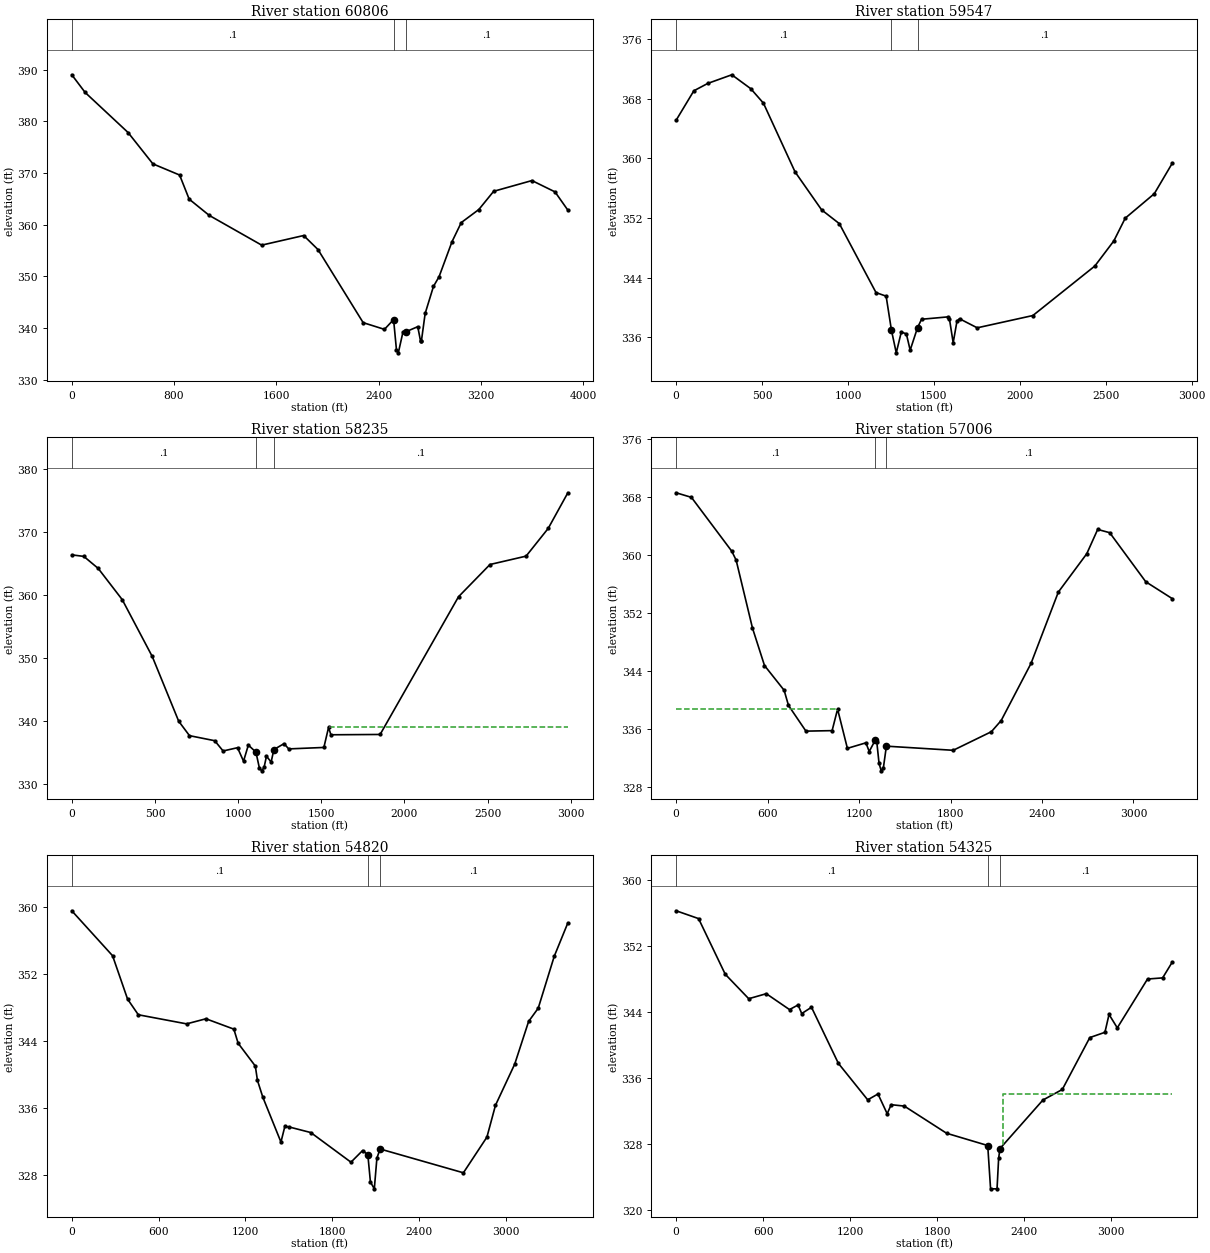
Type RM Length L Ch R = 1 ,60806   ,1137.91,1259.77,1200.24
XS GIS Cut Line= 4
1595810.49866109 742484.27207759 1593903.8701096743190.126773849
1592612.71945383743530.5794353781592116.40213588 743656.91985324
#Sta/Elev= 30
       0  389.01   104.5  385.59  440.39  377.84  634.47  371.78  843.47  369.62
  918.11  364.96 1074.86  361.82  1485.4  356.06 1813.83  357.92  1925.8  355.21
 2279.23  341.07 2445.74  339.77 2517.29  341.66 2539.85  335.78 2554.33  335.23
 2590.52  339.24 2610.81  339.28 2706.35  340.29 2728.07  337.52 2735.31  337.59
 2764.26  342.85 2829.42  348.09 2872.85  349.94  2974.2  356.72  3046.6  360.42
 3184.14  362.95 3299.97  366.47 3599.52  368.55  3780.1  366.36 3880.52  362.83
#Mann= 3 , 0 , 0
       0      .1       0 2517.29    .045       0 2610.81      .1       0
Bank Sta=2517.29,2610.81
XS Rating Curve= 0 ,0
Exp/Cntr=0.3,0.1

Type RM Length L Ch R = 1 ,59547   ,1156.04,1311.61,1269.09
XS GIS Cut Line= 2
1594276.12896158741854.3587398681591531.02635771742748.113077194
#Sta/Elev= 30
       0  365.14  103.06  369.09  184.04  370.08  323.91  371.24  434.34  369.37
  507.95  367.43     692   358.2  846.59   353.1  949.66  351.25 1163.15  341.99
 1222.04  341.51 1253.22   336.9 1280.93   333.9 1310.38   336.7 1339.83  336.44
 1361.91  334.26 1404.78  337.28 1428.17  338.41 1582.76  338.73 1590.12  338.51
 1612.21  335.25 1634.29  338.15 1649.02  338.48 1752.08  337.26    2076  338.91
 2436.71  345.56 2547.14  348.93 2613.39  351.98 2782.71  355.27 2886.93  359.35
#Mann= 3 , 0 , 0
       0      .1       0 1253.22    .045       0 1404.78      .1       0
Bank Sta=1253.22,1404.78
XS Rating Curve= 0 ,0
Exp/Cntr=0.3,0.1

Type RM Length L Ch R = 1 ,58235   ,1152.57,1229.57,1152.11
XS GIS Cut Line= 4
 1593762.5501385740878.9028606711592696.22670941741148.695535675
1591576.25752454741275.7023506311590821.19816019 741256.14970018
#Sta/Elev= 30
       0   366.3   72.21  366.06  158.85  364.15  303.26   359.2  483.78  350.18
  642.63  339.92  707.62  337.62  859.25  336.82  909.79  335.19  996.44  335.71
 1032.54  333.57 1061.43  336.12 1106.97  335.02  1128.1  332.46 1142.19  332.04
 1156.28  332.61 1170.37  334.36 1198.55  333.44 1215.03  335.42 1276.05  336.35
 1304.23  335.52 1515.58  335.75 1543.75  338.93 1557.84  337.76 1853.73  337.81
 2325.12  359.66 2514.18  364.77 2731.26   366.1  2864.3   370.5  2982.4  376.15
#Mann= 3 , 0 , 0
       0      .1       0 1106.97    .045       0 1215.03      .1       0
#XS Ineff= 2 , 0
                         1543.69          339.06
Permanent Ineff=
       F       F
Bank Sta=1106.97,1215.03
XS Rating Curve= 0 ,0
Exp/Cntr=0.3,0.1

Type RM Length L Ch R = 1 ,57006   ,1516.93,2185.86,2151.63
XS GIS Cut Line= 3
1593712.02242471739750.6543045191591581.79764751740201.278778091
 1590530.3405457740433.418657303
#Sta/Elev= 30
       0  368.53  100.17   367.9   364.9  360.48  393.52  359.25  500.84  349.88
  579.55  344.73  708.34  341.32  736.96  339.23  851.43  335.69 1023.15  335.76
 1058.93  338.72 1123.32  333.32 1244.95  334.08 1266.42  332.88 1306.21  334.46
  1316.5  334.14 1330.81  331.28 1345.12  330.22 1359.43  330.64  1379.1  333.62
 1817.35  333.05 2067.77  335.61 2132.16  337.15  2327.9  345.02 2507.11  354.85
 2693.49  360.13 2765.18  363.48 2844.03  363.03 3080.59  356.27 3254.12  353.95
#Mann= 3 , 0 , 0
       0      .1       0 1306.21    .045       0  1379.1      .1       0
#XS Ineff= 2 , 0
          1055.4  338.69
Permanent Ineff=
       F       F
Bank Sta=1306.21,1379.1
XS Rating Curve= 0 ,0
Exp/Cntr=0.3,0.1

Type RM Length L Ch R = 1 ,54820   ,296.63,495.14,491.34
XS GIS Cut Line= 4
1593391.42926408739459.2168769991592103.31560329739008.377096206
1591228.58617404738309.460754424 1590334.6364651738007.611869827
#Sta/Elev= 30
       0  359.58  281.82   354.2  385.65     349  459.82  347.13  793.55  346.04
  927.05  346.65 1119.87  345.41 1149.54  343.72  1268.2  340.99 1283.03  339.27
 1320.12  337.26 1445.37  331.89 1472.26  333.76 1499.14  333.71 1651.46  333.03
 1929.22  329.48 2009.86  330.88  2045.7  330.38 2063.62  327.11  2090.5  326.29
 2108.42  329.97 2130.45  331.06 2706.04  328.21 2868.58  332.48 2927.68  336.29
 3060.67  341.22 3156.72  346.33 3223.21  347.92 3334.03  354.14 3427.92  358.13
#Mann= 3 , 0 , 0
       0      .1       0  2045.7    .045       0 2130.45      .1       0
Bank Sta=2045.7,2130.45
XS Rating Curve= 0 ,0
Exp/Cntr=0.5,0.3

Type RM Length L Ch R = 1 ,54325   ,74.7,93.65,87.42
XS GIS Cut Line= 6
1593366.65784651739310.5883789361592831.59524922739137.188463211
1592157.81272128738686.3486824181591910.44061475738482.222707763
1591358.34619525737793.1746349631590790.43052866737170.337989822
#Sta/Elev= 30
       0  356.32  154.53  355.37  338.49  348.61  500.37  345.64  621.42  346.25
  781.44  344.32   840.4  344.88  865.67  343.84  933.05   344.6 1118.34  337.79
 1320.48  333.36 1391.31  334.07 1454.84  331.67 1482.07  332.77 1572.82   332.6
 1864.31   329.3 2147.92  327.81 2167.53  322.55 2212.05  322.55  2223.1  326.26
 2232.39  327.44 2528.07  333.33 2662.08  334.62 2851.55  340.92 2955.75  341.56
 2984.17  343.73 3041.01   342.1 3249.42  348.03 3353.62  348.17 3419.71  350.08
#Mann= 3 , 0 , 0
       0      .1       0 2147.92    .045       0 2232.39      .1       0
#XS Ineff= 2 , 0
                          2254.5          334.08
Permanent Ineff=
       F       F
Bank Sta=2147.92,2232.39
XS Rating Curve= 0 ,0
Exp/Cntr=0.5,0.3

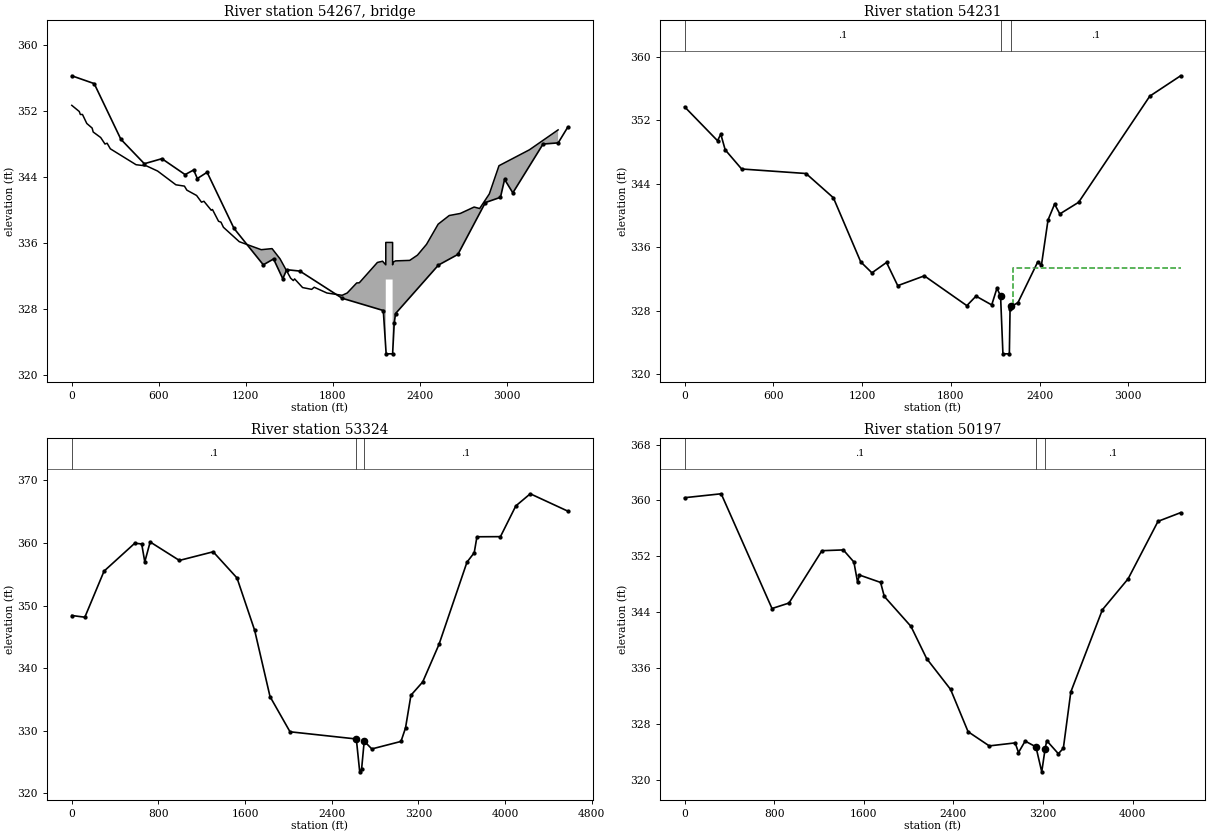
Type RM Length L Ch R = 3 ,54267   ,,,
BEGIN DESCRIPTION:
Calvert Road, CE041807PF-3, invert elevations adjusted based on bridge survey
END DESCRIPTION:
Bridge Culvert--1,0,-1,-1, 0
Deck Dist Width WeirC Skew NumUp NumDn MinLoCord MaxHiCord MaxSubmerge Is_Ogee
45,30,2.6,0, 60, 60, , , 0.98, 0, 0,0,,
       0    51.7   59.08   73.85   103.4  140.32  147.71  199.41  228.95  243.72
  265.87  443.12  516.98  591.78  717.84  776.66  793.47   860.7  894.31  911.12
  961.54  969.95 1011.97 1028.77 1045.58 1154.83 1306.09 1380.99 1435.87 1509.04
 1527.33 1536.48 1591.36 1653.95 1671.45 1758.95 1863.95 1898.95 1964.51 1982.34
 2107.13 2142.79    2165    2165    2212    2212  2214.1 2231.93 2329.98 2383.46
 2445.86 2526.08 2602.37 2678.62 2773.93 2812.05 2878.77 2945.49 3155.18 3353.08
  352.73  351.98  351.62  351.62  350.53  349.97  349.49  348.82  348.03  348.13
  347.45  345.52  345.36  344.75  343.08  342.92  342.43  341.78  340.97  341.08
  339.99  340.08  338.65  338.54  337.92  336.17   335.2  335.33  334.09  331.74
  331.45  331.65   330.6  330.38  330.64  329.94  329.66  329.94  331.16  331.18
  333.65   333.8  333.36  336.08  336.08  333.36  333.66  333.84   333.9  334.54
  335.85   338.3  339.35   339.6  340.38   340.2  341.97   345.4  347.33  349.75
                                                                                
                                                                                
                                                                                
                                                                                
                          331.58  331.58
                                                                                
    7.16   44.08   58.85    88.4  125.32  132.71  184.41  213.95  228.72  250.87
  428.12  501.98  576.78  702.84  761.66  778.47   845.7  879.31  896.12  946.54
  954.95  996.97 1013.77 1030.58 1139.83 1291.09 1365.99 1420.87 1494.04 1512.33
 1521.48 1576.36 1638.95 1656.45 1743.95 1848.95 1883.95 1949.51 1967.34 2092.13
 2127.79    2150    2150    2197    2197  2199.1 2216.93 2314.98 2368.46 2430.86
 2511.08 2587.37 2663.62 2682.68 2758.93 2797.05 2863.77 2930.49 3140.18 3338.08
  352.49  351.62  351.62  350.53  349.97  349.49  348.82  348.03  348.13  347.45
  345.52  345.36  344.75  343.08  342.92  342.43  341.78  340.97  341.08  339.99
  340.08  338.65  338.54  337.92  336.17   335.2  335.33  334.09  331.74  331.45
  331.65   330.6  330.38  330.64  329.94  329.66  329.94  331.16  331.18  333.65
   333.8  333.36  336.08  336.08  333.36  333.66  333.84   333.9  334.54  335.85
   338.3  339.35   339.6  340.04  340.38   340.2  341.97   345.4  347.33  349.75
                                                                                
                                                                                
                                                                                
                                                                                
                  331.58  331.58
                                                                                
BR Coef=-1 , 0 , 0 ,, 0 ,,,0.8,-1,,0,
WSPro=,,,, 1 ,,,, 0 ,,,, 0 ,,,,-1 ,-1 ,-1 , 0 , 0 , 0 , 0 , 0
BC Design=,, 0 ,, 0 ,,,,,,
BC Use User HTab Curves=0
BC User HTab FreeFlow(D)= 0

Type RM Length L Ch R = 1 ,54231   ,659.04,907.24,705.12
XS GIS Cut Line= 6
1593372.79257314739232.865946531 1592788.1871444 739029.74033235
1592182.73035225738626.8403153421591963.65315931738427.456906065
1591390.15973201737687.0512130111590870.87950431737112.432692289
#Sta/Elev= 30
       0  353.71  222.32  349.44  244.55  350.26  274.19  348.29  385.35  345.87
  820.69   345.3 1005.67  342.24 1190.65  334.15 1266.32  332.77 1365.08  334.08
  1440.8  331.15 1620.63  332.39    1908  328.63 1969.98  329.83 2076.23  328.72
 2111.64  330.83 2136.11  329.83 2152.07  322.55 2195.49  322.55 2200.19  328.19
 2209.04  328.55 2253.31     329 2386.13   334.1 2412.69  333.78 2456.96  339.44
 2501.23  341.44 2536.65   340.2 2663.82  341.67 3144.99  355.06 3353.39  357.63
#Mann= 3 , 0 , 0
       0      .1       0 2136.11    .045       0 2209.04      .1       0
#XS Ineff= 2 , 0
                         2219.03          333.33
Permanent Ineff=
       F       F
Bank Sta=2136.11,2209.04
XS Rating Curve= 0 ,0
Exp/Cntr=0.5,0.3

Type RM Length L Ch R = 1 ,53324   ,2433.89,3126.74,2378.14
XS GIS Cut Line= 4
1594964.04213741738530.6567164211592536.30090715738129.413072616
1592204.63412671737665.0795803371590906.39558797736821.698339492
#Sta/Elev= 30
       0  348.42  120.61  348.15  297.99  355.51  581.79  359.97  645.64  359.85
  674.02  356.99  723.69  360.17   993.3  357.22 1305.47   358.6 1525.42  354.42
  1688.6  346.05  1830.5  335.46 2014.97  329.84 2627.21  328.69 2658.53  323.44
 2675.74  323.84 2700.02  328.34 2770.36   327.1 3039.65   328.3 3081.38  330.45
 3131.47  335.68 3239.98   337.8 3390.24  343.79 3649.01  356.95 3715.79  358.45
 3740.83     361 3957.86  361.02 4099.77  365.93 4233.32  367.87 4579.42   365.1
#Mann= 3 , 0 , 0
       0      .1       0 2627.21    .045       0 2700.02      .1       0
Bank Sta=2627.21,2700.02
XS Rating Curve= 0 ,0
Exp/Cntr=0.3,0.1

Type RM Length L Ch R = 1 ,50197   ,1118.44,1599.73,1550.27
XS GIS Cut Line= 4
1595661.29557572737576.5204323981594354.03363219736868.701605543
1593208.07649042 736162.570186631591701.58629233 735636.15457727
#Sta/Elev= 30
       0   360.4  326.37  360.96   780.1  344.55  931.35  345.33 1225.87  352.82
 1416.92  352.93 1511.25   351.2 1544.14  348.31 1560.58  349.34 1749.69  348.28
 1782.58  346.28 2021.02  341.99  2160.8  337.39 2374.58  332.98  2530.8  326.93
 2719.91   324.9 2951.26  325.33 2980.92  323.95 3040.24  325.59 3136.64  324.76
 3188.54  321.19  3218.2  324.44 3233.03  325.65 3336.84  323.78 3381.33  324.56
 3448.07  332.62 3729.84  344.37 3959.71   348.8 4226.65  357.02 4428.43  358.26
#Mann= 3 , 0 , 0
       0      .1       0 3136.64    .045       0  3218.2      .1       0
Bank Sta=3136.64,3218.2
XS Rating Curve= 0 ,0
Exp/Cntr=0.3,0.1