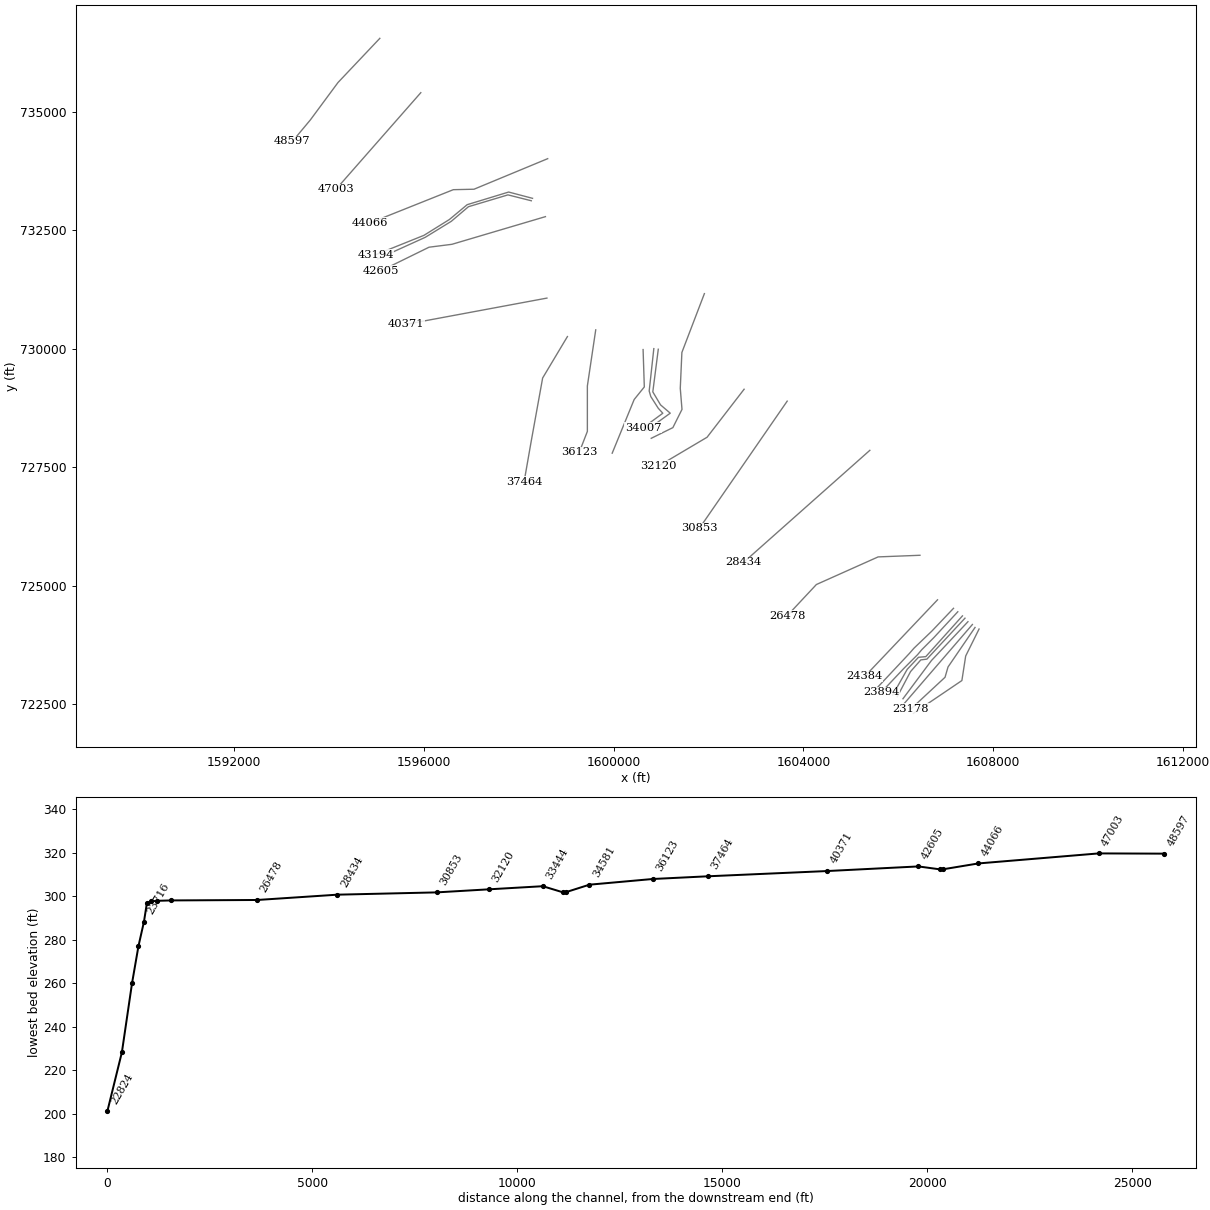
HEC-RAS study NortheastCreek.prj: Northeast Creek

--- NortheastCreek.g04 (geometry) --- (continued)

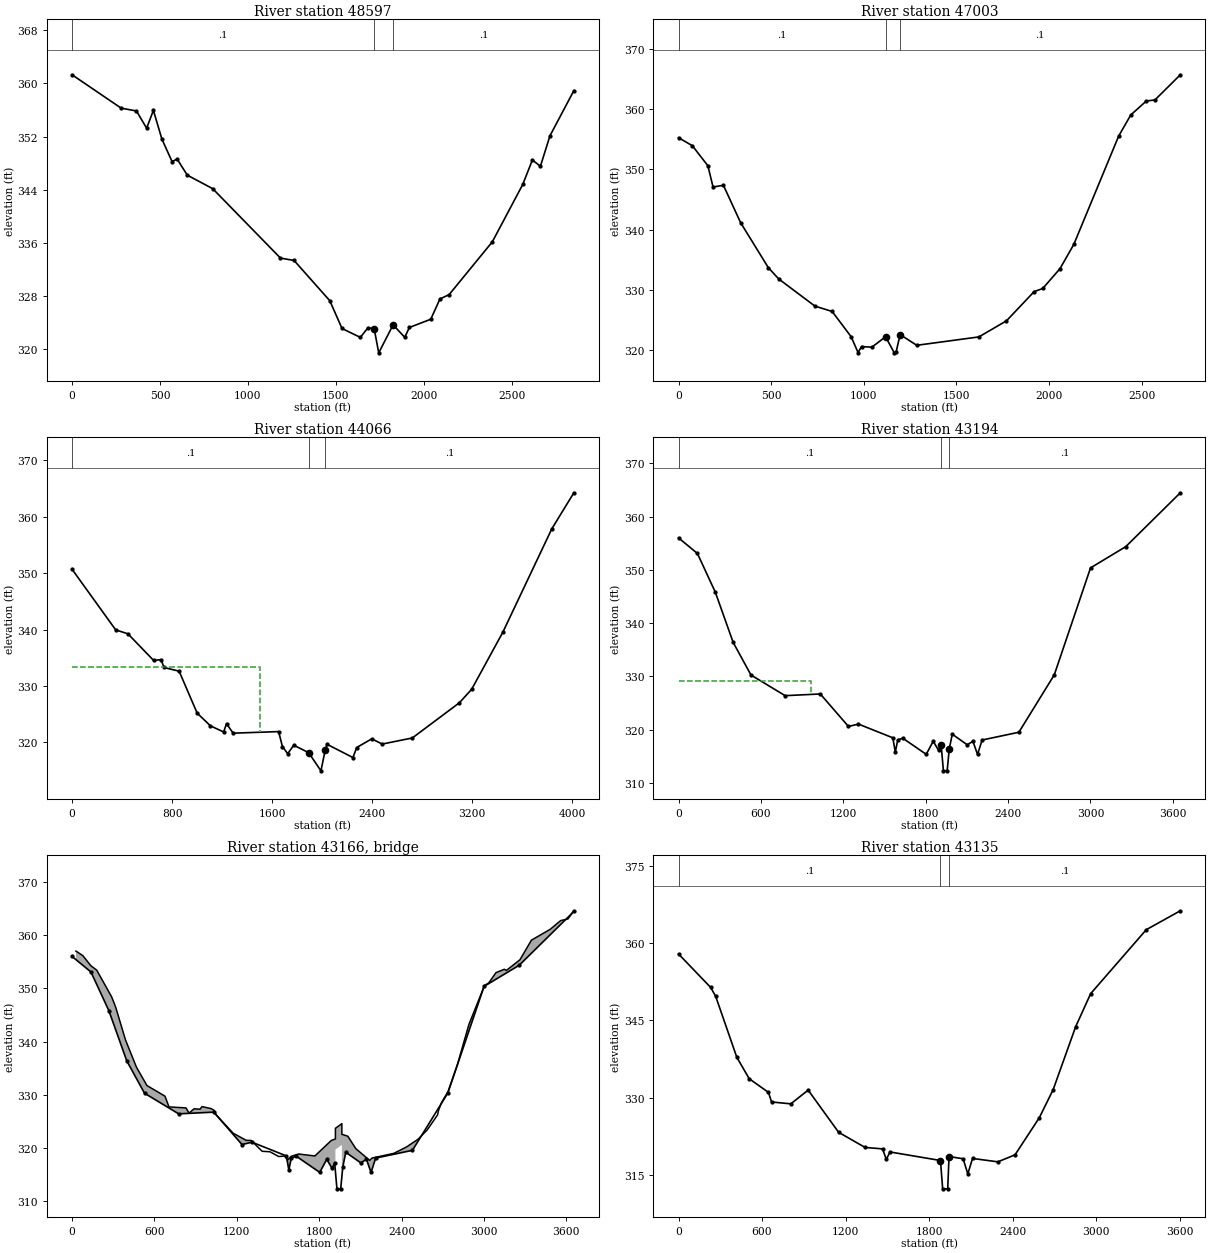
Type RM Length L Ch R = 1 ,48597   ,1464.1,1594.43,1413.33
XS GIS Cut Line= 4
1595071.25873187736544.4480095061594189.07950978735612.592676178
1593606.66992569734824.6267681421593227.68025987734370.527983144
#Sta/Elev= 30
       0  361.28  279.54  356.26  366.29  355.84  424.13  353.25  462.68  355.93
  510.88  351.62  568.72  348.23  597.63  348.61  655.47  346.19  800.06  344.16
 1185.63  333.72 1262.74  333.37 1465.99  327.32 1535.63  323.14 1640.09   321.8
 1683.61  323.27 1718.71  323.08 1744.54  319.48 1826.32  323.69 1892.52  321.81
 1918.63  323.29  2040.5  324.53 2092.72  327.58 2144.95  328.23 2390.69  336.17
 2563.93   344.8 2618.63  348.47 2664.22  347.53 2718.93  352.13 2854.52   358.9
#Mann= 3 , 0 , 0
       0      .1       0 1718.71    .045       0 1826.32      .1       0
Bank Sta=1718.71,1826.32
XS Rating Curve= 0 ,0
Exp/Cntr=0.3,0.1

Type RM Length L Ch R = 1 ,47003   ,2447.08,2936.42,1703.3
XS GIS Cut Line= 2
 1595935.1661339735398.625583664   1594148.44977733363.692548782
#Sta/Elev= 30
       0  355.26   74.52  353.93  158.36  350.61  186.31  347.08   242.2  347.37
  335.35  341.15   484.4  333.72  540.29  331.85  735.91  327.34  829.06  326.45
  931.53  322.26  968.79  319.64  987.42  320.63 1043.31  320.53 1117.06  322.25
 1164.41  319.59 1173.73  319.67 1195.86322.6175 1285.51  320.84 1620.86  322.23
 1769.91   324.9 1918.95  329.74 1965.53  330.26 2058.68  333.55 2133.21  337.57
 2375.41  355.54 2440.62  359.03 2524.46  361.34 2571.03  361.52 2708.01  365.69
#Mann= 3 , 0 , 0
       0      .1       0 1117.06    .045       0 1195.86      .1       0
Bank Sta=1117.06,1195.86
XS Rating Curve= 0 ,0
Exp/Cntr=0.3,0.1

Type RM Length L Ch R = 1 ,44066   ,294.99,872.13,633.31
XS GIS Cut Line= 4
1598610.54108432734007.2688026731597056.44531444733362.887630463
1596620.54040152733353.4114360961594860.56349947732650.868646652
#Sta/Elev= 30
       0  350.67  348.58  339.95  447.09  339.24   651.7  334.54  712.32  334.66
  735.05  333.28   856.3  332.63 1000.28  325.21 1106.37  322.95 1212.46  321.86
 1235.19  323.34 1288.24  321.65 1651.98  321.93 1682.39  319.29  1724.4  318.02
 1773.41  319.51 1892.44   318.2 1990.47  314.98 2025.48  318.75 2039.48  319.68
 2246.53  317.33 2276.68  319.11 2397.28  320.65 2480.19  319.72 2721.37   320.8
 3098.23  327.04 3196.21  329.43 3444.94  339.51 3836.86  357.83 4013.42  364.22
#Mann= 3 , 0 , 0
       0      .1       0 1892.44    .045       0 2025.48      .1       0
#XS Ineff= 2 , 0
         1503.38  333.37
Permanent Ineff=
       F       F
Bank Sta=1892.44,2025.48
XS Rating Curve= 0 ,0
Exp/Cntr=0.5,0.3

Type RM Length L Ch R = 1 ,43194   ,57.68,59.33,65.32
XS GIS Cut Line= 6
1598290.76899149733170.9887981411597787.61502653733303.604799286
1596912.92977564733037.0639726671596538.49577747732724.770084828
1596002.33815885732390.9661588221594982.48227507731981.203924209
#Sta/Elev= 30
       0  356.02  137.54  353.09  267.85  345.82  398.15  336.37  527.65  330.26
  776.46  326.38 1032.58   326.7 1237.48   320.6 1310.66  321.04 1560.78  318.46
 1578.79   315.8 1596.79  318.06 1632.81   318.4 1803.87  315.36 1855.02  317.82
 1893.51  316.11 1912.76   317.1 1929.05  312.29 1956.46  312.26 1971.71  316.37
 1993.65  319.14  2102.4  317.16 2144.23   317.8 2177.69  315.34 2211.16  318.05
 2478.86  319.51 2736.65  330.29 3000.68  350.38 3257.18  354.37  3654.7  364.49
#Mann= 3 , 0 , 0
       0      .1       0 1912.76    .045       0 1971.71      .1       0
#XS Ineff= 2 , 0
          963.96  329.21
Permanent Ineff=
       F       F
Bank Sta=1912.76,1971.71
XS Rating Curve= 0 ,0
Exp/Cntr=0.5,0.3

Type RM Length L Ch R = 3 ,43166   ,,,
BEGIN DESCRIPTION:
Crothers Road, CE041807PF-2, channel inverts adjusted based on bridge survey
END DESCRIPTION:
Bridge Culvert--1,0,-1,-1, 0
Deck Dist Width WeirC Skew NumUp NumDn MinLoCord MaxHiCord MaxSubmerge Is_Ogee
15,29,2.6,0, 60, 60, , , 0.98, 0, 0,0,,
      28   78.61  136.45  179.84  288.29  317.21  389.52  469.05  545.45   676.8
  705.99  830.04  851.93  888.41   932.2  946.79 1012.46 1034.35 1048.95    1173
 1267.86 1304.35 1384.62 1441.42 1504.97 1550.36 1568.52 1595.75 1650.22 1768.24
 1887.67    1918    1918    1965    1965 2008.34 2066.95 2167.42 2184.17 2343.25
 2435.35 2519.08 2586.15  2662.1  2669.7 2692.48 2738.06 2806.41 2889.96 3003.89
 3034.27 3087.44  3148.2 3163.39 3262.13 3345.67 3482.39 3558.34 3611.51 3654.23
  357.03  356.17  354.28  353.43  348.41   346.5  340.28  335.16  331.71  329.71
  327.69   327.5  326.52  327.33  327.26  327.75  327.37  327.05   326.2  322.74
   321.4  321.37  319.33  319.24  318.34  318.44  317.65  318.39  318.82  318.45
  321.36  321.66  323.66  324.53  322.53  322.17  319.82  317.62  318.05  318.94
  320.14  321.58  323.34  326.18  327.09  328.58  330.56  335.64  343.19  350.55
  351.02  352.97  353.61  353.39   355.4  359.09  361.13  362.77  363.08  364.62
                                                                                
                                                                                
                                                                                
                  319.66  320.53
                                                                                
                                                                                
       0   50.61  108.45  151.84  260.29  289.21  361.52  441.05  517.45   648.8
  677.99  802.04  823.93  860.41   904.2  918.79  984.46 1006.35 1020.95    1145
 1239.86 1276.35 1356.62 1413.42 1476.97 1522.36 1540.52 1567.75 1622.22 1740.24
 1859.67    1890    1890    1937    1937 1980.34 2038.95 2139.42 2156.17 2315.25
 2407.35 2491.08 2558.15  2634.1  2641.7 2664.48 2710.06 2778.41 2861.96 2975.89
 3006.27 3059.44  3120.2 3135.39 3234.13 3317.67 3454.39 3530.34 3583.51 3626.23
  357.03  356.17  354.28  353.43  348.41   346.5  340.28  335.16  331.71  329.71
  327.69   327.5  326.52  327.33  327.26  327.75  327.37  327.05   326.2  322.74
   321.4  321.37  319.33  319.24  318.34  318.44  317.65  318.39  318.82  318.45
  321.36  321.66  323.66  324.53  322.53  322.17  319.82  317.62  318.05  318.94
  320.14  321.58  323.34  326.18  327.09  328.58  330.56  335.64  343.19  350.55
  351.02  352.97  353.61  353.39   355.4  359.09  361.13  362.77  363.08  364.62
                                                                                
                                                                                
                                                                                
                  319.66  320.53
                                                                                
                                                                                
BR Coef=-1 , 0 , 0 ,, 0 ,,,0.8,0,,0,
WSPro=,,,, 1 ,,,, 0 ,,,, 0 ,,,,-1 ,-1 ,-1 , 0 , 0 , 0 , 0 , 0
BC Design=,, 0 ,, 0 ,,,,,,
BC Use User HTab Curves=0
BC User HTab FreeFlow(D)= 0

Type RM Length L Ch R = 1 ,43135   ,738.24,529.96,351.99
XS GIS Cut Line= 6
1598265.09018135 733119.631176011597772.91298491733243.745426193
1596940.19174199732994.4665890041596578.32918152732686.530016929
1596027.84541133732348.3844242251595021.00049216731891.328088775
#Sta/Elev= 30
       0  357.92  231.01  351.41  267.11  349.67  418.71  337.84  507.59  333.67
  646.42     331  668.34  329.14  807.17  328.78  931.39  331.45  1150.6  323.24
 1340.57   320.3 1466.13  320.02 1492.93  317.98 1519.72  319.42 1882.29  317.76
  1898.1  312.25 1934.29  312.25  1943.4  318.19 1946.83  318.52 2044.96   318.1
 2078.81  315.15 2112.66  318.16 2294.94   317.5 2418.22  318.87 2592.43  326.07
 2692.37  331.56  2853.8  343.78 2961.43   350.2 3361.18  362.64 3605.91  366.32
#Mann= 3 , 0 , 0
       0      .1       0 1882.29    .045       0 1946.83      .1       0
Bank Sta=1882.29,1946.83
XS Rating Curve= 0 ,0
Exp/Cntr=0.5,0.3

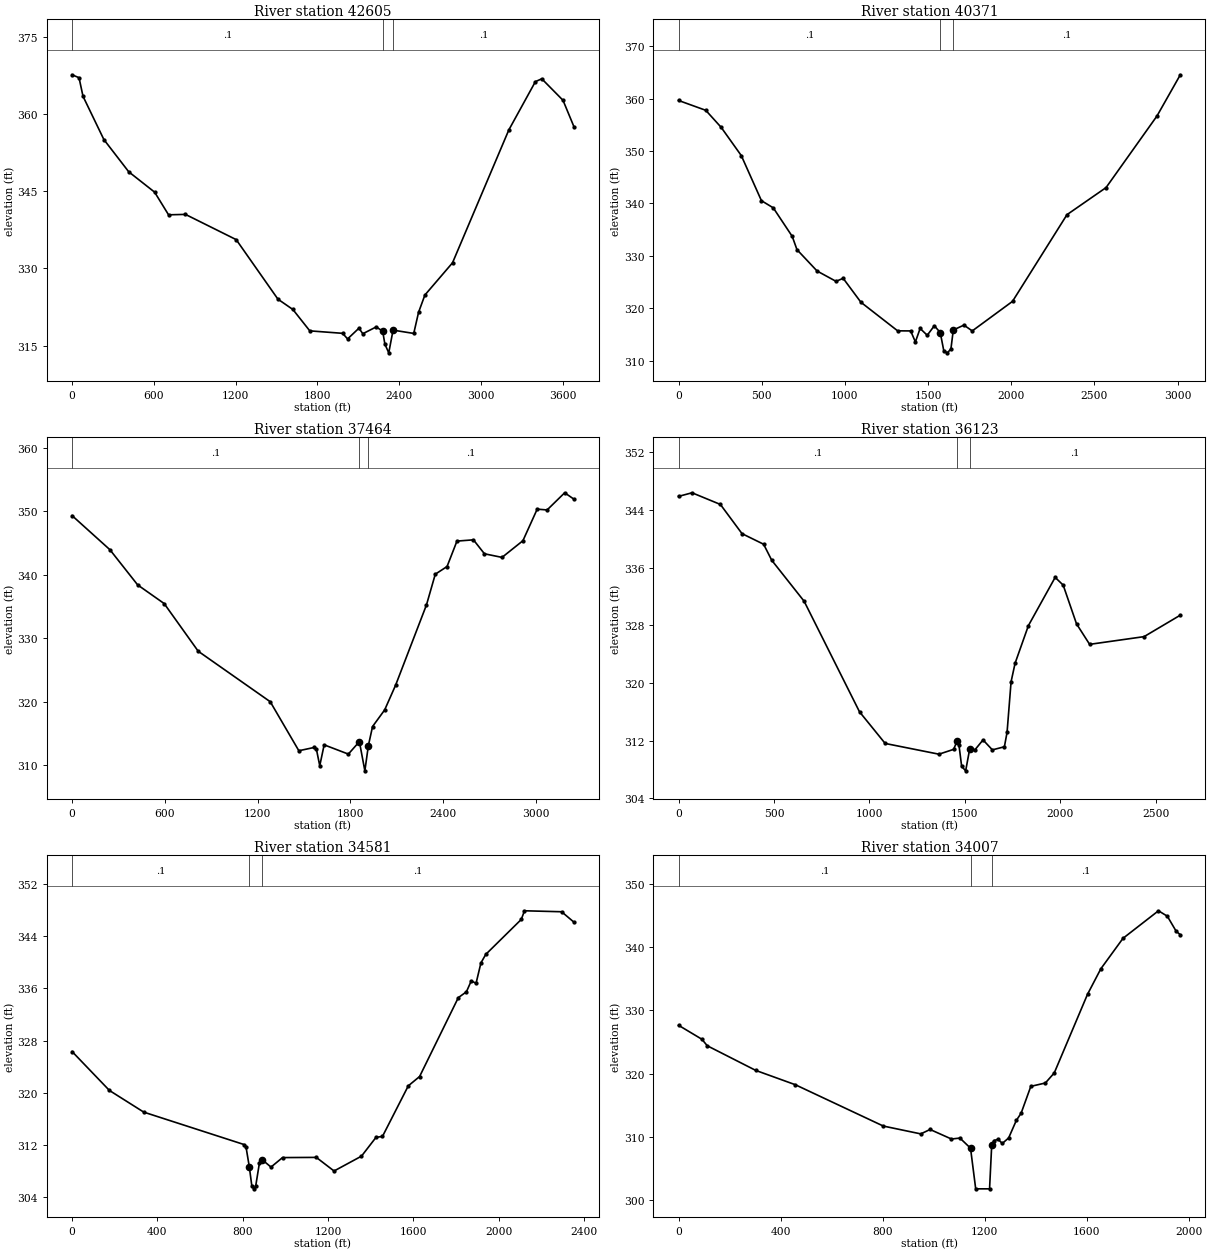
Type RM Length L Ch R = 1 ,42605   ,1531.91,2233.86,1596.27
XS GIS Cut Line= 4
1598563.16011621732784.8398132621596591.57082751732201.588073745
1596108.82594113732140.4586391751595085.39701846731638.220373183
#Sta/Elev= 30
       0  367.62    51.1  367.05    80.3  363.44   233.6  355.03  416.09  348.77
  605.89  344.82  708.09  340.42  832.19   340.5 1204.48   335.6 1511.08  324.03
 1620.58  322.03 1744.67  317.88 1985.57   317.4 2022.07  316.31 2105.45   318.4
 2133.67  317.32 2232.45  318.65 2279.57   317.8 2295.96  315.28 2324.18  313.61
  2355.8  318.02 2507.64  317.38 2542.66  321.46 2589.44  324.84 2792.17   331.1
 3205.43  356.91 3400.37  366.29 3447.15  366.84  3603.1  362.66 3682.66  357.57
#Mann= 3 , 0 , 0
       0      .1       0 2279.57    .045       0  2355.8      .1       0
Bank Sta=2279.57,2355.8
XS Rating Curve= 0 ,0
Exp/Cntr=0.3,0.1

Type RM Length L Ch R = 1 ,40371   ,2309.89,2906.96,3017.29
XS GIS Cut Line= 2
1598594.63491251731067.4662609251595628.73233224 730515.37184146
#Sta/Elev= 30
       0  359.63  163.77  357.75  256.33   354.5  377.37  349.11  498.42  340.51
  569.62  339.14  683.54   333.7  712.02  331.17  833.07  327.09  946.99  325.12
  989.71   325.7 1096.52  321.13 1317.24  315.68 1395.57  315.66 1424.05  313.56
 1452.53  316.13 1495.25  314.83 1537.97  316.65 1573.57  315.34 1594.93  311.85
 1616.29  311.48 1637.66  312.22  1651.9  315.84 1715.98  316.77 1765.82  315.66
 2007.91   321.3 2335.44  337.84 2570.42  343.01 2876.59  356.67 3016.86  364.53
#Mann= 3 , 0 , 0
       0      .1       0 1573.57    .045       0  1651.9      .1       0
Bank Sta=1573.57,1651.9
XS Rating Curve= 0 ,0
Exp/Cntr=0.3,0.1

Type RM Length L Ch R = 1 ,37464   ,1073.57,1341.27,1213.16
XS GIS Cut Line= 4
1599026.50499156730256.1374759821598504.04933549729382.523101822
 1598258.9991852728026.5789336261598112.69187468727191.113956362
#Sta/Elev= 30
       0  349.32  244.69  343.94  424.13  338.39  595.41  335.45  815.63  327.93
 1281.11  319.97 1466.06  312.24 1565.65  312.76 1579.88  312.45 1601.22  309.87
 1629.67  313.17 1786.17  311.71 1857.51  313.68 1892.87  309.07 1915.58  313.06
 1942.66  316.06 2020.91  318.68 2092.04   322.6 2291.21  335.24 2348.12  340.08
 2424.25  341.29 2488.21   345.3  2594.8   345.5 2665.87   343.3 2779.57  342.73
 2914.59  345.36 3006.98  350.34 3070.94  350.21 3184.64  352.92 3243.99  351.92
#Mann= 3 , 0 , 0
       0      .1       0 1857.51    .045       0 1915.58      .1       0
Bank Sta=1857.51,1915.58
XS Rating Curve= 0 ,0
Exp/Cntr=0.3,0.1

Type RM Length L Ch R = 1 ,36123   ,1234.27,1541.66,962.17
XS GIS Cut Line= 4
1599623.49924093  730397.67729571599447.13619044729214.118845001
1599447.13619044728256.5249138181599274.87627143727813.520642921
#Sta/Elev= 30
       0  345.91   70.77  346.41   219.4  344.79  332.63  340.74  445.87  339.27
  488.33  337.05  658.19  331.36  948.36  316.02 1082.82  311.63 1364.62  310.14
 1441.62  310.81 1460.18  312.01 1469.62  311.39 1483.62  308.45 1504.62  307.83
 1526.18  310.92 1553.62  310.76 1595.62  312.12 1644.62  310.74 1707.62  311.17
 1721.62  313.18 1742.62  320.19 1763.62  322.76 1833.62  327.99 1973.62  334.67
 2015.62   333.6 2085.62  328.22 2154.22  325.38 2439.62  326.45 2629.53  329.43
#Mann= 3 , 0 , 0
       0      .1       0 1460.18    .045       0 1526.18      .1       0
Bank Sta=1460.18,1526.18
XS Rating Curve= 0 ,0
Exp/Cntr=0.3,0.1

Type RM Length L Ch R = 1 ,34581   ,144.55,573.78,541.84
XS GIS Cut Line= 4
1600622.13595204729982.0623779591600647.83049396729194.096471816
1600433.70932201728928.5862198031599970.65651241727797.488840133
#Sta/Elev= 30
       0  326.31  175.09  320.33  336.18     317  806.37  312.02  815.36  311.63
  830.62  308.61  842.34   305.7  851.33  305.22  860.33  305.59  878.31  309.24
     892  309.67  932.27  308.56  986.22  310.02 1144.61  310.05 1227.81  307.96
 1356.39  310.24 1424.47  313.13 1454.72  313.27 1575.74  321.04 1628.69  322.47
 1810.22  334.59 1848.04  335.48 1870.73  337.15 1893.43   336.8 1916.12  339.92
 1938.81  341.23 2105.21   346.6 2120.34  347.93 2294.31  347.78 2351.69  346.19
#Mann= 3 , 0 , 0
       0      .1       0  830.62    .045       0     892      .1       0
Bank Sta=830.62,892
XS Rating Curve= 0 ,0
Exp/Cntr=0.5,0.3

Type RM Length L Ch R = 1 ,34007   ,84.34,82.39,101.38
XS GIS Cut Line= 6
 1600848.3784886730001.7956371611600750.60865405729108.448003799
1600784.18146138728991.7624359131600942.53412439728743.533937484
1601037.79902765728639.6597144311600625.79917149728336.346936896
#Sta/Elev= 30
       0  327.65   91.54  325.44  112.67  324.41   302.8  320.51  457.72  318.25
  802.77  311.71  949.67  310.47  986.09  311.17 1069.92  309.66 1103.13  309.81
 1144.65  308.21 1164.93  301.78 1219.26  301.78 1227.68  308.71 1235.98   309.4
 1252.59  309.62  1269.2  308.96  1294.1  309.83 1324.04  312.59 1343.03  313.75
 1381.03  317.99 1438.02  318.52 1472.87  320.11 1603.26  332.55 1655.41  336.58
 1742.33   341.4 1881.41  345.76 1916.18   344.9 1950.95  342.51 1967.09  341.97
#Mann= 3 , 0 , 0
       0      .1       0 1144.65    .045       0 1227.68      .1       0
Bank Sta=1144.65,1227.68
XS Rating Curve= 0 ,0
Exp/Cntr=0.5,0.3

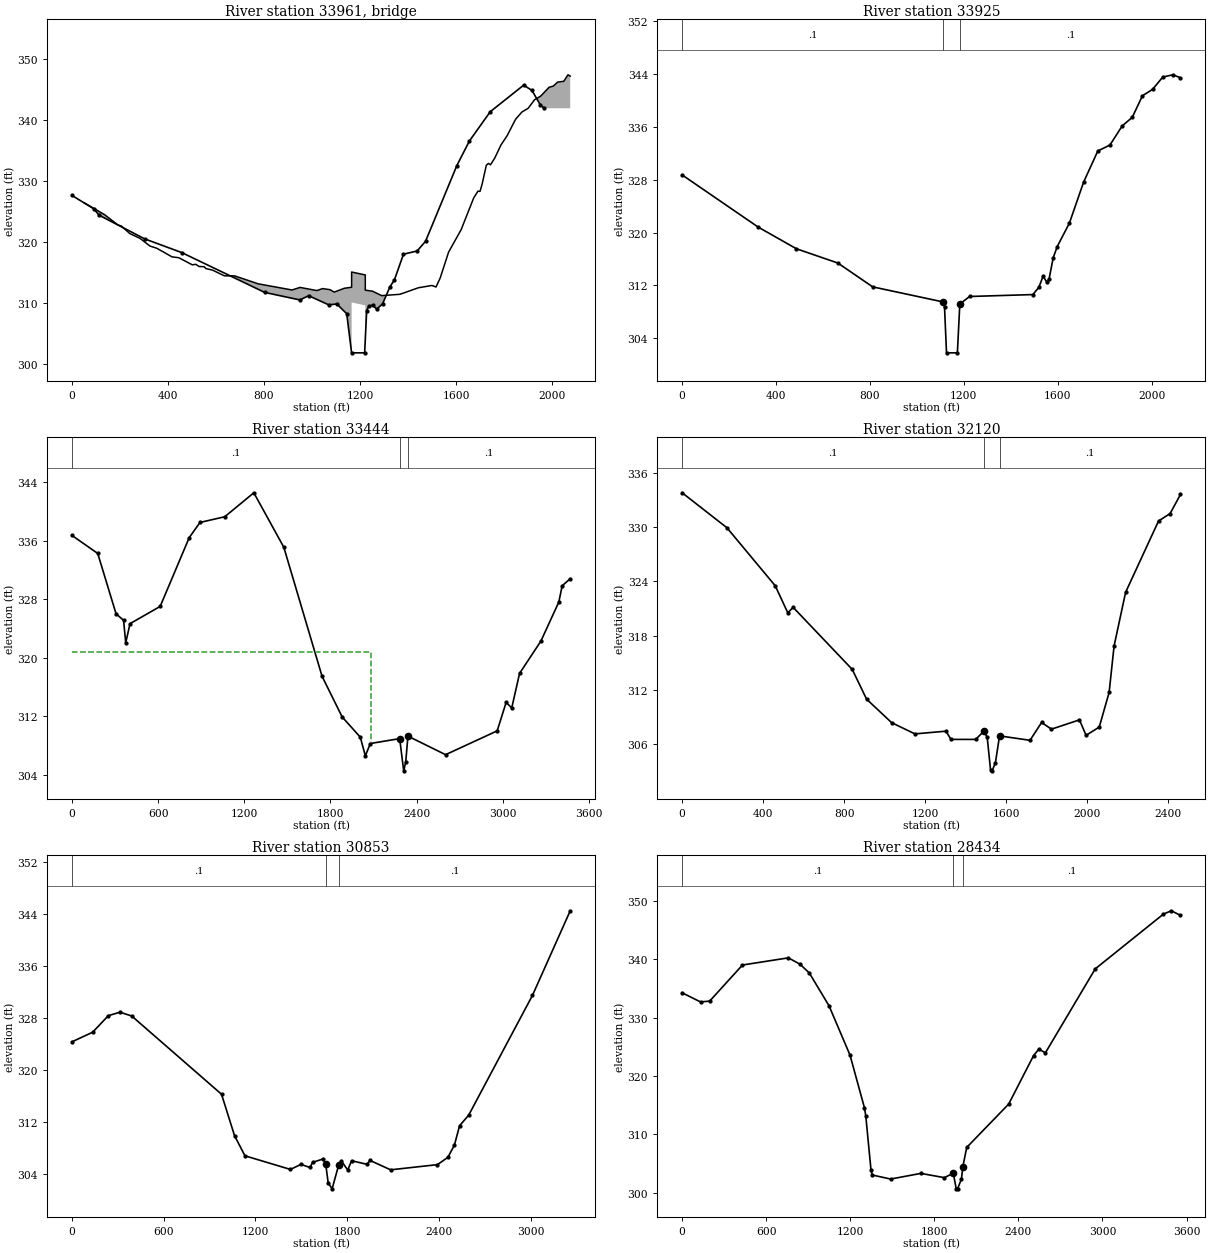
Type RM Length L Ch R = 3 ,33961   ,,,
BEGIN DESCRIPTION:
Kirk's Mill Lane, CE041807PF-1, channel inverts adjusted based on bridge survey
END DESCRIPTION:
Bridge Culvert--1,0,-1,-1, 0
Deck Dist Width WeirC Skew NumUp NumDn MinLoCord MaxHiCord MaxSubmerge Is_Ogee
35,32,2.6,0, 60, 60, , , 0.98, 0, 0,0,,
   51.11  135.56  191.86  205.94  241.13  283.35  325.58  353.73  417.07  445.22
  501.52  515.59  529.67  550.78  557.82  585.97  635.23  677.46  775.99  916.74
  950.48 1020.44 1043.76 1074.85 1092.53 1134.72    1165    1165    1222    1222
 1252.07 1290.23 1366.56 1442.89 1499.19 1516.63 1534.08 1568.96 1621.29 1673.62
 1691.06 1699.78  1708.5 1725.95 1734.67 1743.39 1760.83    1787 1813.16 1848.05
 1874.21 1900.38 1926.54 1952.71 1987.59 2005.03 2022.48 2048.64 2066.08 2075.49
  326.43   324.5  322.79  322.62  321.38   320.6  319.32  318.96  317.55  317.41
  316.24  316.33  315.97  315.93  315.63  315.37  314.43  314.43  313.12  312.11
  312.53  312.01  312.34  312.16  311.76  312.39  312.56  315.06  314.58  312.08
  311.91  311.18   311.4  312.47  312.85   312.6   314.1  318.33  322.03  327.25
  328.34  328.31   329.5  332.59  332.91  332.68  333.76  335.93  337.49  340.17
  341.35  341.97  343.35  343.98  345.42  345.61  346.26   346.4  347.47  347.25
                                                                                
                                                                                
                                                          310.06  309.58
                                                                                
                                                                                
                                                                                
    6.11   90.56  146.86  160.94  196.13  238.35  280.58  308.73  372.07  400.22
  456.52  470.59  484.67  505.78  512.82  540.97  590.23  632.46  730.99  871.74
  905.48  975.44  998.76 1029.85 1047.53 1089.72    1120    1120    1177    1177
 1207.07 1245.23 1321.56 1397.89 1454.19 1471.63 1489.08 1523.96 1576.29 1628.62
 1646.06 1654.78  1663.5 1680.95 1689.67 1698.39 1715.83    1742 1768.16 1803.05
 1829.21 1855.38 1881.54 1907.71 1942.59 1960.03 1977.48 2003.64 2021.08 2030.49
  326.43   324.5  322.79  322.62  321.38   320.6  319.32  318.96  317.55  317.41
  316.24  316.33  315.97  315.93  315.63  315.37  314.43  314.43  313.12  312.11
  312.53  312.01  312.34  312.16  311.76  312.39  312.56  315.06  314.58  312.08
  311.91  311.18   311.4  312.47  312.85   312.6   314.1  318.33  322.03  327.25
  328.34  328.31   329.5  332.59  332.91  332.68  333.76  335.93  337.49  340.17
  341.35  341.97  343.35  343.98  345.42  345.61  346.26   346.4  347.47  347.25
                                                                                
                                                                                
                                                          310.06  309.58
                                                                                
                                                                                
                                                                                
BR Coef=-1 , 0 , 0 ,, 0 ,,,0.8,0,,0,
WSPro=,,,, 1 ,,,, 0 ,,,, 0 ,,,,-1 ,-1 ,-1 , 0 , 0 , 0 , 0 , 0
BC Design=,, 0 ,, 0 ,,,,,,
BC Use User HTab Curves=0
BC User HTab FreeFlow(D)= 0

Type RM Length L Ch R = 1 ,33925   ,575.17,480.92,454.37
XS GIS Cut Line= 5
1600942.53412439729988.9562320861600826.97947885729090.197875991
1600989.61194421728816.290565521 1601194.5106294728640.923517659
1600685.19792379 728271.89297165
#Sta/Elev= 30
       0  328.73  324.65  320.81  486.98  317.54  663.42  315.38  811.63  311.77
 1109.68   309.5 1117.82  308.77 1126.35  301.77 1172.67  301.77 1182.95  309.09
 1185.26  309.22 1224.71  310.31  1494.4   310.6 1520.34  311.73 1537.63  313.37
 1554.91  312.44 1563.56  312.98 1580.85  316.16 1598.14  317.88    1650  321.43
 1710.51  327.64 1771.02  332.36 1822.89  333.27 1874.76  336.15 1917.98  337.47
  1961.2  340.73 2004.42   341.7 2047.65  343.56 2090.87  343.91 2123.36  343.46
#Mann= 3 , 0 , 0
       0      .1       0 1109.68    .045       0 1185.26      .1       0
Bank Sta=1109.68,1185.26
XS Rating Curve= 0 ,0
Exp/Cntr=0.5,0.3

Type RM Length L Ch R = 1 ,33444   ,1162.55,1323.58,749.82
XS GIS Cut Line= 6
1601914.55799103731161.7887998221601440.01214129729921.298269168
1601406.01823236729164.9338112181601442.21606439 728720.54312177
1601250.11797197728336.346936896 1600793.8850024728111.389960215
#Sta/Elev= 30
       0  336.74  179.87  334.27  307.28  326.02  359.75  325.11  374.74  322.05
  404.71  324.66  614.57  327.02  816.92  336.44  891.87  338.51 1064.25  339.29
 1266.61  342.57 1475.31  335.12 1741.58  317.46 1881.72  311.89 2007.85  309.13
 2042.88  306.57 2077.92  308.26 2281.94  308.93 2310.03  304.52 2324.08  305.71
  2339.4  309.27 2601.59  306.73 2960.69  309.99 3023.13  313.88 3062.15  313.13
 3116.79  317.86 3265.08  322.27 3389.95  327.62 3413.37  329.85 3469.37  330.81
#Mann= 3 , 0 , 0
       0      .1       0 2281.94    .045       0  2339.4      .1       0
#XS Ineff= 2 , 0
         2081.08  320.79
Permanent Ineff=
       F       F
Bank Sta=2281.94,2339.4
XS Rating Curve= 0 ,0
Exp/Cntr=0.3,0.1

Type RM Length L Ch R = 1 ,32120   ,974.91,1267.55,1207.47
XS GIS Cut Line= 3
1602752.03735448729145.8210884031601971.03101888728133.405468196
1600953.79437187 727530.77712281
#Sta/Elev= 30
       0  333.78  221.02  329.92  459.72  323.51  521.61  320.53  548.13  321.13
  839.88  314.28   910.6     311 1034.38   308.4 1149.31  307.16 1303.06  307.46
 1327.47  306.55 1449.51  306.55 1489.89  307.46 1506.47  306.79 1522.74  303.21
 1530.87  303.08 1547.15     304 1567.41  306.94    1718  306.45 1774.96  308.42
 1823.77  307.68 1962.09  308.71 1994.63     307 2059.72  307.91 2108.54  311.74
 2132.95  316.86  2189.9  322.79 2352.63  330.67 2409.58  331.48    2461   333.6
#Mann= 3 , 0 , 0
       0      .1       0 1489.89    .045       0 1567.41      .1       0
Bank Sta=1489.89,1567.41
XS Rating Curve= 0 ,0
Exp/Cntr=0.3,0.1

Type RM Length L Ch R = 1 ,30853   ,1673.49,2418.51,1745.08
XS GIS Cut Line= 2
1603660.54949002728894.9208679351601809.20122151726213.657859817
#Sta/Elev= 30
       0  324.33   136.1  325.82  238.18  328.37  314.74   328.9   391.3  328.31
  978.25  316.26 1063.32  309.88 1131.37  306.77  1429.1  304.67 1497.15  305.45
  1556.7  304.97 1573.71  305.76 1641.76  306.28 1659.47   305.5 1675.79   302.6
 1701.31  301.68 1743.84   305.3 1760.86  306.02 1803.39  304.57 1828.91  306.01
 1930.99  305.45    1948  306.07 2084.11  304.61 2390.34  305.41  2458.4  306.54
 2500.93  308.41 2534.96  311.41  2594.5  313.04 3011.33  331.49 3258.34  344.53
#Mann= 3 , 0 , 0
       0      .1       0 1659.47    .045       0 1743.84      .1       0
Bank Sta=1659.47,1743.84
XS Rating Curve= 0 ,0
Exp/Cntr=0.3,0.1

Type RM Length L Ch R = 1 ,28434   ,1687.13,1956.85,1535.06
XS GIS Cut Line= 2
1605402.94345859727857.6149845271602742.79202466725496.652101547
#Sta/Elev= 30
       0  334.28  131.03  332.71  196.55  332.86  430.53  339.05  758.11  340.28
  842.34  339.17  907.86  337.67 1048.25  332.05    1198  323.58 1300.95  314.55
 1310.31  313.21 1347.75  303.86 1357.11     303 1488.14  302.31 1703.41  303.28
 1871.87  302.55 1934.88  303.32 1956.11  300.64 1965.47  300.63 1993.55  302.32
 2002.91  304.39 2030.98  307.74 2330.48  315.18 2508.31  323.51 2545.75  324.61
 2592.55  323.98  2948.2  338.39 3434.89  347.79 3491.05  348.36 3556.76  347.57
#Mann= 3 , 0 , 0
       0      .1       0 1934.88    .045       0 2002.91      .1       0
Bank Sta=1934.88,2002.91
XS Rating Curve= 0 ,0
Exp/Cntr=0.3,0.1

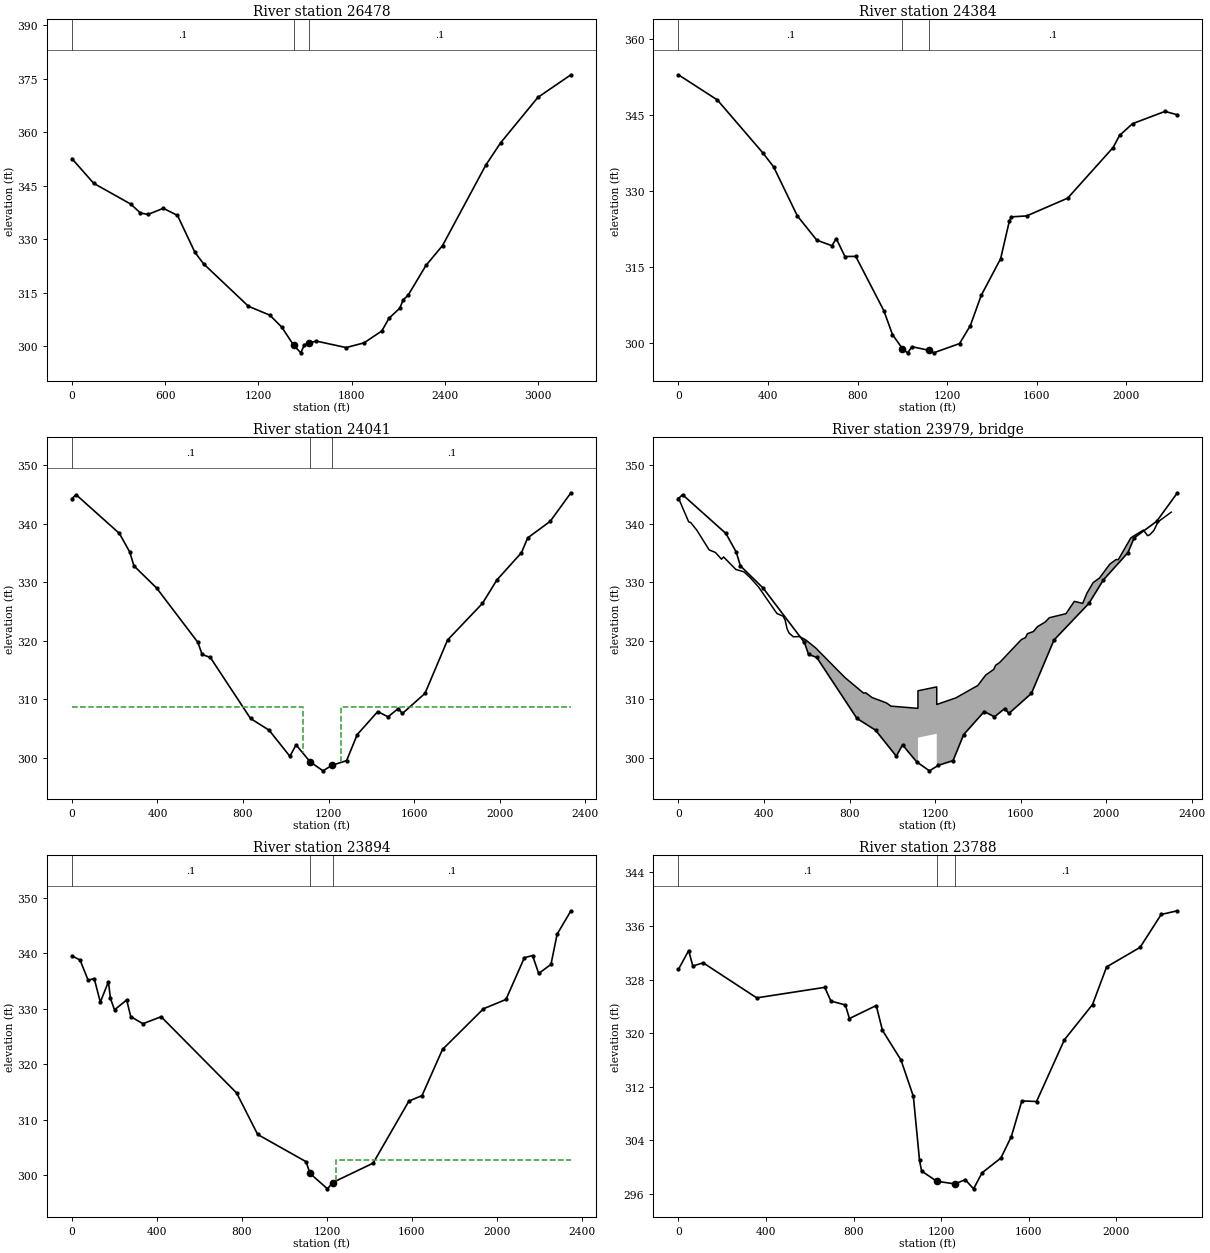
Type RM Length L Ch R = 1 ,26478   ,1811.74,2093.36,2009.49
XS GIS Cut Line= 4
1606459.93554117725644.8239517511605577.75632098725610.564563781
1604275.89960481725028.1549797361603659.23063284724368.661775604
#Sta/Elev= 30
       0  352.62  140.11   345.7  378.29  339.89  441.33  337.37  490.37  336.99
  588.44   338.7  679.51   336.7   791.6  326.36  847.64  323.13 1135.91  311.25
 1273.94  308.75 1350.63  305.39 1428.35  300.26 1473.32  298.19 1496.33  300.45
 1522.78  300.93 1573.02  301.48 1764.73  299.67 1879.76  300.98 1994.79  304.32
  2040.8  307.88 2109.81  310.68 2132.82  313.08 2163.49   314.3 2278.52  322.67
 2385.71  328.27 2663.63  350.78 2759.46  357.06 2999.05  369.78 3211.93  376.12
#Mann= 3 , 0 , 0
       0      .1       0 1428.35    .045       0 1522.78      .1       0
Bank Sta=1428.35,1522.78
XS Rating Curve= 0 ,0
Exp/Cntr=0.3,0.1

Type RM Length L Ch R = 1 ,24384   ,348.78,342.97,348.99
XS GIS Cut Line= 2
1606829.98493578724705.664962783 1605296.2121239723090.508289367
#Sta/Elev= 30
       0  352.87  173.76  347.91  376.48  337.48  424.75  334.72  530.93  325.02
  617.81  320.23  685.39  319.13  704.69  320.54  743.31     317  791.57  317.03
  917.07  306.31  955.68  301.59 1000.09  298.81 1023.25  297.99 1042.56   299.2
 1119.48  298.48 1139.09  297.99 1254.93  299.82  1303.2  303.37 1351.46  309.31
 1438.34  316.57 1476.96  323.94 1486.61  324.83 1554.18  325.01  1737.6  328.52
 1940.32  338.51 1969.28  340.91  2027.2  343.22    2172  345.64 2227.37  344.97
#Mann= 3 , 0 , 0
       0      .1       0 1000.09    .045       0 1119.48      .1       0
Bank Sta=1000.09,1119.48
XS Rating Curve= 0 ,0
Exp/Cntr=0.5,0.3

Type RM Length L Ch R = 1 ,24041   ,137.66,147.49,143.07
XS GIS Cut Line= 5
1607167.10320061724526.3145379281606712.00769812724047.527606979
1606335.35005572723687.495895416 1606234.9719639723573.111560836
1605551.30991751722844.540592209
#Sta/Elev= 30
       0  344.28   19.32  344.96  222.13  338.33  270.42  335.16  289.73  332.81
  395.96  329.02  589.12  319.73  608.43  317.69  647.06  317.16  834.87  306.75
  922.02  304.74 1018.86   300.3 1047.91  302.24 1113.96  299.34 1173.79  297.81
 1215.91  298.76 1284.06  299.55  1333.8     304 1429.79  307.93 1477.79  307.03
 1525.78  308.45 1544.98   307.6 1650.57  311.03 1756.17  320.15 1919.35   326.4
 1986.55  330.39 2101.74  335.06 2130.54  337.57 2236.13  340.41 2332.91  345.28
#Mann= 3 , 0 , 0
       0      .1       0 1113.96    .045       0 1215.91      .1       0
#XS Ineff= 2 , 0
         1078.27  308.65 1258.45          308.65
Permanent Ineff=
       F       F
Bank Sta=1113.96,1215.91
XS Rating Curve= 0 ,0
Exp/Cntr=0.5,0.3

Type RM Length L Ch R = 3 ,23979   ,,,
BEGIN DESCRIPTION:
North East Road and Covered Bridge (just downstream of road), CE041307PF-4 and CE041307FS-4, channel invert elevations not adjusted
END DESCRIPTION:
Bridge Culvert--1,0,-1,-1, 0
Deck Dist Width WeirC Skew NumUp NumDn MinLoCord MaxHiCord MaxSubmerge Is_Ogee
40,80,2.6,0, 60, 60, , , 0.98, 0, 0,0,,
       0   47.98   57.58   86.37  143.95  172.74  201.53  211.13  268.71  307.09
  335.88  374.27  460.64  489.43  499.03  508.63  518.22  537.42  566.21     595
  641.57  778.26  866.12  875.89  905.17  973.52  993.04 1119.96 1119.96 1207.83
 1207.83 1297.45 1399.61 1436.76 1473.91 1483.19 1501.77 1603.93  1622.5 1631.79
 1659.65 1678.22 1715.37 1733.95 1811.82 1850.97 1890.12  1909.7 1939.06 1968.42
 2017.36 2046.72 2056.51 2115.23 2173.96 2193.54 2203.32  2222.9 2242.47 2304.06
  344.41  340.32   340.2  338.88  335.52   335.1  333.94  334.33  332.19  331.77
  330.78  329.22  324.67  324.21  323.54     322  321.29   320.7  320.73  320.17
   318.8  313.75  311.07  311.14  310.33  309.39  308.86  308.48  311.48  312.14
  309.14  310.27  312.38  314.16  315.12  315.84   316.3  320.24  320.55  321.23
  321.59  322.41  323.23  323.95  324.64  326.74   326.4  328.12  329.95  330.72
  333.12  333.89  333.85  337.59  338.92  337.96   338.1  338.85  340.32  341.97
                                                                                
                                                                                
                                                                  303.48  304.14
                                                                                
                                                                                
                                                                                
      10   57.98   67.58   96.37  153.95  182.74  211.53  221.13  278.71  317.09
  345.88  384.27  470.64  499.43  509.03  518.63  528.22  547.42  576.21     605
  651.57  788.26  876.12  885.89  915.17  983.52 1003.04 1129.96 1129.96 1217.83
 1217.83 1307.45 1409.61 1446.76 1483.91 1493.19 1511.77 1613.93  1632.5 1641.79
 1669.65 1688.22 1725.37 1743.95 1821.82 1860.97 1900.12  1919.7 1949.06 1978.42
 2027.36 2056.72 2066.51 2125.23 2183.96 2203.54 2213.32  2232.9 2252.47 2314.06
  344.41  340.32   340.2  338.88  335.52   335.1  333.94  334.33  332.19  331.77
  330.78  329.22  324.67  324.21  323.54     322  321.29   320.7  320.73  320.17
   318.8  313.75  311.07  311.14  310.33  309.39  308.86  308.48  311.48  312.14
  309.14  310.27  312.38  314.16  315.12  315.84   316.3  320.24  320.55  321.23
  321.59  322.41  323.23  323.95  324.64  326.74   326.4  328.12  329.95  330.72
  333.12  333.89  333.85  337.59  338.92  337.96   338.1  338.85  340.32  341.97
                                                                                
                                                                                
                                                                  303.48  304.14
                                                                                
                                                                                
                                                                                
BR Coef=-1 , 0 , 0 ,, 0 ,,,0.8,0,,0,
WSPro=,,,, 1 ,,,, 0 ,,,, 0 ,,,,-1 ,-1 ,-1 , 0 , 0 , 0 , 0 , 0
BC Design=,, 0 ,, 0 ,,,,,,
BC Use User HTab Curves=0
BC User HTab FreeFlow(D)= 0

Type RM Length L Ch R = 1 ,23894   ,160.94,105.95,54.14
XS GIS Cut Line= 6
1607257.52419478724453.7460327451606750.86866193723906.927070618
1606498.75624853723654.8146572111606410.05002977723549.767818466
1606121.53325844723260.8762378691605640.21007311722751.609118551
#Sta/Elev= 30
       0  339.55   38.17   338.8   76.34  335.15  104.97  335.46   133.6   331.2
  171.77  334.89  181.31  331.88   200.4  329.82  257.66  331.61  276.74   328.6
     334  327.32  419.89  328.58  775.16  314.84  874.15  307.37    1102  302.46
 1120.32  300.35 1202.78  297.57 1226.86   298.7 1417.57   302.2 1585.75  313.37
 1647.78  314.38  1744.1  322.69 1936.73  330.01 2042.68  331.69 2129.37  339.21
 2167.89  339.61 2196.79  336.37 2254.58  338.01 2283.48  343.44 2348.51  347.67
#Mann= 3 , 0 , 0
       0      .1       0 1120.32    .045       0 1226.86      .1       0
#XS Ineff= 2 , 0
                         1241.55          302.81
Permanent Ineff=
       F       F
Bank Sta=1120.32,1226.86
XS Rating Curve= 0 ,0
Exp/Cntr=0.5,0.3

Type RM Length L Ch R = 1 ,23788   ,62.58,71.58,74.62
XS GIS Cut Line= 5
1607355.47157863724366.7987861931606582.79372029 723507.74908258
1606428.72502333723493.7428379361606190.61885454723239.296049133
  1605884.815836722698.888423949
#Sta/Elev= 30
       0   329.5   47.07  332.32    65.9  330.01  112.98  330.49  357.77  325.26
  668.46  326.83  696.71  324.79  762.61   324.2  781.44  322.18  903.84  324.12
  932.08  320.42 1016.82  315.99 1073.31  310.58 1101.55  301.02 1110.97  299.44
 1179.66  297.92 1263.55  297.51 1310.12  298.15 1348.47  296.78 1386.82  299.16
  1473.1  301.37 1521.04  304.58 1568.97   309.9 1636.08   309.8 1763.16     319
 1891.85  324.27  1956.2  329.88 2109.02  332.79 2205.53   337.7 2279.54  338.25
#Mann= 3 , 0 , 0
       0      .1       0 1179.66    .045       0 1263.55      .1       0
Bank Sta=1179.66,1263.55
XS Rating Curve= 0 ,0
Exp/Cntr=0.5,0.3

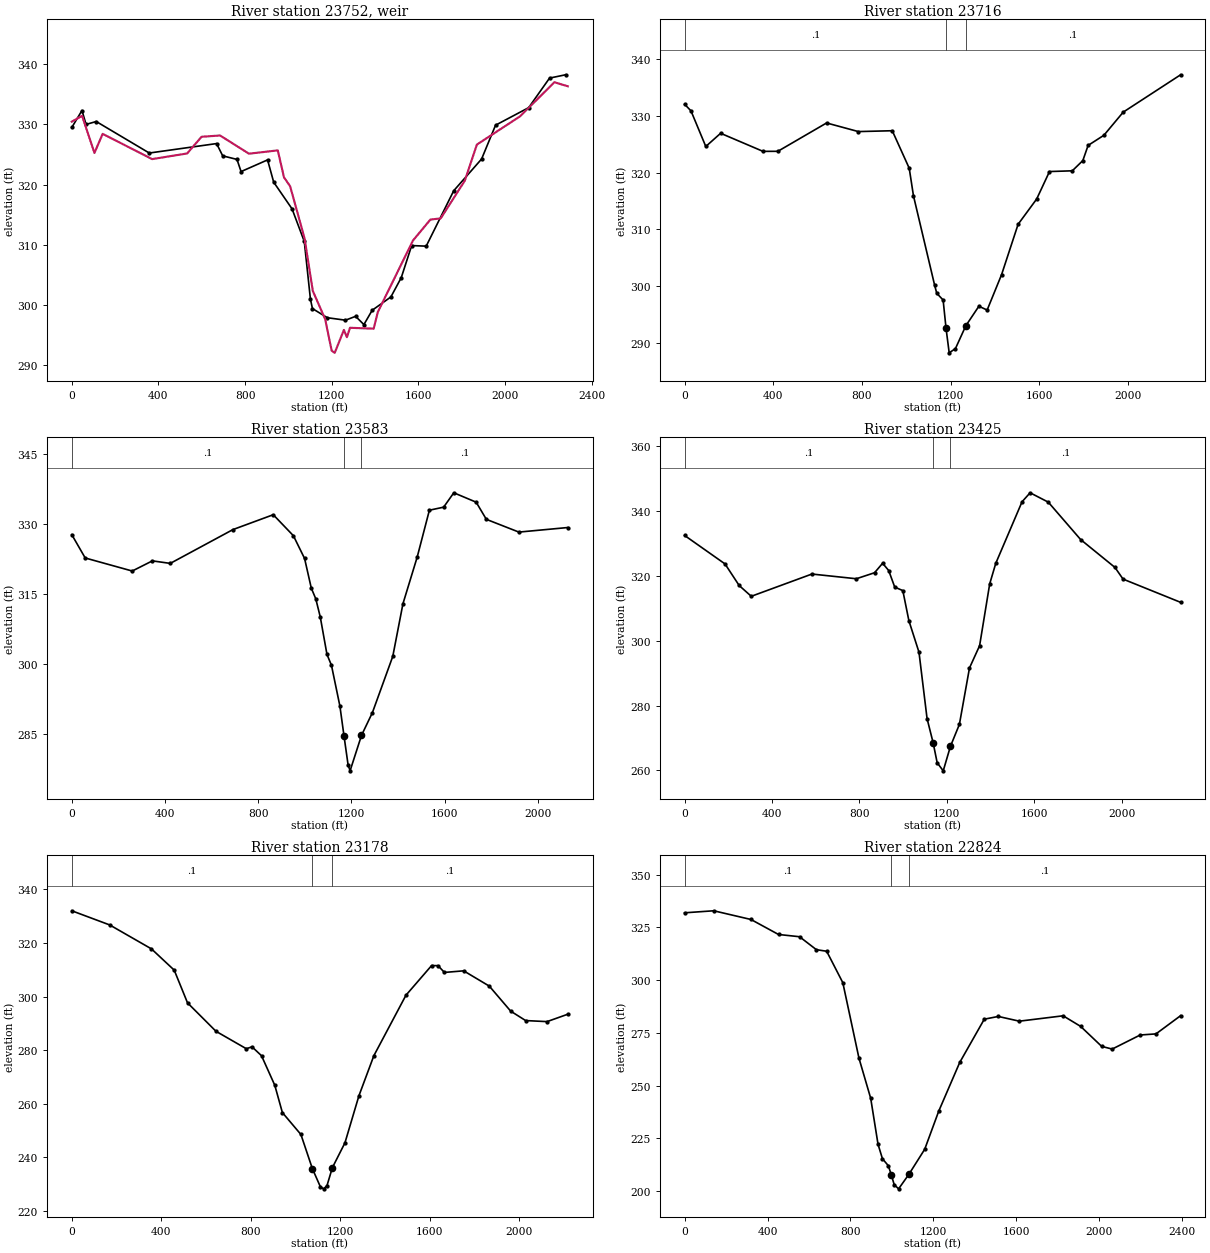
Type RM Length L Ch R = 5 ,23752   ,,,
IW Pilot Flow=0
#Inline Weir SE= 30
       0  330.47   47.55  331.43  104.61  325.27  142.65  328.44  370.89  324.25
  532.56  325.19  599.13  327.96  684.72  328.17  817.86  325.15  950.99   325.7
  979.52  321.23 1008.05  319.74 1074.62  311.09 1112.66  302.37 1169.72  297.67
 1199.77  292.44 1213.85  292.09 1256.11  295.89  1270.2  294.69 1284.28  296.25
 1393.59   296.1 1412.73  298.86  1575.4  310.76 1655.29  314.21    1703  314.41
 1814.34  320.67 1870.01  326.66 2068.83  331.34 2227.88  337.01 2289.68  336.34
IW Dist,WD,Coef,Skew,MaxSub,Min_El,Is_Ogee,SpillHt,DesHd
30,10,2.6,0,0.98,, 0 ,,,0,0,

Type RM Length L Ch R = 1 ,23716   ,95.18,133.29,194.62
XS GIS Cut Line= 5
1607409.16218571724318.9441166221606606.13746265723455.225662246
1606477.74688151723438.8850441281606260.65008169723191.441379562
1605980.52517705722661.538435012
#Sta/Elev= 30
       0  332.05   28.67  330.89   95.58   324.6  162.49  326.93  353.65  323.74
  420.55  323.75  640.39  328.75  783.76  327.23  936.68  327.38 1013.15  320.77
 1032.26  315.91 1127.84  300.12  1137.4   298.7 1166.08  297.52 1179.35   292.5
 1193.46   288.2 1221.68  288.95 1268.35  292.97  1327.4  296.42 1364.65  295.75
 1429.83     302 1504.33  310.88 1588.14  315.34 1645.87  320.18  1748.8  320.31
 1796.31  322.12 1820.06  324.79 1891.32  326.58 1978.42  330.66 2237.34  337.25
#Mann= 3 , 0 , 0
       0      .1       0 1179.35    .045       0 1268.35      .1       0
Bank Sta=1179.35,1268.35
XS Rating Curve= 0 ,0
Exp/Cntr=0.5,0.3

Type RM Length L Ch R = 1 ,23583   ,159.97,158.09,155.15
XS GIS Cut Line= 3
1607471.72341353724244.2441425621606701.37992863723424.878797561
1606101.44576073722619.519701019
#Sta/Elev= 30
       0  327.77   57.65  322.76  259.41  319.96  345.89  322.14  422.75   321.6
  691.77  328.86  864.71  332.05  951.18  327.54  999.22  322.65 1028.05  316.28
 1047.26  313.99 1066.48  310.11  1095.3  302.05 1114.52  299.73 1150.81  290.96
 1168.27   284.6 1185.73  278.41 1194.46  277.06 1243.48  284.67 1290.47  289.58
 1377.76  301.64 1421.41  312.94 1482.51  322.95 1534.88  333.02 1595.98  333.67
 1639.62  336.76 1735.64  334.74 1779.28  331.06 1918.94  328.32 2128.88   329.3
#Mann= 3 , 0 , 0
       0      .1       0 1168.27    .045       0 1243.48      .1       0
Bank Sta=1168.27,1243.48
XS Rating Curve= 0 ,0
Exp/Cntr=0.3,0.1

Type RM Length L Ch R = 1 ,23425   ,237.61,246.67,268.75
XS GIS Cut Line= 2
1607565.66991808724185.5451259911606083.44061857722467.129543334
#Sta/Elev= 30
       0  332.41  184.88  323.64  249.59  316.99  305.06  313.66  582.39  320.52
  785.76  319.07  868.96  320.92  905.94  323.84  933.67  321.61   961.4  316.49
  998.38  315.42 1026.11  306.15 1072.33  296.43 1109.31  275.98 1137.04  268.53
 1155.53  262.38 1183.27  259.88 1216.15  267.41 1257.22   274.2 1303.44  291.59
 1349.66  298.44 1395.88  317.49 1423.62  323.82 1543.79  342.78 1580.77  345.56
 1663.97  342.67 1811.88  331.15 1969.03  322.55    2006  318.96 2269.35   311.8
#Mann= 3 , 0 , 0
       0      .1       0 1137.04    .045       0 1216.15      .1       0
Bank Sta=1137.04,1216.15
XS Rating Curve= 0 ,0
Exp/Cntr=0.3,0.1

Type RM Length L Ch R = 1 ,23178   ,343.5,354.32,352.99
XS GIS Cut Line= 4
1607621.12336355724122.8566837461607051.53605849  723289.4850941
1606988.50795557 723072.388294251606269.52070238722404.757274643
#Sta/Elev= 30
       0  332.04  169.58  326.75  356.11  317.81  457.85  309.87  517.21  297.67
  644.39  287.05  780.05  280.54  805.48  281.25  847.88  277.93  907.23   266.9
  941.14  256.71    1024  248.52 1075.03  235.81 1111.47   228.9 1126.05  228.23
 1140.63  229.46  1164.4   236.1 1220.81  245.41 1283.25  262.98 1350.12  277.96
  1493.4  300.51 1608.03  311.59 1636.69  311.55 1665.35  309.02 1751.32  309.62
 1865.95  303.91 1961.47  294.57 2028.34  291.05 2123.87  290.66 2216.65  293.42
#Mann= 3 , 0 , 0
       0      .1       0 1075.03    .045       0  1164.4      .1       0
Bank Sta=1075.03,1164.4
XS Rating Curve= 0 ,0
Exp/Cntr=0.3,0.1

Type RM Length L Ch R = 1 ,22824   ,622.16,581.78,341.39
XS GIS Cut Line= 4
1607706.01472858  724089.98138241607423.76890375723520.164340973
1607343.88801007723003.6012268361606321.41256906722311.300146103
#Sta/Elev= 30
       0  331.95  140.61  332.91  320.28  328.78  453.08  321.68  554.63  320.61
  635.89  314.47  685.47  313.73  763.39  298.84   841.3  263.07  897.97  244.03
  933.38  222.22  954.63  215.39  982.96   212.1  997.13  207.88  1011.3  203.12
 1032.55  201.13 1082.13  207.99 1158.59  219.89 1226.22  237.95 1327.66  261.05
 1446.01  281.53 1513.64  282.83 1615.09  280.59 1826.43  283.14 1910.96  278.12
 2012.41  268.65 2063.13  267.37 2198.39  274.04 2274.47  274.56 2393.39   283.2
#Mann= 3 , 0 , 0
       0      .1       0  997.13    .045       0 1082.13      .1       0
Bank Sta=997.13,1082.13
XS Rating Curve= 0 ,0
Exp/Cntr=0.3,0.1