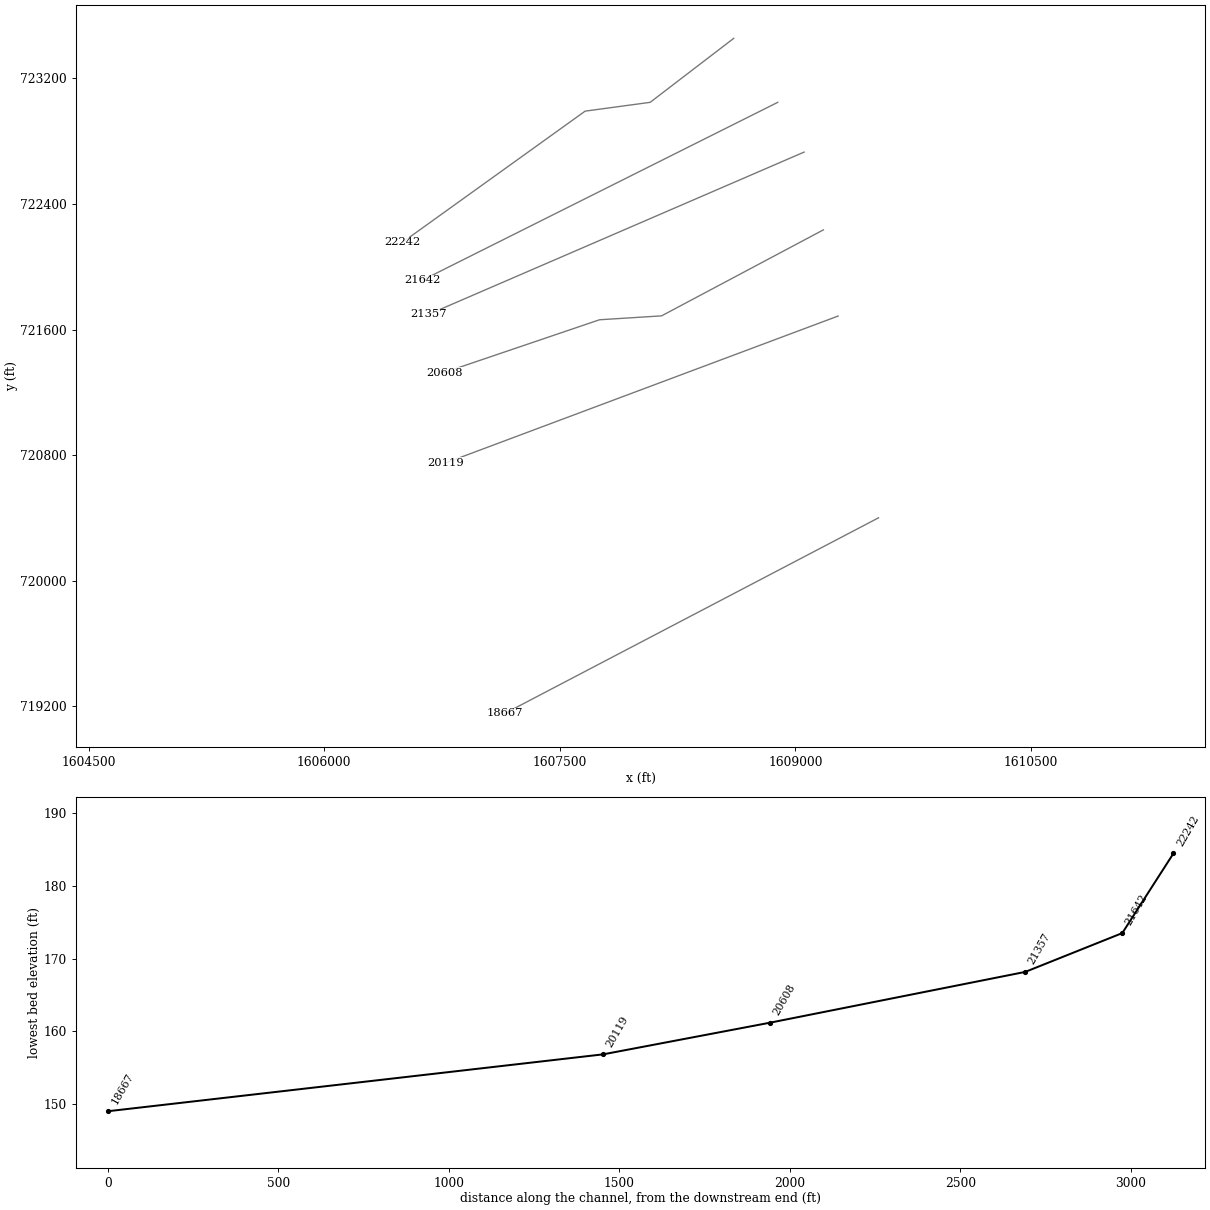
HEC-RAS study NortheastCreek.prj: Northeast Creek

--- NortheastCreek.g04 (geometry) --- (continued)

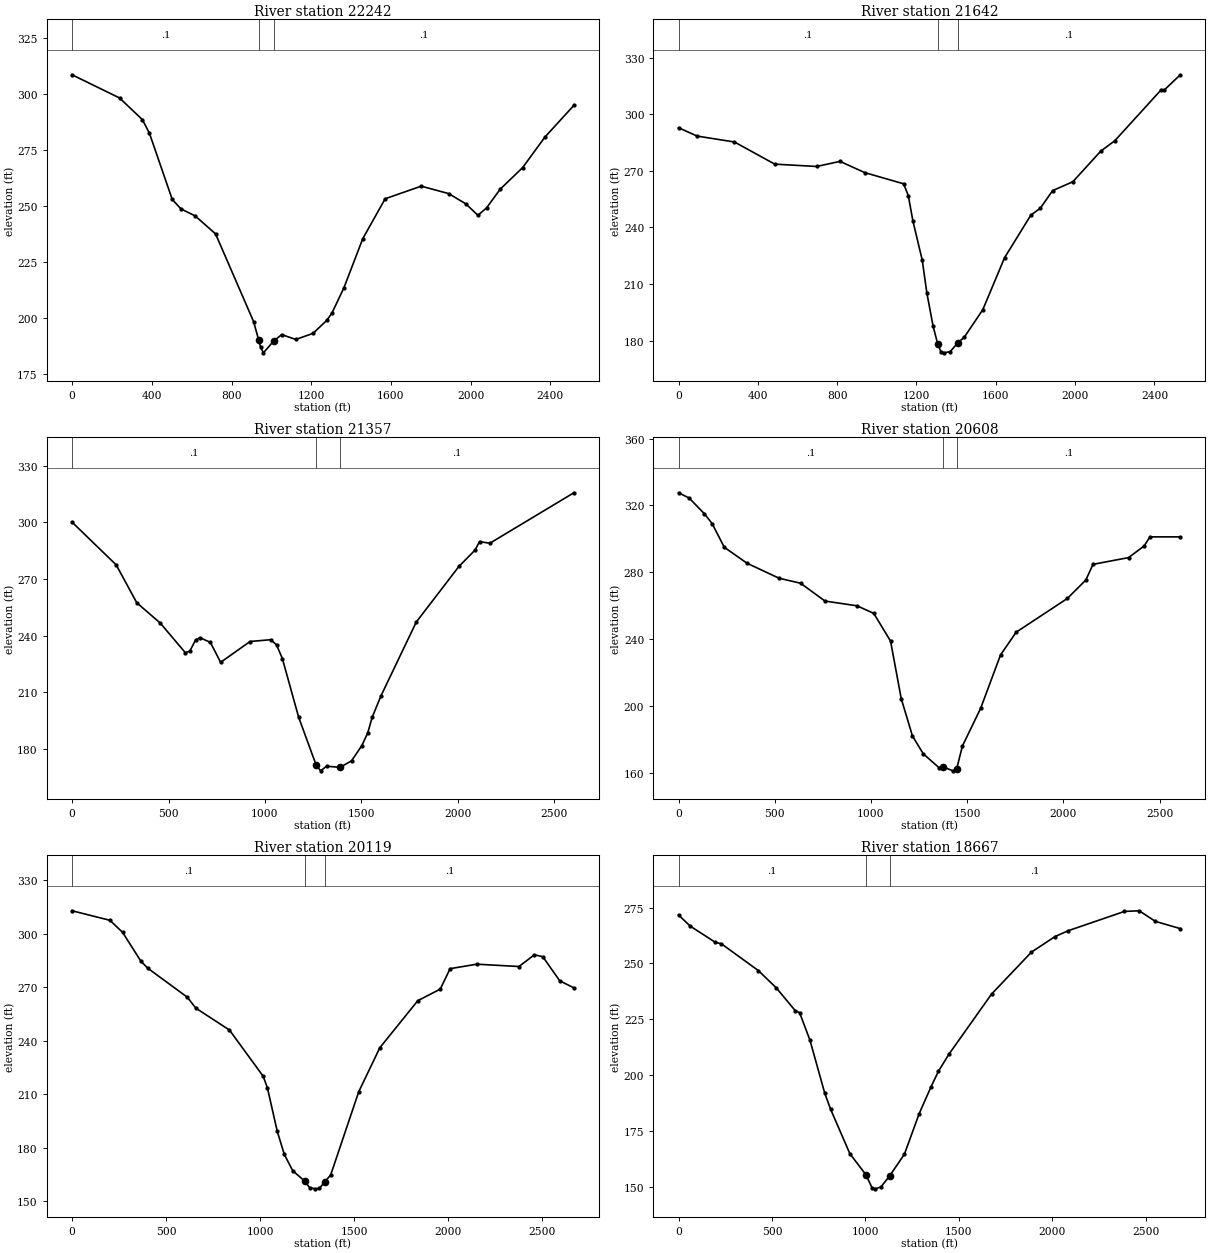
Type RM Length L Ch R = 1 ,22242   ,145.35,150.07,135.07
XS GIS Cut Line= 4
1608607.31864934723455.2256622461608075.08133128723047.488304153
1607661.11897469722991.4633217011606500.15687372722157.313610077
#Sta/Elev= 30
       0  308.66  238.09  298.31  352.72  288.63  387.99  282.59  502.63  252.96
  546.72  248.72  617.26  245.63  719.91   237.6  910.64  198.44  935.85  190.36
  945.96  186.93  960.08  184.44 1012.14  189.77 1051.91  192.58 1122.68  190.42
 1208.88  193.13 1277.83  198.92 1303.69  202.16 1364.03  213.51 1458.84  235.47
  1570.9  253.27 1751.91   258.9 1889.82  255.57 1976.01  250.98 2036.35  245.88
 2079.45  249.16  2148.4  257.57 2260.45  267.16 2372.51  280.83 2517.76  294.98
#Mann= 3 , 0 , 0
       0      .1       0  935.85    .045       0 1012.14      .1       0
Bank Sta=935.85,1012.14
XS Rating Curve= 0 ,0
Exp/Cntr=0.3,0.1

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
Type RM Length L Ch R = 1 ,21642   ,291.57,284.54,280.25
XS GIS Cut Line= 2
1608887.44355202723047.4883041531606624.65682989721914.538692504
#Sta/Elev= 30
       0  292.91   93.94  288.47  281.82  285.34  485.36  273.59  696.73  272.35
  814.15  275.06  939.41  269.09 1135.12  263.16  1158.6  256.94 1182.09  243.37
 1229.06  222.67 1252.54  205.09 1283.85  187.63 1307.34  178.04    1323   174.2
 1338.65   173.5 1369.97  174.16 1409.11  178.89 1440.42  181.71 1534.36  196.36
 1643.96   223.9 1777.04  246.61 1824.01  250.14 1886.64  259.56 1988.41  264.24
 2129.32  280.49 2199.77  285.96 2434.62  313.09 2450.28  312.97 2530.56  320.99
#Mann= 3 , 0 , 0
       0      .1       0 1307.34    .045       0 1409.11      .1       0
Bank Sta=1307.34,1409.11
XS Rating Curve= 0 ,0
Exp/Cntr=0.3,0.1

Type RM Length L Ch R = 1 ,21357   ,696.9,749.34,548.41
XS GIS Cut Line= 2
1609055.04091077722730.412546188 1606667.1193047721697.978607193
#Sta/Elev= 30
       0  300.15  228.79  277.48  335.56  257.38  457.58  246.56  587.22  230.87
   610.1  231.64   640.6  237.67  663.48  238.83  716.87  236.35  770.25  225.77
  922.77  236.81 1029.54  237.77 1060.05  235.06 1090.55  227.68 1174.44   196.7
 1265.95  171.09 1288.83  168.17 1319.34  170.63 1389.75  170.03 1448.98  173.51
 1502.37  181.58 1532.87  188.28 1555.75  196.56 1601.51  207.97 1784.54  247.15
  2005.7  276.66 2089.59  285.37 2112.47  289.85 2165.85  288.95 2601.55  315.75
#Mann= 3 , 0 , 0
       0      .1       0 1265.95    .045       0 1389.75      .1       0
Bank Sta=1265.95,1389.75
XS Rating Curve= 0 ,0
Exp/Cntr=0.3,0.1

Type RM Length L Ch R = 1 ,20608   ,448.69,488.68,483.19
XS GIS Cut Line= 4
1609178.15095332722235.1260833891608147.91380692721687.326271087
  1607752.626442721662.4262790981606762.85178378721326.276395828
#Sta/Elev= 30
       0  327.53    55.5  324.37  134.78  314.92  174.42  309.15  237.84  294.91
  356.76  285.33  523.25  276.39  634.24  273.43  761.09  262.76  927.58  259.92
 1014.79  255.39    1102  238.82 1157.49  204.42 1215.92  182.02 1272.03  171.38
  1356.2  162.84  1375.3  163.56 1426.34  161.19 1445.46  162.28 1475.43     176
 1570.29  198.58 1673.79  230.56  1755.1  244.14 2021.24  264.33 2117.35  275.38
 2154.31  284.72 2339.12  288.75 2420.44  295.74 2450.01  301.15 2608.19  301.15
#Mann= 3 , 0 , 0
       0      .1       0  1375.3    .045       0 1445.46      .1       0
Bank Sta=1375.3,1445.46
XS Rating Curve= 0 ,0
Exp/Cntr=0.3,0.1

Type RM Length L Ch R = 1 ,20119   ,1432.04,1452.31,1444.63
XS GIS Cut Line= 2
1609271.88419534721686.140932098 1606772.4800034720750.290960312
#Sta/Elev= 30
       0  312.87  201.81  307.51  269.09   300.7  366.26  284.56  403.63  280.56
  612.92  264.38  657.77  258.28  837.16  245.94 1016.55  220.01 1038.97   213.5
 1091.29  189.12 1128.67  176.23 1173.51  167.02 1237.55  161.15 1263.21  157.57
 1293.11  156.85 1315.53  157.08 1344.57  160.89 1375.33  164.59 1524.82  211.37
 1636.94  236.03 1838.75  262.42 1958.35  268.92 2010.67  280.39 2152.69   282.9
 2376.93  281.59 2459.15   288.2 2503.99  287.06 2593.69  273.59 2668.87  269.61
#Mann= 3 , 0 , 0
       0      .1       0 1237.55    .045       0 1344.57      .1       0
Bank Sta=1237.55,1344.57
XS Rating Curve= 0 ,0
Exp/Cntr=0.3,0.1

Type RM Length L Ch R = 1 ,18667   ,519.02,524.33,517.07
XS GIS Cut Line= 2
1609529.32717897720400.8450298461607150.41424756719155.045888916
#Sta/Elev= 30
       0  271.71   63.21  266.69  197.54  259.43  229.15  258.83   426.7  246.84
  521.52  239.22  624.24  228.89  647.95  227.95  703.26  215.65  782.28  191.94
  813.88  184.68  916.61  164.84 1003.53  155.26 1035.13  149.56 1050.94  149.04
 1082.54  149.83 1129.95  154.84 1208.97  164.59 1287.99  182.76  1351.2  194.74
 1390.71  201.68 1446.02  209.23 1675.17  236.29 1888.52  255.07 2014.95  262.06
 2086.06  264.69 2386.33  273.31 2465.35   273.6 2552.27  268.84 2685.38  265.61
#Mann= 3 , 0 , 0
       0      .1       0 1003.53    .045       0 1129.95      .1       0
Bank Sta=1003.53,1129.95
XS Rating Curve= 0 ,0
Exp/Cntr=0.5,0.3