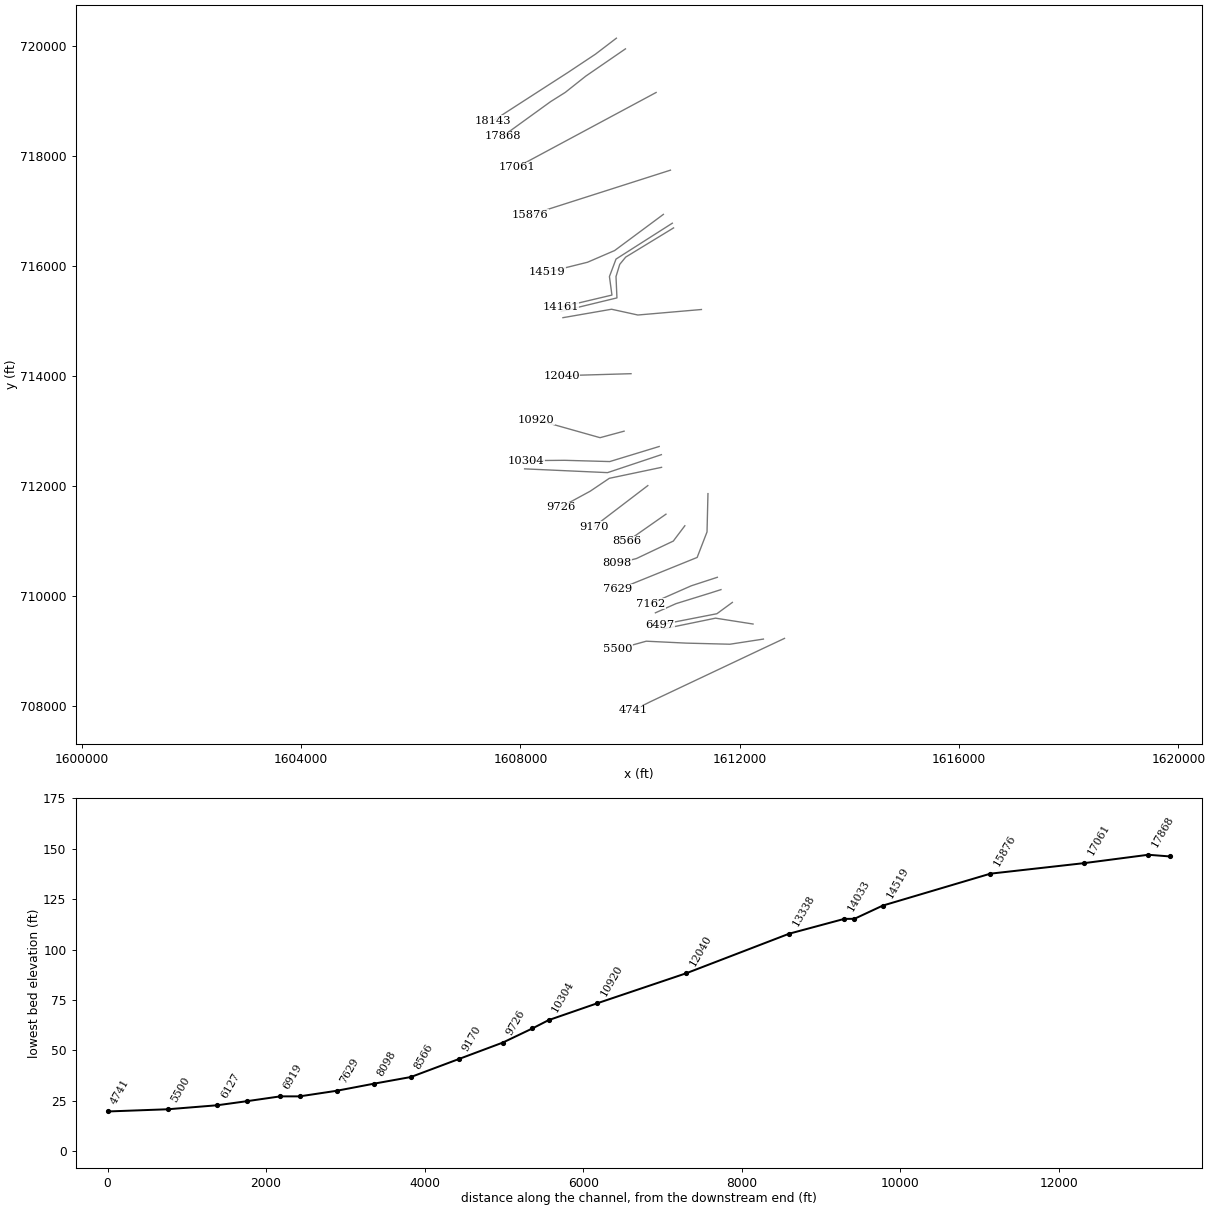
HEC-RAS study NortheastCreek.prj: Northeast Creek

--- NortheastCreek.g04 (geometry) --- (continued)

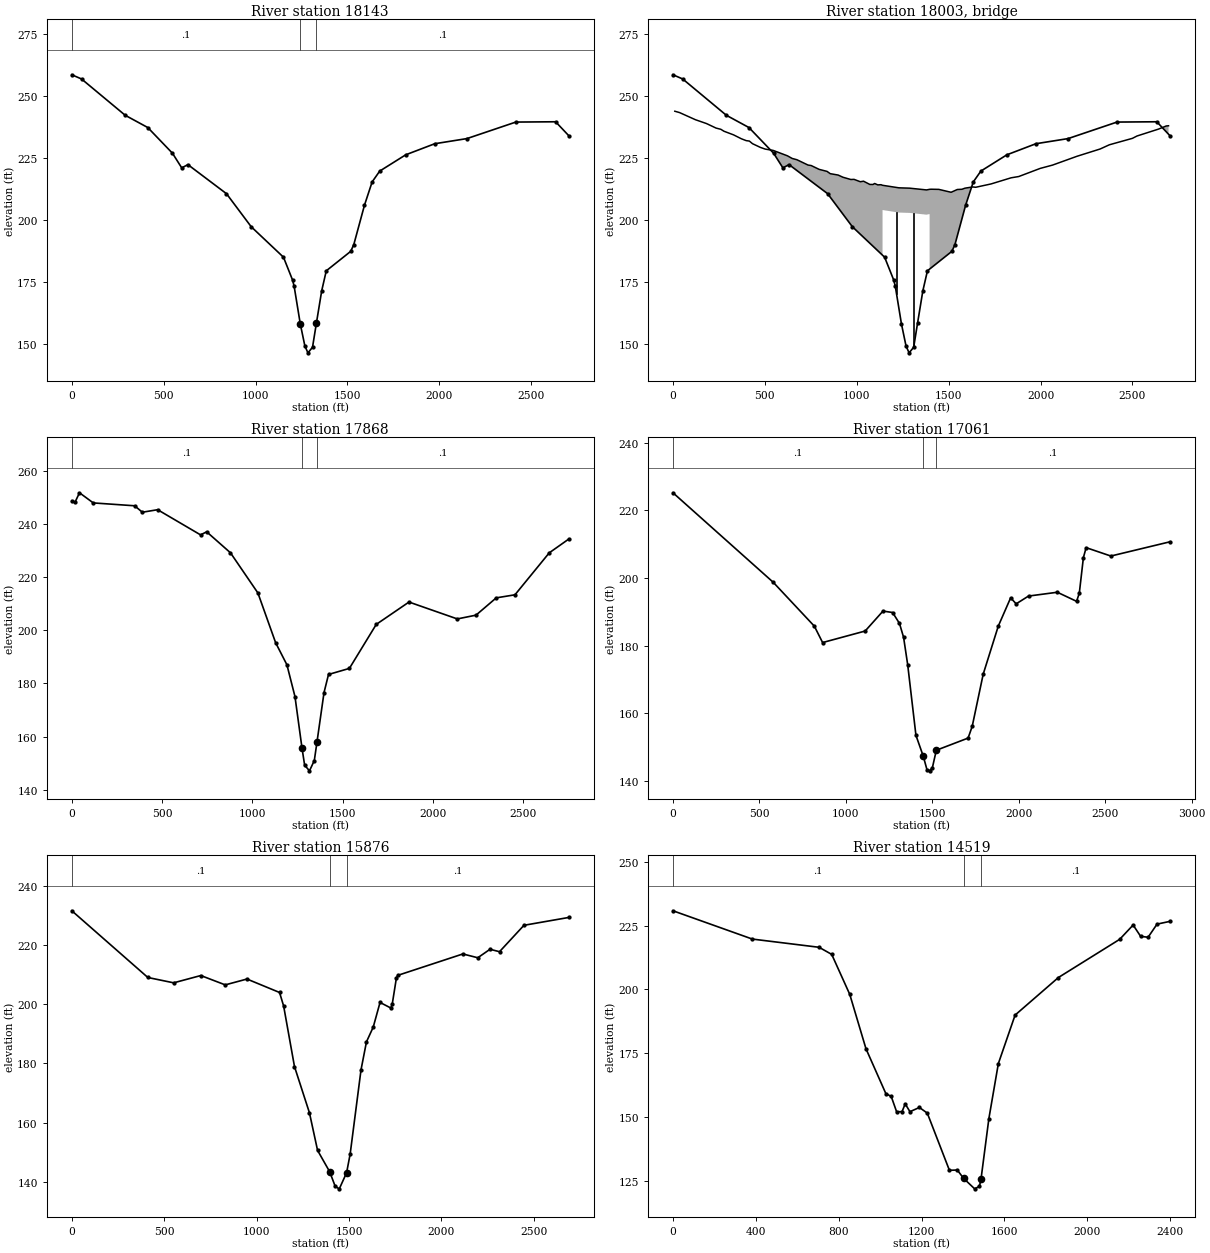
Type RM Length L Ch R = 1 ,18143   ,271.68,274.76,278.42
XS GIS Cut Line= 5
 1609750.0807057720136.8527164761609367.75175481719845.826200515
 1608863.7885609719511.6895199121608381.02797514719201.755172744
1607501.75821309 718636.06892015
#Sta/Elev= 30
       0   258.6   52.78  256.91  290.31  242.24  413.47  237.27  547.68  226.89
  598.07  220.98  631.67  222.29  841.64  210.54  976.02   197.2 1151.71  184.88
 1201.62  175.57 1209.94  173.06 1243.21  157.93 1268.17  149.01  1284.8  146.23
 1309.76  148.47 1330.82  158.19 1359.67  171.27 1384.63  179.38 1517.72  187.25
 1534.36  189.96 1592.59  205.91 1634.18   215.3  1675.5  219.68    1817  226.26
 1975.15  230.74 2149.94  232.81 2416.29  239.49 2632.71  239.61 2704.37  233.97
#Mann= 3 , 0 , 0
       0      .1       0 1243.21    .045       0 1330.82      .1       0
Bank Sta=1243.21,1330.82
XS Rating Curve= 0 ,0
Exp/Cntr=0.5,0.3

Type RM Length L Ch R = 3 ,18003   ,,,
BEGIN DESCRIPTION:
I-95, CE041807FS-4,
END DESCRIPTION:
Bridge Culvert--1,0,-1,-1, 0
Deck Dist Width WeirC Skew NumUp NumDn MinLoCord MaxHiCord MaxSubmerge Is_Ogee
60,155,2.6,0, 60, 60, , , 0.98, 0, 0,0,,
      10   35.89  122.18  182.58  234.36  260.25   277.5  329.28  372.42  398.31
  415.57  432.83  475.97  501.86  545.01  622.67  648.56  674.44  734.85  752.11
  795.25   838.4  855.66   898.8  924.69  967.84  985.09 1019.61 1036.87 1071.39
 1088.64 1097.27 1114.53 1131.79 1140.42 1229.19 1287.71 1379.65 1396.37 1404.73
 1446.52  1513.4  1547.2 1572.27 1588.99 1630.78  1647.5 1731.09 1839.75 1881.54
 1998.56 2065.43 2199.17 2324.55  2374.7 2500.08 2525.16 2642.18 2683.97 2696.68
  243.87  243.32  240.44  238.88  237.06  236.57  235.78  234.33  232.73  231.99
  231.81  230.75  229.24  228.57  228.04  225.86  224.79  224.27  222.12  221.92
  220.38  219.56  218.64  218.08   217.2  216.28  216.34  215.38   215.6  214.28
  214.27  214.67   214.1  214.18  213.94  212.92  212.78  212.07  212.31  212.35
  212.29  211.12  212.24  212.33  212.78  213.27  213.14  214.49  216.96  217.48
  220.77   222.1  225.68  228.61  230.31  232.91  233.86  236.65  237.91     238
                                                                                
                                                                                
                                                                                
                                  203.94  202.92  202.78  202.07  202.31
                                                                                
                                                                                
      50   75.89  162.18  222.58  274.36  300.25   317.5  369.28  412.42  438.31
  455.57  472.83  515.97  541.86  585.01  662.67  688.56  714.44  774.85  792.11
  835.25   878.4  895.66   938.8  964.69 1007.84 1025.09 1059.61 1076.87 1111.39
 1128.64 1137.27 1154.53 1171.79 1180.42 1269.19 1327.71 1419.65 1436.37 1444.73
 1486.52  1553.4  1587.2 1612.27 1628.99 1670.78  1687.5 1771.09 1879.75 1921.54
 2038.56 2105.43 2239.17 2364.55  2414.7 2540.08 2565.16 2682.18 2723.97 2736.68
  243.87  243.32  240.44  238.88  237.06  236.57  235.78  234.33  232.73  231.99
  231.81  230.75  229.24  228.57  228.04  225.86  224.79  224.27  222.12  221.92
  220.38  219.56  218.64  218.08   217.2  216.28  216.34  215.38   215.6  214.28
  214.27  214.67   214.1  214.18  213.94  212.92  212.78  212.07  212.31  212.35
  212.29  211.12  212.24  212.33  212.78  213.27  213.14  214.49  216.96  217.48
  220.77   222.1  225.68  228.61  230.31  232.91  233.86  236.65  237.91     238
                                                                                
                                                                                
                                                                                
                                  203.94  202.92  202.78  202.07  202.31
                                                                                
                                                                                
Pier Skew, UpSta & Num, DnSta & Num=  ,1217, 2 ,1257, 2 , 0 , 0 , 0 ,,
       5       5
     140     205
       5       5
     140     205
Pier Skew, UpSta & Num, DnSta & Num=  ,1307, 2 ,1347, 2 , 0 , 0 , 0 ,,
       5       5
     140     205
       5       5
     140     205
BR Coef=-1 , 1 , 0 ,, 0 ,,,0.8,-1,1.2,0,
WSPro=,,,, 1 ,,,, 0 ,,,, 0 ,,,,-1 ,-1 ,-1 , 0 , 0 , 0 , 0 , 0
BC Design=,, 0 ,, 0 ,,,,,,
BC Use User HTab Curves=0
BC User HTab FreeFlow(D)= 0

Type RM Length L Ch R = 1 ,17868   ,823.68,806.49,789.35
XS GIS Cut Line= 5
1609915.56637196719942.8350391691609190.85328485719446.378042251
1608817.10107614 719150.639642731608551.73623085 718984.15945816
1607672.95028117718350.748806015
#Sta/Elev= 30
       0  248.78   16.97  248.18   42.42  251.84  118.79  248.02  347.88  246.94
  390.31  244.51  475.16  245.46  712.74  235.98  746.68  237.13  878.45  229.22
  1030.2   214.1 1128.39  195.35 1190.87  187.03  1235.5  175.06 1274.26  155.73
 1289.06  149.19 1315.84  147.07 1342.62  150.96 1357.09  157.78 1396.37  176.57
 1421.16  183.38 1536.85  185.67 1685.58  202.25 1866.78  210.67 2134.28  204.31
 2237.82  205.73    2350  212.25 2453.55   213.4 2643.38  229.21  2751.6  234.41
#Mann= 3 , 0 , 0
       0      .1       0 1274.26    .045       0 1357.09      .1       0
Bank Sta=1274.26,1357.09
XS Rating Curve= 0 ,0
Exp/Cntr=0.5,0.3

Type RM Length L Ch R = 1 ,17061   ,1180.2,1185.07,1142.26
XS GIS Cut Line= 2
1610474.79379465 719149.645124451607940.46375281717793.431251556
#Sta/Elev= 30
       0  225.17  579.57  198.71  817.75  185.71  865.38  180.87  1111.5  184.28
 1214.71  190.18 1270.29  189.76 1309.98  186.53  1333.8  182.42 1357.62  174.28
 1405.25  153.43 1447.83  147.23 1468.77  143.32 1484.65  142.93 1500.53   143.9
 1523.14  149.02 1706.95  152.62 1730.77   156.1 1794.28  171.52 1881.61  185.75
 1953.07  194.11 1984.83  192.32 2056.28  194.62    2223  195.75 2334.15  193.07
 2350.03  195.42 2373.85  206.02 2389.73  208.94 2532.63  206.46 2874.39  210.67
#Mann= 3 , 0 , 0
       0      .1       0 1447.83    .045       0 1523.14      .1       0
Bank Sta=1447.83,1523.14
XS Rating Curve= 0 ,0
Exp/Cntr=0.3,0.1

Type RM Length L Ch R = 1 ,15876   ,1284.01,1357.48,1277.81
XS GIS Cut Line= 2
1610736.14701848717737.310562149 1608173.9723988716921.295038253
#Sta/Elev= 30
       0  231.51   411.4     209  550.98   207.2  697.91  209.66  830.15  206.51
  947.69  208.48    1124  203.94 1146.04  199.38 1204.82  178.93 1285.63  163.36
  1329.7  150.66 1395.31  143.44 1425.21  138.51 1447.25  137.69 1486.74  143.13
 1506.02  149.43 1564.79  177.86 1594.18  187.28 1630.91  192.27 1667.64  200.58
 1726.41  198.69 1733.76  200.03  1755.8  208.68 1763.14  209.71 2115.77  216.94
 2196.58  215.66  2262.7  218.52 2314.13   217.7 2446.36  226.61 2688.98  229.26
#Mann= 3 , 0 , 0
       0      .1       0 1395.31    .045       0 1486.74      .1       0
Bank Sta=1395.31,1486.74
XS Rating Curve= 0 ,0
Exp/Cntr=0.3,0.1

Type RM Length L Ch R = 1 ,14519   ,323.88,357.84,384.72
XS GIS Cut Line= 4
1610607.35035518 716933.26641655  1609718.388155716275.935213119
1609223.82467653716063.0851078331608491.36990552715881.536489517
#Sta/Elev= 30
       0  230.83  383.06  219.74  705.17  216.52  766.11  213.74  853.17  198.08
  931.52  176.75 1027.29   159.2  1053.4  158.05 1079.52  152.03 1105.59  152.12
 1120.83  155.15  1143.7  152.09 1189.42  153.74 1227.52  151.52 1334.21  129.12
 1372.32  129.22  1402.8  125.94 1456.15  121.85 1479.01  122.84 1486.63  125.61
 1524.73  149.41 1570.46  170.96 1651.22  189.95 1860.37  204.68 2156.05  219.64
 2220.96  225.25 2257.02  220.82 2293.08  220.45 2336.35   225.6 2398.63  226.68
#Mann= 3 , 0 , 0
       0      .1       0  1402.8    .045       0 1486.63      .1       0
Bank Sta=1402.8,1486.63
XS Rating Curve= 0 ,0
Exp/Cntr=0.5,0.3

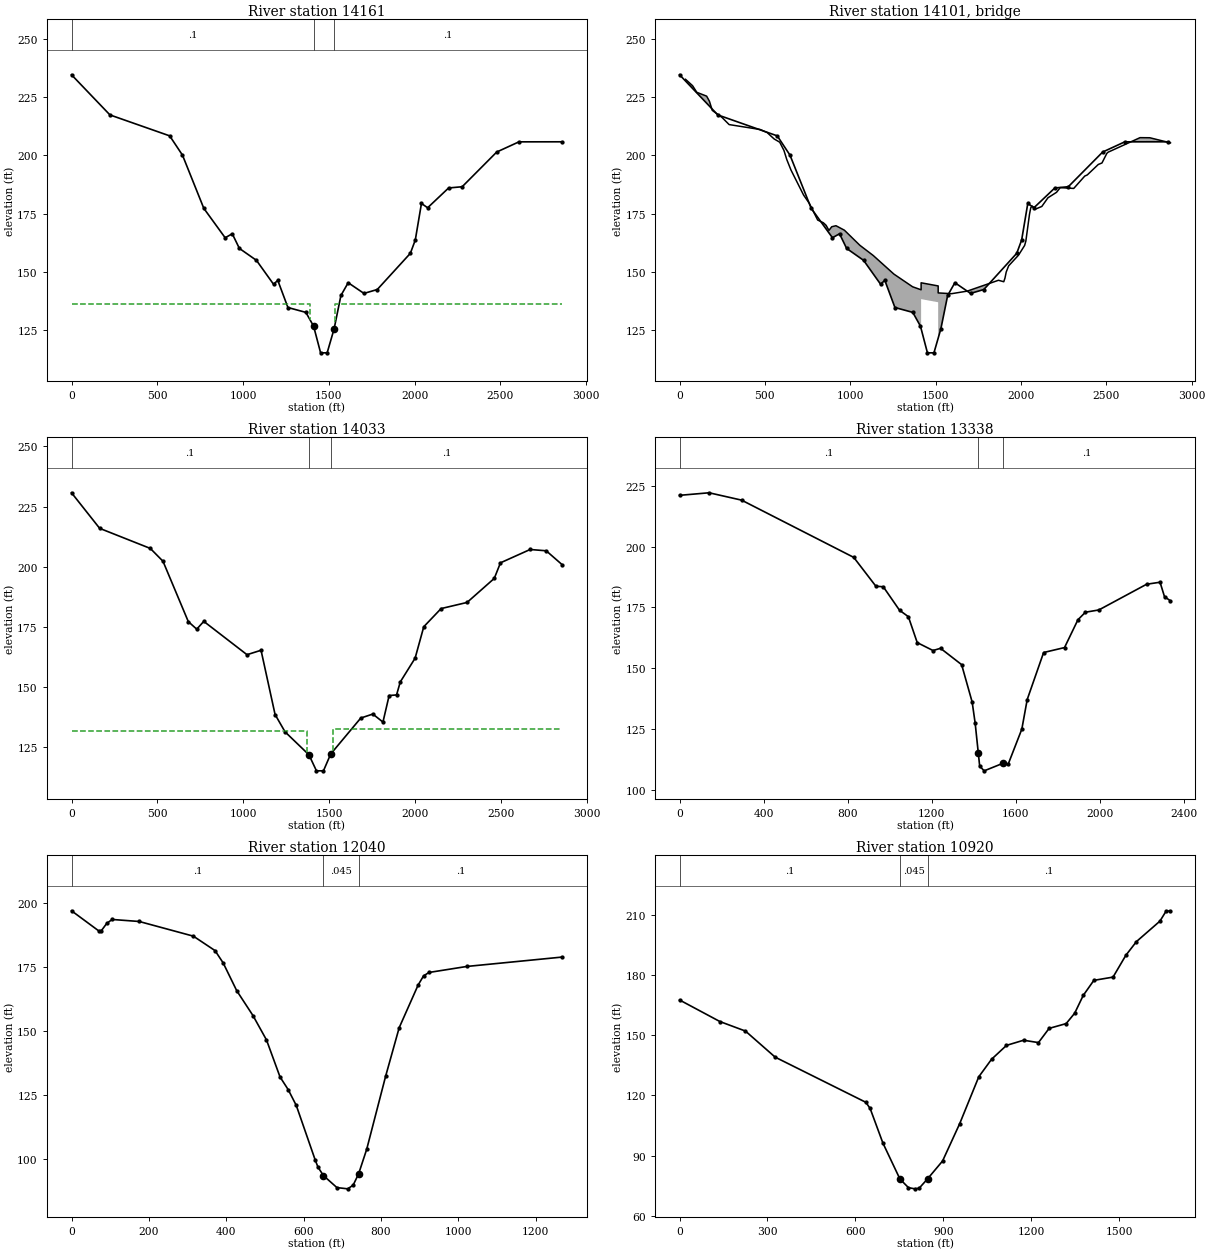
Type RM Length L Ch R = 1 ,14161   ,117.98,128.09,159.17
XS GIS Cut Line= 5
1610770.38543133716772.9285793451609743.42934233 716120.67984201
1609623.39857675715802.8401928251609669.04979324 715466.16245845
 1608729.2611981715244.238237396
#Sta/Elev= 30
       0  234.64   223.9  217.41  572.18  208.42  646.82  200.14  771.21   177.3
  895.59  164.68  937.06  166.39  978.52  160.11 1078.03  154.98 1177.54  144.73
 1202.42  146.38 1261.48  134.74 1366.23  132.64 1411.13  126.74 1452.04  115.28
 1490.21  115.28 1530.85  125.62 1570.46   139.9 1612.84  145.38 1704.68  140.79
 1782.38  142.46 1975.21     158 2003.98   163.7 2039.94  179.41  2075.9  177.55
 2198.18  186.05  2277.3  186.58 2478.69  201.48 2608.16  205.85 2861.74  205.87
#Mann= 3 , 0 , 0
       0      .1       0 1411.13    .045       0 1530.85      .1       0
#XS Ineff= 2 , 0
         1391.33  136.37 1538.84          136.37
Permanent Ineff=
       F       F
Bank Sta=1411.13,1530.85
XS Rating Curve= 0 ,0
Exp/Cntr=0.5,0.3

Type RM Length L Ch R = 3 ,14101   ,,,
BEGIN DESCRIPTION:
Lums Road, CE041307PF-3, channel inverts adjusted based on bridge survey
END DESCRIPTION:
Bridge Culvert--1,0,-1,-1, 0
Deck Dist Width WeirC Skew NumUp NumDn MinLoCord MaxHiCord MaxSubmerge Is_Ogee
40,40,2.6,0, 60, 60, , , 0.98, 0, 0,0,,
      35   76.17  100.88  158.52  174.99  191.46   249.1  290.27  471.44  512.61
  553.78  586.72  611.42  627.89   652.6  726.71  759.65  809.05  841.99  858.46
  874.93   891.4   916.1  965.51 1056.45 1134.44 1255.81 1365.07    1415    1415
    1515    1515 1593.37 1685.18 1868.23 1899.18 1906.37 1913.56 1927.94 1985.48
 2021.43 2028.63  2050.2 2057.39 2064.58 2086.16 2122.12 2158.07 2208.42 2229.99
  2309.1 2373.82 2388.21 2452.93 2474.51 2503.27 2510.47 2697.45 2754.98 2875.91
  232.69  229.95  227.11  225.47  223.27  219.35  216.29  213.26  211.16  209.86
   207.1   205.7  202.16  198.28  193.76  182.98  179.49  172.28  171.13  170.01
  167.84  169.41  169.85  167.93  161.43  157.07  149.07  143.64  142.34  145.35
     144     141  140.67  141.77  146.43   145.8  147.38  149.97  152.64   157.2
  161.37  163.27  174.89  177.52  178.32  177.01  178.12  181.84  184.19   186.2
  185.85  191.17  191.63  196.14  196.78  200.93  201.41  207.65  207.61   205.4
                                                                                
                                                                                
                                                                          138.34
     137
                                                                                
                                                                                
      20   61.17   85.88  143.52  159.99  176.46   234.1  275.27  456.44  497.61
  538.78  571.72  596.42  612.89   637.6  711.71  744.65  794.05  826.99  843.46
  859.93   876.4   901.1  950.51 1041.45 1119.44 1240.81 1350.07    1400    1400
    1500    1500 1578.37 1670.18 1853.23 1884.18 1891.37 1898.56 1912.94 1970.48
 2006.43 2013.63  2035.2 2042.39 2049.58 2071.16 2107.12 2143.07 2193.42 2214.99
  2294.1 2358.82 2373.21 2437.93 2459.51 2488.27 2495.47 2682.45 2739.98 2775.94
  232.69  229.95  227.11  225.47  223.27  219.35  216.29  213.26  211.16  209.86
   207.1   205.7  202.16  198.28  193.76  182.98  179.49  172.28  171.13  170.01
  167.84  169.41  169.85  167.93  161.43  157.07  149.07  143.64  142.34  145.35
     144     141  140.67  141.77  146.43   145.8  147.38  149.97  152.64   157.2
  161.37  163.27  174.89  177.52  178.32  177.01  178.12  181.84  184.19   186.2
  185.85  191.17  191.63  196.14  196.78  200.93  201.41  207.65  207.61  206.68
                                                                                
                                                                                
                                                                          138.34
     137
                                                                                
                                                                                
BR Coef=-1 , 0 , 0 ,, 0 ,,,0.8,-1,,0,
WSPro=,,,, 1 ,,,, 0 ,,,, 0 ,,,,-1 ,-1 ,-1 , 0 , 0 , 0 , 0 , 0
BC Design=,, 0 ,, 0 ,,,,,,
BC Use User HTab Curves=0
BC User HTab FreeFlow(D)= 0

Type RM Length L Ch R = 1 ,14033   ,758.78,695.25,603.57
XS GIS Cut Line= 6
1610793.21104056716687.3325443571609920.13149452716156.637134552
1609811.70985034716025.3898811641609743.23302273715802.840192825
1609760.35223009715414.8048381951608744.61262707715169.429540649
#Sta/Elev= 30
       0  230.72  163.83  215.95  458.74  207.61  532.46  202.29  679.91  177.22
  729.06  174.08  770.02  177.32 1021.72  163.48 1103.43  165.32 1185.15  138.64
 1243.22  131.44 1382.38   121.9 1426.09  115.25 1466.79  115.25 1508.88  122.22
 1684.05  137.17 1754.12  138.83 1813.22   135.5 1849.22  146.52 1892.43  146.77
 1914.04  152.16 2000.45  162.04 2050.86  175.09 2151.68  182.63 2302.91  185.18
 2461.34  195.16 2497.35  201.63 2670.18  207.17  2763.8  206.63 2858.18  200.76
#Mann= 3 , 0 , 0
       0      .1       0 1382.38    .045       0 1508.88      .1       0
#XS Ineff= 2 , 0
         1371.62  131.99 1523.28          132.55
Permanent Ineff=
       F       F
Bank Sta=1382.38,1508.88
XS Rating Curve= 0 ,0
Exp/Cntr=0.5,0.3

Type RM Length L Ch R = 1 ,13338   ,1283.37,1297.31,1299.82
XS GIS Cut Line= 4
1611301.08084299715203.6679554281610142.02536964715103.658275634
1609662.04547887715208.5545425561608775.24148609 715055.23106274
#Sta/Elev= 30
       0  221.05  140.52   222.1  295.09  219.08  829.07  195.56  934.46  183.71
  969.59   183.5 1046.87  173.86 1089.03   171.2 1131.19  160.56 1206.35  157.31
 1242.18  158.22 1342.49  151.51 1392.65  136.15 1406.98  127.45  1421.9  115.18
 1428.47  109.81 1449.97  107.89  1538.9  110.98 1564.61  110.73  1629.1  125.03
 1654.67  137.18 1732.81  156.49 1832.26  158.52  1896.2  169.96 1931.72  173.04
 1995.65  173.97 2222.97  184.53 2286.91  185.36 2308.22  179.41 2336.63  177.72
#Mann= 3 , 0 , 0
       0      .1       0  1421.9    .045       0  1538.9      .1       0
Bank Sta=1421.9,1538.9
XS Rating Curve= 0 ,0
Exp/Cntr=0.3,0.1

Type RM Length L Ch R = 1 ,12040   ,1120.24,1120.56,1104.64
XS GIS Cut Line= 2
 1610017.4834685714036.7262115331608748.52660477713999.993249699
#Sta/Elev= 30
       0  196.82   70.03  189.01   77.03  189.03   91.04  191.89  105.04  193.43
  175.07  192.64  315.13  186.91  371.16  181.27  392.16  176.46  427.18  165.63
   469.2  155.92  504.21  146.39  539.23  131.94  560.23  127.02  581.24  120.82
  630.26   99.49  637.27   96.78  651.27   93.47  686.29   88.76   714.3   88.27
   728.3   89.72  742.31   94.08  763.32  103.71  812.34  132.27  847.35  151.18
  896.38  167.85  910.38  171.41  924.39  172.74 1022.43  175.09 1269.49  178.76
#Mann= 3 , 0 , 0
       0      .1       0  651.27    .045       0  742.31      .1       0
Bank Sta=651.27,742.31
XS Rating Curve= 0 ,0
Exp/Cntr=0.3,0.1

Type RM Length L Ch R = 1 ,10920   ,558.63,615.76,630.86
XS GIS Cut Line= 3
1609890.58778217 712991.506479011609452.39048007712873.257448226
1608276.68764116 713203.57395938
#Sta/Elev= 30
       0  167.44  137.76   156.7  224.76  151.97  326.27  138.97  635.65  116.49
  650.19  113.44  693.82   96.19  751.98   78.27  781.07   73.99  802.88    73.4
  817.42   73.69  846.51   78.43   897.4   87.27  955.57  105.77 1021.01  129.21
 1064.64  137.94 1115.53  144.84  1173.7   147.4  1224.6  146.23 1260.95   153.3
 1319.12  155.69  1348.2  160.86 1377.29   169.7 1413.64  177.22 1479.08  178.84
 1522.71  189.68 1559.06  196.54 1639.04  206.71 1660.86  211.87 1675.09  211.64
#Mann= 3 , 0 , 0
       0      .1       0  751.98    .045       0  846.51      .1       0
Bank Sta=751.98,846.51
XS Rating Curve= 0 ,0
Exp/Cntr=0.5,0.3

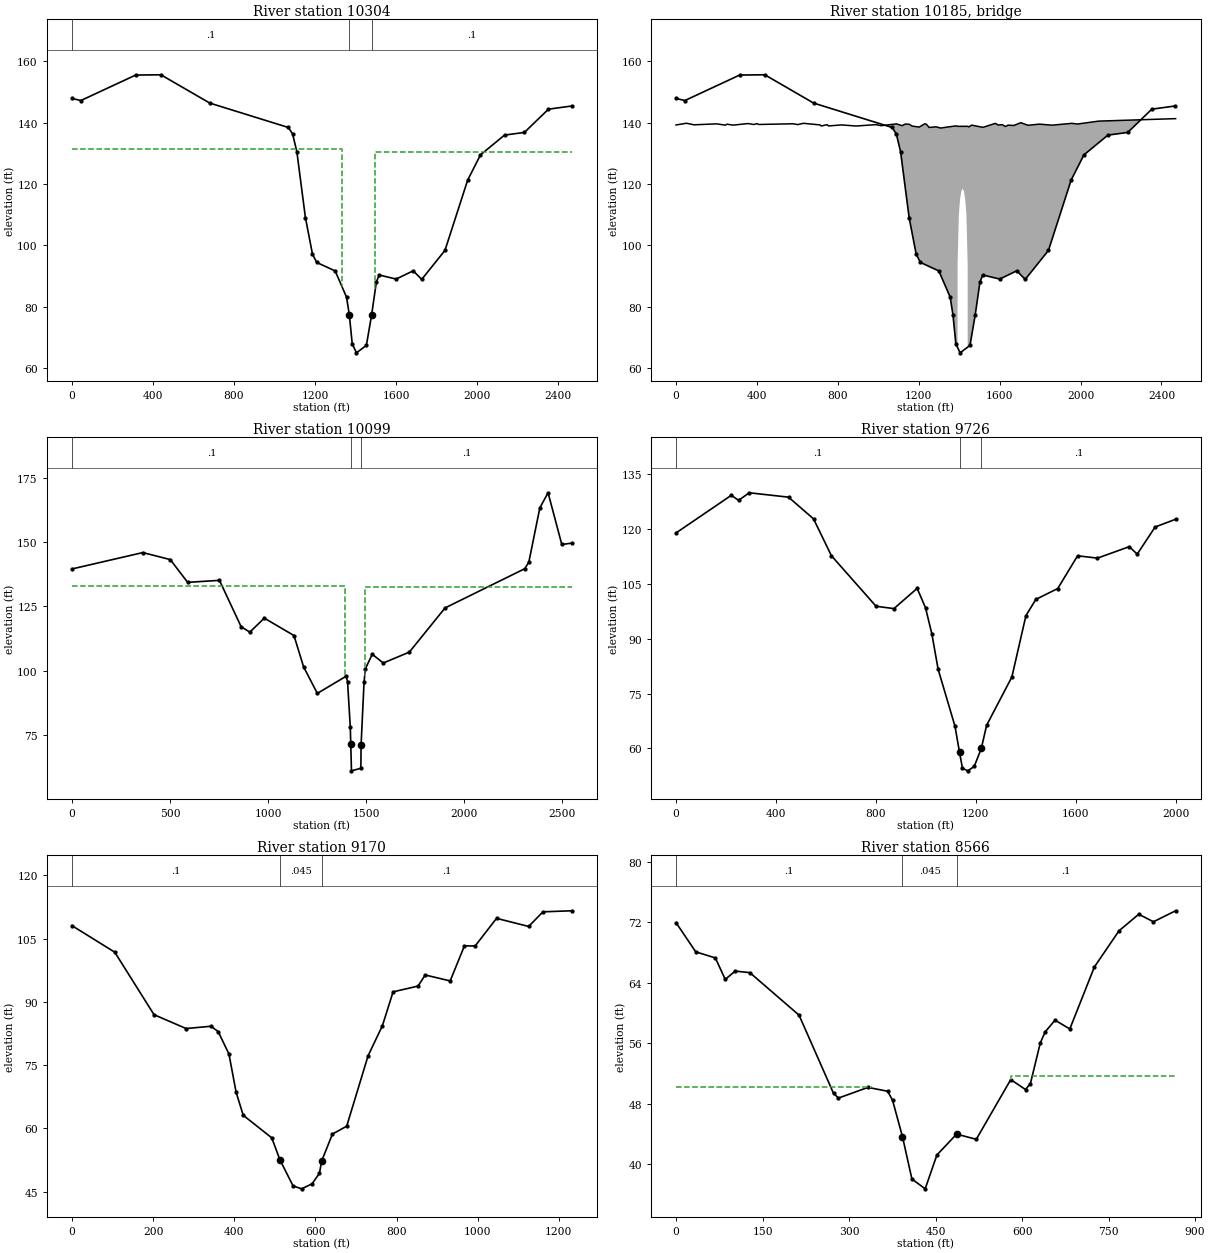
Type RM Length L Ch R = 1 ,10304   ,227.15,205.09,232.74
XS GIS Cut Line= 4
1610530.71653754712712.8233642731609629.10497858712438.916055694
1608807.38305096712461.7416649161608105.49557307712456.035263076
#Sta/Elev= 30
       0  147.89    43.9   147.2  314.58   155.5  438.95  155.59  680.38  146.37
 1068.35  138.42 1089.36  136.29 1110.37  130.46 1152.38  109.09 1187.39   97.13
  1208.4   94.45 1299.44   91.69 1355.46   83.14 1369.46   77.27 1383.47   67.95
 1404.48   65.01  1453.5   67.45  1479.5   77.48 1502.52   88.03 1516.52   90.37
 1600.55   89.04 1684.59   91.73  1726.6   88.94 1841.34   98.38 1953.34  121.26
 2016.35  129.47 2135.35  135.94 2233.35  136.81 2352.36  144.39 2466.25  145.41
#Mann= 3 , 0 , 0
       0      .1       0 1369.46    .045       0  1479.5      .1       0
#XS Ineff= 2 , 0
         1334.46  131.35 1497.75          130.41
Permanent Ineff=
       F       F
Bank Sta=1369.46,1479.5
XS Rating Curve= 0 ,0
Exp/Cntr=0.5,0.3

Type RM Length L Ch R = 3 ,10185   ,,,
BEGIN DESCRIPTION:
Chessie System Railroad Bridge, CE042607FS-1
END DESCRIPTION:
Bridge Culvert--1,0,-1,-1, 0
Deck Dist Width WeirC Skew NumUp NumDn MinLoCord MaxHiCord MaxSubmerge Is_Ogee
80,60,2.6,0, 60, 60, , , 0.98, 0, 0,0,,
       0   51.92   89.01  200.26  244.76  252.18  281.85  356.02  385.69  400.52
  407.94  578.53  600.79  630.45  712.04  718.44  746.96  754.09  818.26  889.57
   989.4 1013.19 1090.22 1118.24 1132.25 1153.26 1167.26 1202.28  1230.3  1237.3
 1251.31 1286.32 1307.33 1384.37    1392 1398.25  1404.5 1410.75    1417 1423.25
  1429.5 1435.75    1442 1447.41 1461.41 1517.44 1578.64 1592.66 1613.68 1627.69
 1641.71 1669.74 1704.78 1739.82 1795.88 1858.95 1957.06 1985.09 2090.21 2469.88
  139.24   139.8  139.29   139.6  139.19   139.5  139.19   139.7  139.39   139.7
   139.4  139.63  139.36  139.78  139.26   138.9  139.34  138.92  139.26   138.9
  139.35  139.01  139.59  139.01  139.52  139.48  138.88  138.56  139.63   139.5
  138.43  138.64  138.24  138.95   138.8   138.8   138.8   138.8   138.8   138.8
   138.8   138.8   138.8  138.61  139.19  138.47  139.76  139.23  139.34  138.74
  139.18  139.08  139.98  139.14  139.51  139.18  139.77  139.55   140.5   141.3
                                                                                
                                                                                
                                                                                
                                    93.5 110.036 115.151 117.706   118.5 117.706
 115.151 110.036    93.5
                                                                                
      30   81.92  119.01  230.26  274.76  282.18  311.85  386.02  415.69  430.52
  437.94  608.53  630.79  660.45  742.04  748.44  776.96  784.09  848.26  919.57
  1019.4 1043.19 1120.22 1148.24 1162.25 1183.26 1197.26 1232.28  1260.3  1267.3
 1281.31 1316.32 1337.33 1414.37    1422 1428.25  1434.5 1440.75    1447 1453.25
  1459.5 1465.75    1472 1477.41 1491.41 1547.44 1608.64 1622.66 1643.68 1657.69
 1671.71 1699.74 1734.78 1769.82 1825.88 1888.95 1987.06 2015.09 2120.21 2499.88
  139.24   139.8  139.29   139.6  139.19   139.5  139.19   139.7  139.39   139.7
   139.4  139.63  139.36  139.78  139.26   138.9  139.34  138.92  139.26   138.9
  139.35  139.01  139.59  139.01  139.52  139.48  138.88  138.56  139.63   139.5
  138.43  138.64  138.24  138.95   138.8   138.8   138.8   138.8   138.8   138.8
   138.8   138.8   138.8  138.61  139.19  138.47  139.76  139.23  139.34  138.74
  139.18  139.08  139.98  139.14  139.51  139.18  139.77  139.55   140.5   141.3
                                                                                
                                                                                
                                                                                
                                    93.5 110.036 115.151 117.706   118.5 117.706
 115.151 110.036    93.5
                                                                                
BR Coef=-1 , 0 , 0 ,, 0 ,,,0.8,-1,,0,
WSPro=,,,, 1 ,,,, 0 ,,,, 0 ,,,,-1 ,-1 ,-1 , 0 , 0 , 0 , 0 , 0
BC Design=,, 0 ,, 0 ,,,,,,
BC Use User HTab Curves=0
BC User HTab FreeFlow(D)= 0

Type RM Length L Ch R = 1 ,10099   ,299.28,372.4,380.65
XS GIS Cut Line= 3
1610570.66135222712564.4569053651609589.00081064 712237.77952005
1608076.32633211712306.254497558
#Sta/Elev= 30
       0  139.61  361.49     146  501.66  143.26  590.19  134.39   752.5  135.16
  863.16  117.07  907.42  114.97   981.2  120.43 1132.69  113.64 1181.74  101.43
 1251.81   91.07 1398.96   97.78 1405.97   95.68 1419.99    77.9 1422.39   71.19
    1426   60.87    1474   61.87    1475   70.85 1490.06   95.33 1497.07   100.7
  1532.1  106.35 1588.16  102.92  1721.3  107.18 1903.48  124.41  2309.9   139.7
 2330.92  142.28 2386.97  163.43 2429.02  169.32 2499.09  149.15 2548.81  149.67
#Mann= 3 , 0 , 0
       0      .1       0 1422.39    .045       0    1475      .1       0
#XS Ineff= 2 , 0
         1395.27  133.03 1493.24          132.58
Permanent Ineff=
       F       F
Bank Sta=1422.39,1475
XS Rating Curve= 0 ,0
Exp/Cntr=0.5,0.3

Type RM Length L Ch R = 1 ,9726    ,551.64,556.87,570.38
XS GIS Cut Line= 4
1610573.83214298712333.9283725321609620.86296381712134.204293385
1609272.77242583711900.2418014261608738.57378305711611.449418202
#Sta/Elev= 30
       0  118.99  221.71  129.31  250.32  127.91  293.24  129.99  450.58  128.79
  550.71  122.84  622.23  112.76  801.03   98.92  872.55   98.28  965.53  103.82
  998.98   98.52 1024.28    91.4 1049.58   81.66 1117.06   66.07  1135.2   58.91
    1147   54.57    1168   53.87    1194   55.07 1222.61   60.04 1243.57   66.33
 1344.78   79.56 1401.04   96.35 1440.83  100.81 1528.36  103.77 1607.93  112.74
 1687.51   112.1 1814.83  115.24 1846.66  113.19 1918.27  120.62 2000.35  122.74
#Mann= 3 , 0 , 0
       0      .1       0  1135.2    .045       0 1222.61      .1       0
Bank Sta=1135.2,1222.61
XS Rating Curve= 0 ,0
Exp/Cntr=0.3,0.1

Type RM Length L Ch R = 1 ,9170    ,617.28,603.36,595.67
BEGIN DESCRIPTION:
edited with hec-2 data
END DESCRIPTION:
XS GIS Cut Line= 2
1610323.27493224712001.8887304221609343.12635964711256.361851916
#Sta/Elev= 30
       0  108.07  105.54  101.77  202.28   86.96  281.43   83.67     343   84.22
  360.59   82.91  386.97   77.64  404.56   68.59  422.15   63.11  492.51   57.76
  512.54   52.56     545   46.37     566   45.67     592   46.87     610   49.37
  615.64   52.29  642.02   58.66   677.2   60.52  729.97   77.23  765.15   84.32
  791.54   92.37   853.1   93.74  870.69   96.37  932.25   94.96  967.43  103.28
  993.82  103.24 1046.59   109.8 1125.74  107.87 1160.92  111.34 1231.46  111.59
#Mann= 3 , 0 , 0
       0      .1       0  512.54    .045       0  615.64      .1       0
Bank Sta=512.54,615.64
XS Rating Curve= 0 ,0
Exp/Cntr=0.3,0.1

Type RM Length L Ch R = 1 ,8566    ,486.51,468.24,434.31
XS GIS Cut Line= 2
1610654.37657535711482.2126415821609943.93331465710986.656539992
#Sta/Elev= 30
       0   71.94   34.14   68.08   68.28   67.27   85.35   64.43  102.42   65.53
  128.02   65.33  213.37   59.71  273.11   49.38  281.64   48.76  332.85   50.17
  366.99   49.66  375.53   48.45   392.6   43.68     409   38.07     432   36.77
  452.34   41.24  486.48      44  520.62   43.31  580.36    51.2  605.96   49.89
   614.5   50.68  631.57   56.04   640.1   57.51  657.17   59.05  682.77   57.89
  725.45   66.09  768.12   70.86  802.26   73.04  827.86   72.05   866.2    73.5
#Mann= 3 , 0 , 0
       0      .1       0   392.6    .045       0  486.48      .1       0
#XS Ineff= 2 , 0
          337.84   50.28  581.08           51.63
Permanent Ineff=
       F       F
Bank Sta=392.6,486.48
XS Rating Curve= 0 ,0
Exp/Cntr=0.3,0.1

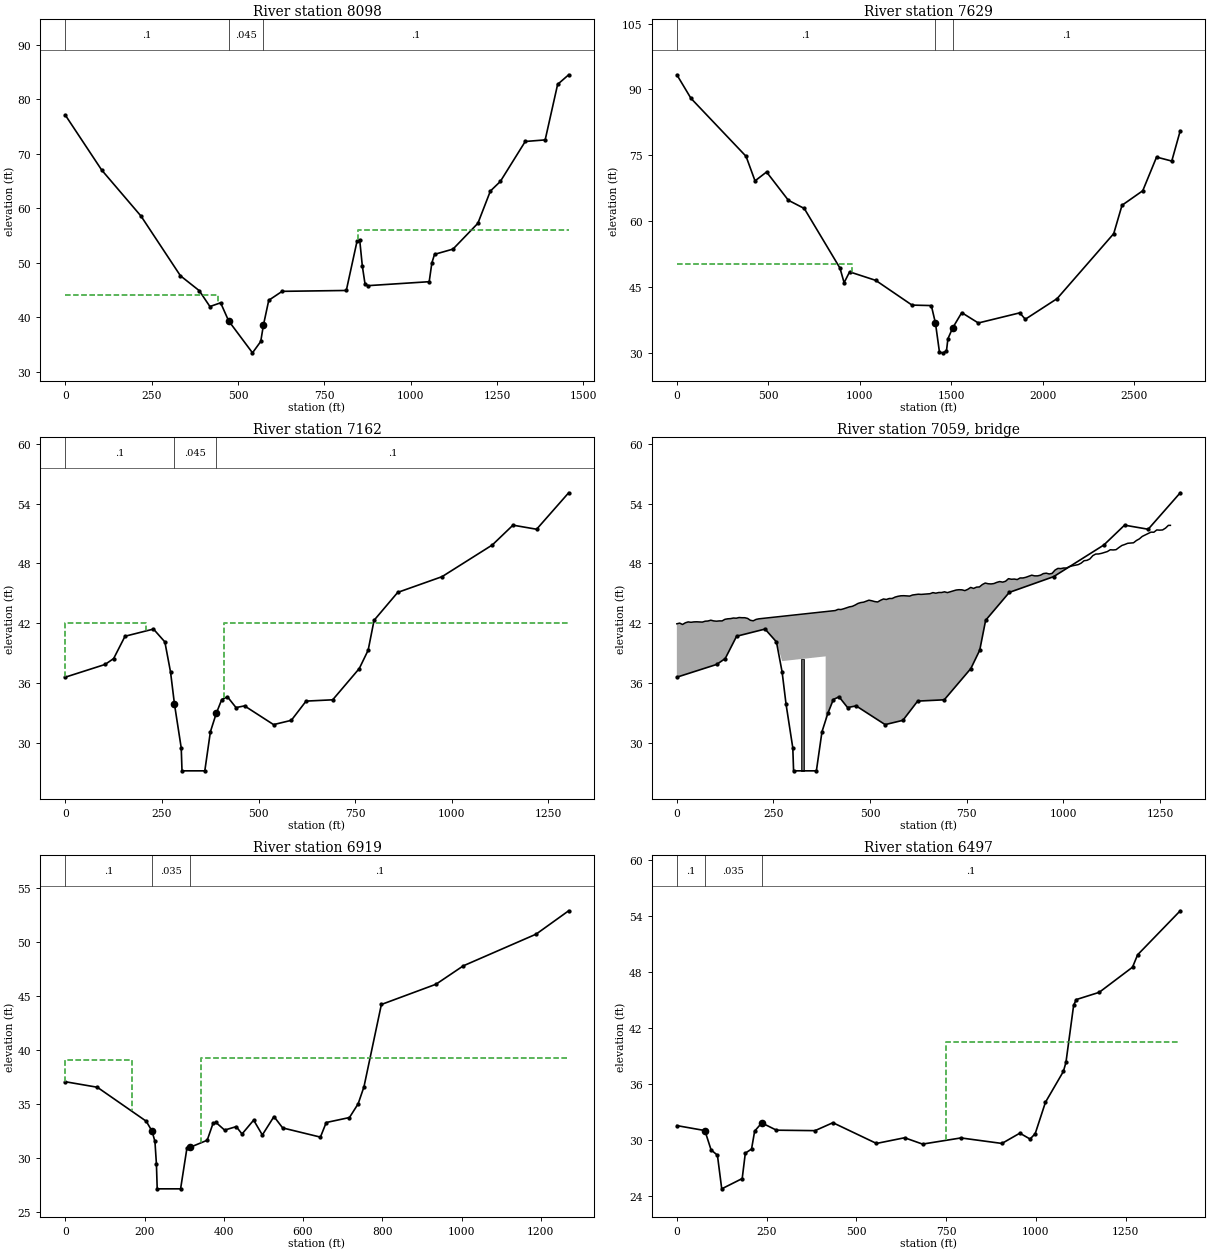
Type RM Length L Ch R = 1 ,8098    ,491.48,469.27,445.71
BEGIN DESCRIPTION:
edited with hec-2 data
END DESCRIPTION:
XS GIS Cut Line= 4
1610998.63457511711271.7109347131610788.13286823710993.234718338
1610114.96595149 710675.289431931609761.93704727710587.580387384
#Sta/Elev= 30
       0   77.08   105.3      67  219.37   58.53  333.45   47.58  387.79   44.86
  418.76   41.94  449.72   42.63  472.95   39.31     542  33.445  565.85   35.53
  573.59   38.52  589.07   43.09  627.78   44.73  813.58   44.89  844.54    53.9
  852.28   54.21  860.02   49.35  867.77   46.09  875.51   45.77 1053.56    46.5
  1061.3   49.96 1069.05   51.52 1122.41   52.48 1194.54   57.22  1230.6   63.13
 1259.45   64.89 1331.58   72.23 1389.28   72.52 1425.35   82.71 1457.32   84.47
#Mann= 3 , 0 , 0
       0      .1       0  472.95    .045       0  573.59      .1       0
#XS Ineff= 2 , 0
          443.24   44.04  848.65           56.07
Permanent Ineff=
       F       F
Bank Sta=472.95,573.59
XS Rating Curve= 0 ,0
Exp/Cntr=0.3,0.1

Type RM Length L Ch R = 1 ,7629    ,500.67,466.26,448.55
BEGIN DESCRIPTION:
edited with hec-2 data
END DESCRIPTION:
XS GIS Cut Line= 4
1611420.48414041711856.0514469151611403.40261084711160.165737182
  1611223.354929710695.8322429961609780.38889663 710112.97801435
#Sta/Elev= 30
       0   93.35   77.02   87.98  378.11   74.75  427.13   69.15  490.15   71.18
  609.18   64.73   696.1   62.86   891.3   49.25  913.82   45.93  943.85    48.4
  1086.5   46.46 1284.71   40.82  1390.4   40.71 1413.05   36.68    1435   30.03
    1454   29.93    1473   30.33 1480.99   33.14 1507.19   35.63 1556.49    39.1
 1647.08   36.74 1873.56   39.05 1903.76   37.59  2077.4   42.29 2386.93   57.12
 2432.23   63.59 2545.47    66.9 2620.97   74.58 2704.01   73.67 2750.35   80.59
#Mann= 3 , 0 , 0
       0      .1       0 1413.05    .045       0 1507.19      .1       0
#XS Ineff= 2 , 0
          956.08   50.26
Permanent Ineff=
       F       F
Bank Sta=1413.05,1507.19
XS Rating Curve= 0 ,0
Exp/Cntr=0.5,0.3

Type RM Length L Ch R = 1 ,7162    ,245.93,242.97,226.95
XS GIS Cut Line= 3
1611591.44502069710334.8751983941611115.35647014710179.865526229
1610381.43705373709857.263584152
#Sta/Elev= 30
       0   36.57  103.06   37.85  125.15   38.44   154.6   40.68  228.21    41.4
  257.66   40.11  272.38   37.08  282.49   33.87     300   29.47     302   27.17
     361   27.17  375.45   31.09  390.58   32.93  404.89   34.33  419.62    34.6
   441.7   33.52  463.79   33.69  538.92   31.81   584.8   32.24  623.03   34.17
  691.85    34.3  760.67   37.44  783.61   39.28   798.9   42.28  860.07   45.08
  974.77   46.66 1104.75   49.84 1158.28   51.83 1219.45   51.42 1302.38   55.08
#Mann= 3 , 0 , 0
       0      .1       0  282.49    .045       0  390.58      .1       0
#XS Ineff= 2 , 0
          208.11   41.98  411.49           41.98
Permanent Ineff=
       F       F
Bank Sta=282.49,390.58
XS Rating Curve= 0 ,0
Exp/Cntr=0.5,0.3

Type RM Length L Ch R = 3 ,7059    ,,,
BEGIN DESCRIPTION:
Pulaski Highway, CE042607PF-1, bridge data from HEC-2 model and survey
END DESCRIPTION:
Bridge Culvert--1,0,-1,-1, 0
Deck Dist Width WeirC Skew NumUp NumDn MinLoCord MaxHiCord MaxSubmerge Is_Ogee
85,115,2.6,0, 151, 142, , , 0.98, 0, 0,0,,
       0    7.32   14.64   21.96   29.28    36.6   43.92   51.24   58.56   65.88
    73.2   80.52   87.84   95.16  102.48   109.8  117.12  124.44  131.76  139.08
   146.4  153.72  161.04  168.36  175.68     183  190.32  197.64  204.96  212.28
     250     250     385     385  409.91  417.23  424.55  431.87  439.19  446.51
  453.83  461.15  468.47  475.79  483.11  490.43  496.92  504.44  511.96  519.49
  527.01  534.53  542.05  549.58   557.1  564.62  572.14  579.67  587.19  594.71
  602.23  609.76  617.28   624.8  632.32  639.85  647.37  654.89  662.42  669.94
  677.46  684.98  692.51  700.03  707.55  715.07   722.6  730.12  737.64  745.16
  752.69  760.21  767.73  775.25  782.78   790.3  797.82  805.34  812.87  820.39
  827.91  835.43  842.96  850.48     858  865.53  873.05  880.57  888.09  895.62
  903.14  910.66  918.18  925.71  933.23  940.75  948.27   955.8  963.32  970.84
  978.36  985.89  993.41 1000.93 1008.45 1015.98  1023.5 1031.02 1038.54 1046.07
 1053.59 1061.11 1068.63 1076.16 1083.68  1091.2 1098.73 1106.25 1113.77 1121.29
 1128.82 1136.34 1143.86 1151.38 1158.91 1166.43 1173.95 1181.47    1189 1196.52
 1204.04 1211.56 1219.09 1226.61 1234.13 1241.65 1249.18  1256.7 1264.22 1271.74
 1276.89
   41.93      42   41.86   42.03   42.12   42.08   42.12   42.13   42.12    42.1
   42.19   42.21   42.29   42.22   42.19   42.22   42.22   42.38   42.43   42.45
   42.51   42.49   42.56   42.54   42.54   42.47   42.28   42.23   42.37   42.43
   42.59   42.59   43.16   43.16   43.26   43.38   43.36   43.44   43.54   43.63
   43.68   43.81   43.97   44.06    44.1    44.2    44.3   44.24   44.16   44.12
   44.29   44.42   44.37   44.47   44.47   44.61   44.69   44.74   44.75   44.73
   44.71   44.82   44.86    44.9   44.88    44.9   44.93   44.95   45.06      45
   45.07   45.07   45.14   45.06   45.15   45.24   45.32   45.35   45.34   45.26
   45.39   45.58   45.48   45.61   45.63   45.87   46.02   45.95   45.93   45.97
   46.09   46.17   46.11    46.2   46.46    46.4   46.42   46.37   46.53   46.53
    46.6   46.71   46.81   46.74   46.74   46.81   46.97   47.01   46.93   46.99
   47.32   47.49   47.47   47.53   47.53   47.67   47.75   47.81   47.87   48.02
   48.26    48.3   48.44   48.77   48.93   48.94      49   49.09   49.18   49.36
   49.34   49.37   49.59   49.79   49.89   50.01   50.03   50.06   50.29   50.45
    50.7   50.84   50.97   51.13   51.12   51.35   51.33   51.35   51.53   51.81
   51.81
                                                                                
                                                                                
                                                                                
           38.09   38.66
                                                                                
                                                                                
                                                                                
                                                                                
                                                                                
                                                                                
                                                                                
                                                                                
                                                                                
                                                                                
                                                                                
        
       0    13.2   20.52   27.84   35.16   42.48    49.8   57.12   64.44   71.76
   79.08    86.4   93.72  101.04  108.36  115.68     123  130.32  137.64  144.96
  152.28     190     190     325     325  349.91  357.23  364.55  371.87  379.19
  386.51  393.83  401.15  408.47  415.79  423.11  430.43  436.92  444.44  451.96
  459.49  467.01  474.53  482.05  489.58   497.1  504.62  512.14  519.67  527.19
  534.71  542.23  549.76  557.28   564.8  572.32  579.85  587.37  594.89  602.42
  609.94  617.46  624.98  632.51  640.03  647.55  655.07   662.6  670.12  677.64
  685.16  692.69  700.21  707.73  715.25  722.78   730.3  737.82  745.34  752.87
  760.39  767.91  775.43  782.96  790.48     798  805.53  813.05  820.57  828.09
  835.62  843.14  850.66  858.18  865.71  873.23  880.75  888.27   895.8  903.32
  910.84  918.36  925.89  933.41  940.93  948.45  955.98   963.5  971.02  978.54
  986.07  993.59 1001.11 1008.63 1016.16 1023.68  1031.2 1038.73 1046.25 1053.77
 1061.29 1068.82 1076.34 1083.86 1091.38 1098.91 1106.43 1113.95 1121.47    1129
 1136.52 1144.04 1151.56 1159.09 1166.61 1174.13 1181.65 1189.18  1196.7 1204.22
 1211.74 1216.89
    42.1   42.19   42.21   42.29   42.22   42.19   42.22   42.22   42.38   42.43
   42.45   42.51   42.49   42.56   42.54   42.54   42.47   42.28   42.23   42.37
   42.43   42.59   42.59   43.16   43.16   43.26   43.38   43.36   43.44   43.54
   43.63   43.68   43.81   43.97   44.06    44.1    44.2    44.3   44.24   44.16
   44.12   44.29   44.42   44.37   44.47   44.47   44.61   44.69   44.74   44.75
   44.73   44.71   44.82   44.86    44.9   44.88    44.9   44.93   44.95   45.06
      45   45.07   45.07   45.14   45.06   45.15   45.24   45.32   45.35   45.34
   45.26   45.39   45.58   45.48   45.61   45.63   45.87   46.02   45.95   45.93
   45.97   46.09   46.17   46.11    46.2   46.46    46.4   46.42   46.37   46.53
   46.53    46.6   46.71   46.81   46.74   46.74   46.81   46.97   47.01   46.93
   46.99   47.32   47.49   47.47   47.53   47.53   47.67   47.75   47.81   47.87
   48.02   48.26    48.3   48.44   48.77   48.93   48.94      49   49.09   49.18
   49.36   49.34   49.37   49.59   49.79   49.89   50.01   50.03   50.06   50.29
   50.45    50.7   50.84   50.97   51.13   51.12   51.35   51.33   51.35   51.53
   51.81   51.81
                                                                                
                                                                                
                   38.09   38.66
                                                                                
                                                                                
                                                                                
                                                                                
                                                                                
                                                                                
                                                                                
                                                                                
                                                                                
                                                                                
                                                                                
                
Pier Skew, UpSta & Num, DnSta & Num=  ,325, 2 ,255, 2 , 0 , 0 , 0 ,,
       6       6
      25      40
       6       6
      25      40
BR Coef=-1 , 1 , 0 ,, 0 ,,,0.8,-1,1.2,0,
WSPro=,,,, 1 ,,,, 0 ,,,, 0 ,,,,-1 ,-1 ,-1 , 0 , 0 , 0 , 0 , 0
BC Design=,, 0 ,, 0 ,,,,,,
BC Use User HTab Curves=0
BC User HTab FreeFlow(D)= 0

Type RM Length L Ch R = 1 ,6919    ,331.39,422.95,368.39
BEGIN DESCRIPTION:
edited with hec-2 data
END DESCRIPTION:
XS GIS Cut Line= 4
1611657.85905458710110.7278328241611470.21860698710050.824749008
1610837.75793304709855.6208379121610461.61837085709688.879273027
#Sta/Elev= 30
       0   37.07   80.83   36.56   204.3   33.42  218.95    32.5  226.27   31.55
     230   29.47     232   27.17     291   27.17  306.86    30.9  315.67   31.02
  358.14   31.66  372.79   33.21  380.12   33.31  402.09    32.6   431.4   32.92
  446.05   32.24  475.35   33.52  497.33   32.15  526.63   33.85  548.61    32.8
  643.85   31.95   658.5    33.3   717.1   33.76  739.08   35.03  753.73    36.6
  797.69   44.21  935.44   46.08 1004.35   47.78 1188.12   50.71 1270.31   52.87
#Mann= 3 , 0 , 0
       0      .1       0  218.95    .035       0  315.67      .1       0
#XS Ineff= 2 , 0
          167.12    39.1  342.12           39.27
Permanent Ineff=
       F       F
Bank Sta=218.95,315.67
XS Rating Curve= 0 ,0
Exp/Cntr=0.5,0.3

Type RM Length L Ch R = 1 ,6497    ,374.78,369.33,77.87
BEGIN DESCRIPTION:
edited with hec-2 data
END DESCRIPTION:
XS GIS Cut Line= 3
1611865.40291218709878.2787132411611583.45029072 709672.40332225
1610549.95378114709471.451692879
#Sta/Elev= 30
       0   31.54   78.01   31.01   95.34   28.94     113   28.37     125   24.77
     182   25.87  190.68   28.59  208.02   29.03  216.69   30.95  236.51   31.83
  277.36   31.05  384.77      31  434.69   31.85  555.92   29.63  634.36   30.24
  684.28   29.56  791.24   30.22  905.34   29.63  955.26   30.73  983.78    30.1
  998.05   30.68 1026.57   34.04 1076.49   37.34 1083.62    38.3 1105.01   44.41
 1112.14   45.03 1176.32   45.81 1269.03    48.5 1283.29   49.83 1401.97   54.54
#Mann= 3 , 0 , 0
       0      .1       0   78.01    .035       0  236.51      .1       0
#XS Ineff= 2 , 0
                          749.55           40.45
Permanent Ineff=
       F       F
Bank Sta=78.01,236.51
XS Rating Curve= 0 ,0
Exp/Cntr=0.3,0.1

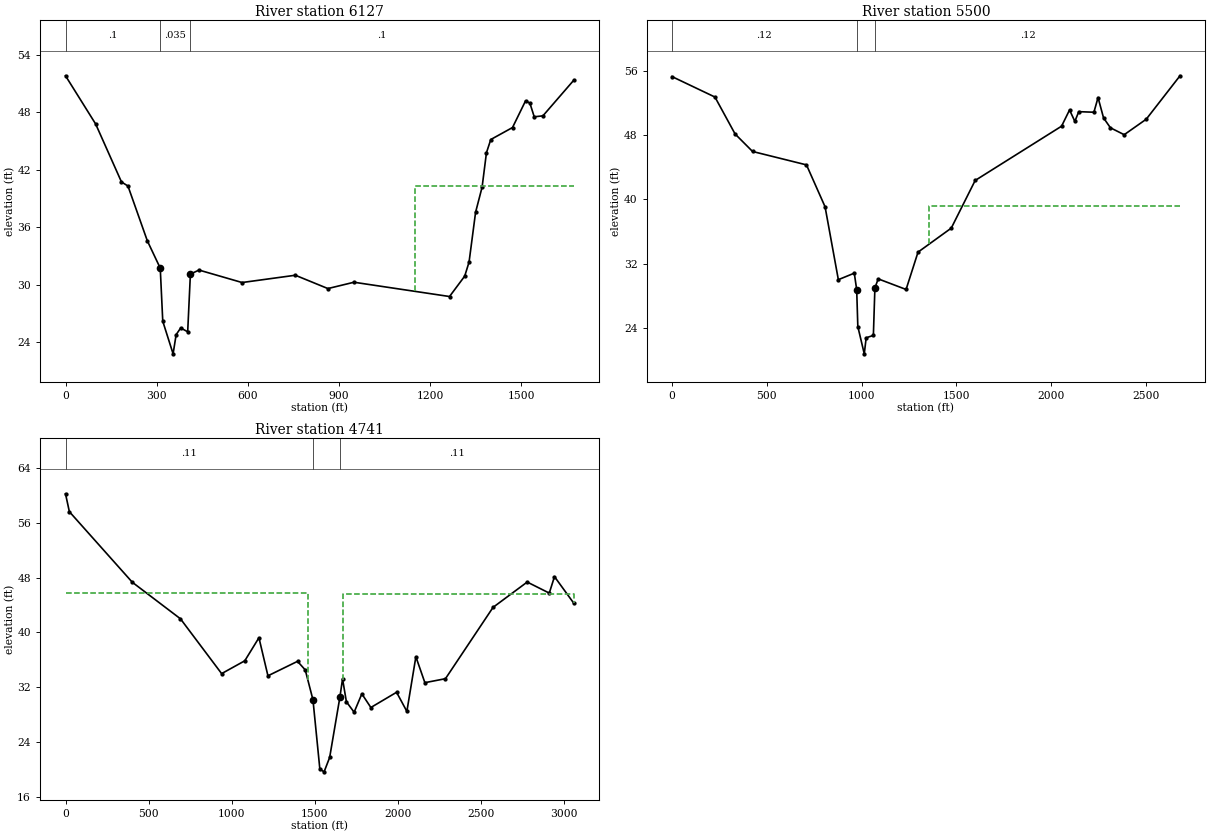
Type RM Length L Ch R = 1 ,6127    ,567.74,626.99,425.35
BEGIN DESCRIPTION:
edited with hec-2 data
END DESCRIPTION:
XS GIS Cut Line= 3
1612242.50421104709485.1233441681611558.92164646709591.762224272
1610599.17172576709394.890445665
#Sta/Elev= 30
       0   51.78   99.19   46.75   184.2    40.7  205.46   40.28  269.22   34.56
  311.73   31.71     320   26.17     354   22.77     364   24.77     379   25.47
     402   25.07  410.91   31.09  439.25   31.51  580.94   30.21  756.16   30.97
  863.35   29.58   949.1   30.24 1263.51   28.75 1313.53   30.88 1327.82   32.35
 1349.26   37.54  1370.7   40.16 1384.99   43.75 1399.28   45.13 1470.74   46.38
 1513.61   49.16  1527.9   48.93 1542.19    47.5 1570.78    47.6 1671.58   51.29
#Mann= 3 , 0 , 0
       0      .1       0  311.73    .035       0  410.91      .1       0
#XS Ineff= 2 , 0
                         1149.32           40.25
Permanent Ineff=
       F       F
Bank Sta=311.73,410.91
XS Rating Curve= 0 ,0
Exp/Cntr=0.3,0.1

Type RM Length L Ch R = 1 ,5500    ,548.4,759.68,763.69
BEGIN DESCRIPTION:
edited with hec-2 data
END DESCRIPTION:
XS GIS Cut Line= 5
 1612431.8408699709211.3507690281611820.73795919709117.848684326
1611022.63087906709137.884845346 1610295.0499424709172.902109683
1609780.38889663709031.025319994
#Sta/Elev= 30
       0   55.31  226.61   52.76  332.83   48.16  424.89   45.98  709.24   44.31
  807.27   39.09   877.3   30.01  961.32   30.82     974   28.77     980   24.17
    1014   20.77    1024   22.77    1062   23.07    1070   28.97 1087.36   30.11
 1234.41   28.79 1297.43   33.44 1472.64   36.43 1598.78   42.37 2054.31   49.13
 2096.35   51.15 2124.39   49.73 2144.99   50.94 2224.86   50.87 2246.65    52.7
 2275.69   50.16    2312   48.93 2384.61   48.07 2500.79      50 2678.86   55.41
#Mann= 3 , 0 , 0
       0     .12       0     974    .035       0    1070     .12       0
#XS Ineff= 2 , 0
                         1354.72           39.18
Permanent Ineff=
       F       F
Bank Sta=974,1070
XS Rating Curve= 0 ,0
Exp/Cntr=0.5,0.3

Type RM Length L Ch R = 1 ,4741    ,142.33,171.82,150.3
BEGIN DESCRIPTION:
edited with hec-2 data
END DESCRIPTION:
XS GIS Cut Line= 4
1612816.58858709709224.0212994961612442.53982927709049.024366409
  1610381.443039708077.924699783 1610054.6306515707916.074756622
#Sta/Elev= 30
       0   60.21   23.18    57.6  401.87   47.31  691.53   41.98  939.15   33.99
 1078.43   35.86 1163.55   39.22 1217.72   33.67 1395.69   35.78 1442.12   34.53
 1488.55   30.17    1530   20.07  1555.5   19.67    1589   21.77 1651.05   30.63
 1666.52   33.22 1689.74   29.88 1736.17   28.36 1782.59   31.04 1836.76   29.05
 1991.52   31.27 2053.42   28.48 2107.59   36.45 2161.76   32.67 2285.57   33.25
 2571.87   43.65 2777.29   47.34 2910.08   45.73 2941.33   48.13 3056.06    44.3
#Mann= 3 , 0 , 0
       0     .11       0 1488.55    .035       0 1651.05     .11       0
#XS Ineff= 2 , 0
         1458.33   45.73 1667.23           45.62
Permanent Ineff=
       F       F
Bank Sta=1488.55,1651.05
XS Rating Curve= 0 ,0
Exp/Cntr=0.5,0.3