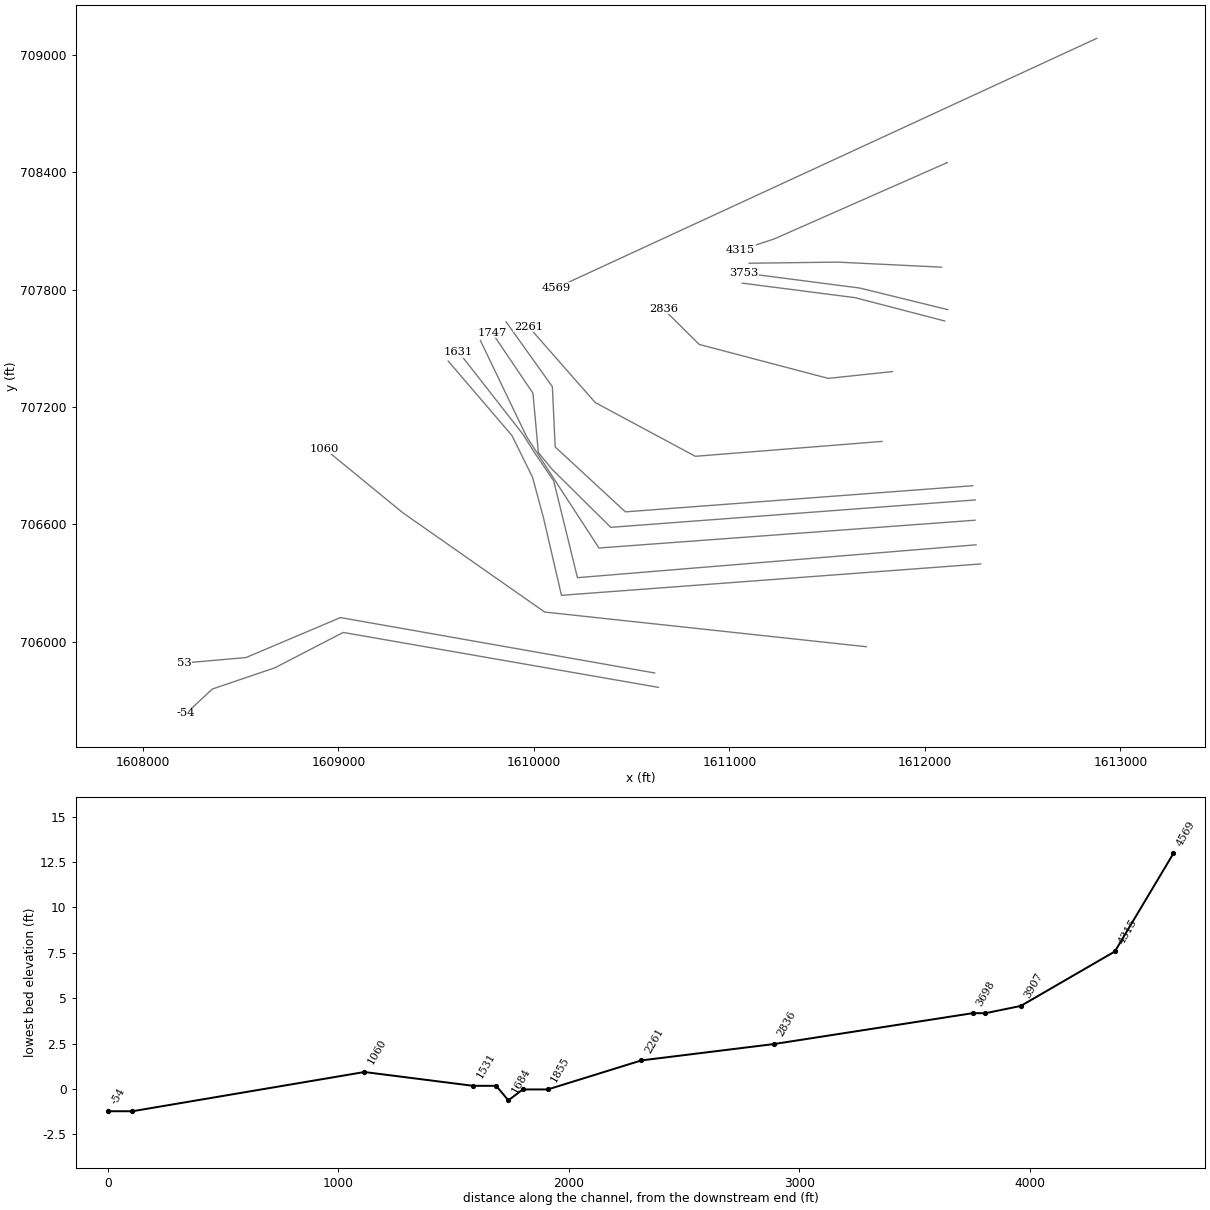
HEC-RAS study NortheastCreek.prj: Northeast Creek

--- NortheastCreek.g04 (geometry) --- (continued)

Type RM Length L Ch R = 3 ,4660    ,,,
BEGIN DESCRIPTION:
Conrail Railroad Bridge, CE042607FS-4, edited using HEC-2 and survey data
END DESCRIPTION:
Bridge Culvert--1,0,-1,-1, 0
Deck Dist Width WeirC Skew NumUp NumDn MinLoCord MaxHiCord MaxSubmerge Is_Ogee
45,60,2.6,0, 60, 60, , , 0.98, 0, 0,0,,
       0  239.51  656.72  672.17   857.6  880.78  973.49  988.95 1066.21 1089.39
 1282.54 1413.89 1437.06 1491.15    1500  1500.1  1508.5    1517  1525.5    1534
    1541    1550    1559    1568    1577    1583  1591.5    1600  1608.5  1616.9
    1617 1661.12 1730.66 1777.02 1792.47 1823.37 1892.91 1923.82  1977.9 2001.08
 2039.71 2055.16 2109.24  2155.6 2348.75 2418.29 2456.92 2495.55 2503.27 2518.72
    2704 2735.32 2750.99 2797.98 2821.47 2844.97 2946.78 2970.27 3040.75 3048.18
   57.91   56.36   54.46   54.06   52.89   53.15   52.51   52.07   51.86   51.35
   51.09   50.09    49.5   49.49   49.49   49.49   49.49   49.49   49.49   49.49
   49.48   49.48   49.48   49.48   49.47   49.47   49.46   49.46   49.46   49.45
   49.45   48.67   48.02   48.24   47.68   48.09   47.71   47.16   47.32   46.87
   46.94   46.45   46.78   46.29   46.17   45.62   45.91   45.58   45.95   45.43
   44.83   44.21   44.54   44.12   44.41   43.94   44.07    43.6   43.35    43.4
                                                                                
                                   20.07   32.67   39.17   41.17   39.17   32.67
   32.67   39.17   41.17   39.17   32.67   32.67   39.17   41.17   39.17   32.67
   24.97
                                                                                
                                                                                
       0  239.51  656.72  672.17   857.6  880.78  973.49  988.95 1066.21 1089.39
 1282.54 1413.89 1437.06 1491.15    1500  1500.1  1508.5    1517  1525.5    1534
    1541    1550    1559    1568    1577    1583  1591.5    1600  1608.5  1616.9
    1617 1661.12 1730.66 1777.02 1792.47 1823.37 1892.91 1923.82  1977.9 2001.08
 2039.71 2055.16 2109.24  2155.6 2348.75 2418.29 2456.92 2495.55 2503.27 2518.72
    2704 2735.32 2750.99 2797.98 2821.47 2844.97 2946.78 2970.27 3040.75 3048.18
   57.91   56.36   54.46   54.06   52.89   53.15   52.51   52.07   51.86   51.35
   51.09   50.09    49.5   49.49   49.49   49.49   49.49   49.49   49.49   49.49
   49.48   49.48   49.48   49.48   49.47   49.47   49.46   49.46   49.46   49.45
   49.45   48.67   48.02   48.24   47.68   48.09   47.71   47.16   47.32   46.87
   46.94   46.45   46.78   46.29   46.17   45.62   45.91   45.58   45.95   45.43
   44.83   44.21   44.54   44.12   44.41   43.94   44.07    43.6   43.35    43.4
                                                                                
                                   20.07   32.67   39.17   41.17   39.17   32.67
   32.67   39.17   41.17   39.17   32.67   32.67   39.17   41.17   39.17   32.67
   24.97
                                                                                
                                                                                
Pier Skew, UpSta & Num, DnSta & Num=  ,1537.5, 2 ,1537.5, 2 , 0 , 0 , 0 ,,
       7       7
      15   32.67
       7       7
      15   32.67
Pier Skew, UpSta & Num, DnSta & Num=  ,1580, 2 ,1580, 2 , 0 , 0 , 0 ,,
       6       6
      15   32.67
       6       6
      15   32.67
BR Coef=-1 , 1 , 0 ,, 0 ,,,0.8,-1,2,0,
WSPro=,,,, 1 ,,,, 0 ,,,, 0 ,,,,-1 ,-1 ,-1 , 0 , 0 , 0 , 0 , 0
BC Design=,, 0 ,, 0 ,,,,,,
BC Use User HTab Curves=0
BC User HTab FreeFlow(D)= 0

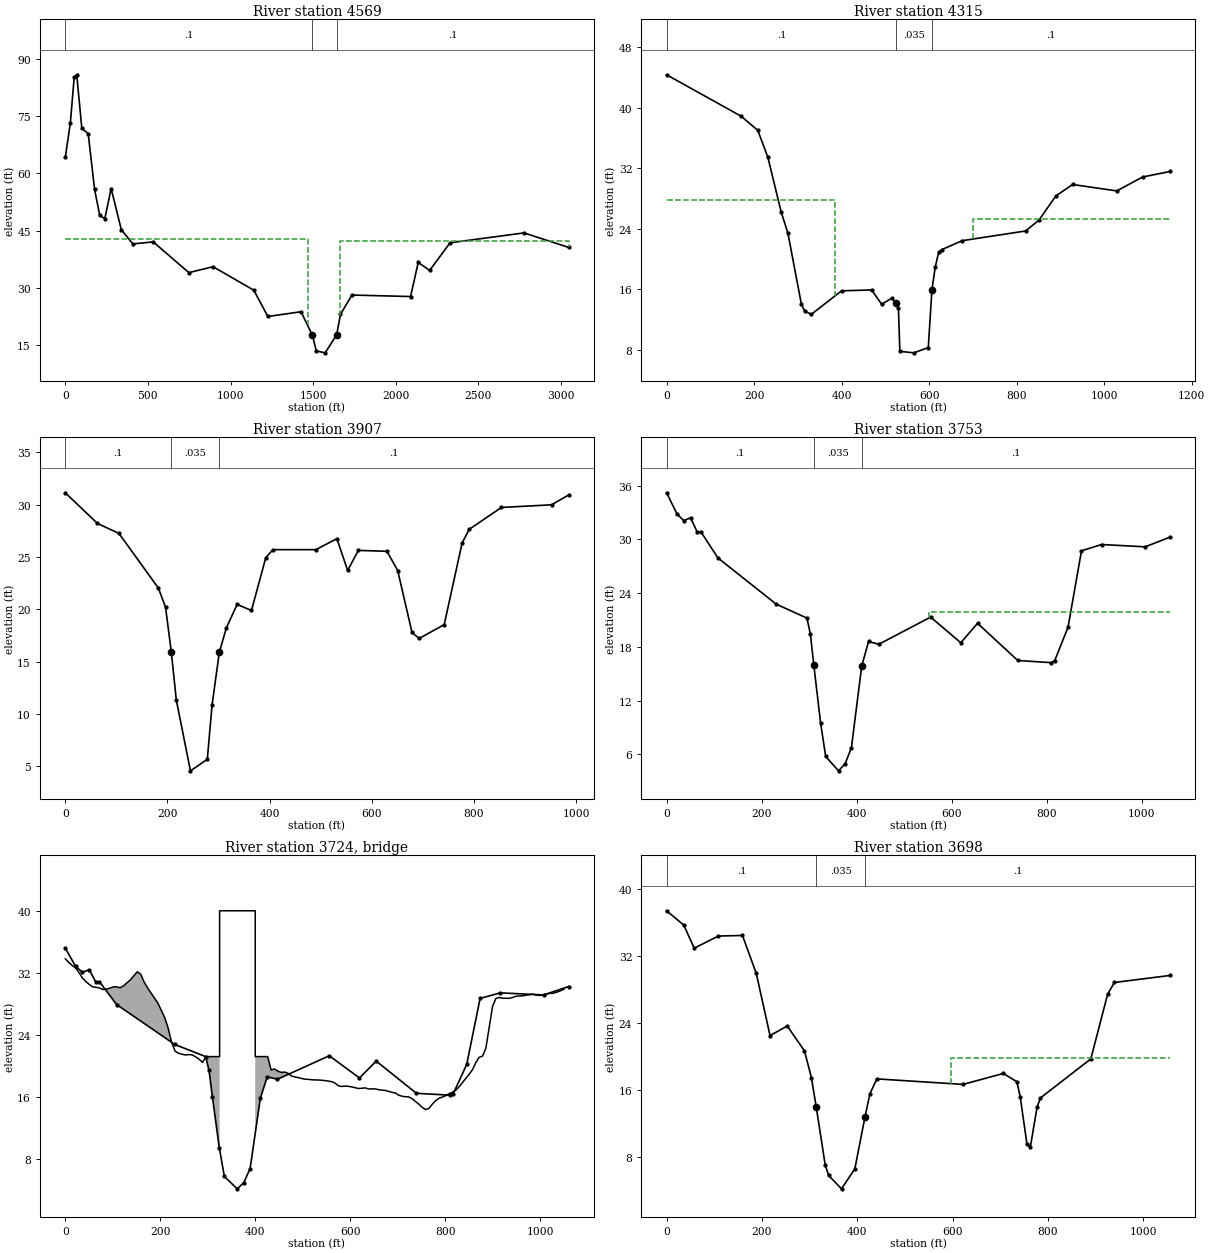
Type RM Length L Ch R = 1 ,4569    ,260.99,254.05,258.42
BEGIN DESCRIPTION:
edited with hec-2 data
END DESCRIPTION:
XS GIS Cut Line= 2
1612878.91048408 709085.744590611610113.37630624707808.794889227
#Sta/Elev= 30
       0   64.18   30.84   73.27   53.97   85.17   69.39   85.86  100.23   71.81
  138.78   70.42  177.33   55.81  208.17   49.08  239.02   48.08  277.57   56.04
  339.25   45.24  408.64   41.52     532   42.06  747.89   33.99  894.38   35.55
 1141.11   29.38 1225.92    22.5 1426.39   23.74 1495.78   17.56 1518.91   13.47
 1572.88   12.97 1642.27   17.73  1665.4   23.06 1734.79   28.12 2089.46   27.73
 2135.72   36.66 2205.12   34.58 2328.48   41.82 2775.67   44.41 3046.12   40.61
#Mann= 3 , 0 , 0
       0      .1       0 1495.78    .035       0 1642.27      .1       0
#XS Ineff= 2 , 0
         1466.22   42.81 1663.29           42.36
Permanent Ineff=
       F       F
Bank Sta=1495.78,1642.27
XS Rating Curve= 0 ,0
Exp/Cntr=0.5,0.3

Type RM Length L Ch R = 1 ,4315    ,401.29,407.81,230.76
BEGIN DESCRIPTION:
edited with hec-2 data
END DESCRIPTION:
XS GIS Cut Line= 4
1612112.38496952708450.5786607711612114.22234622708450.287176803
1611228.67959303708059.6065509021611057.14715648708003.104398265
#Sta/Elev= 30
       0   44.37  170.18   38.89  208.44   37.01  231.39   33.45  261.99   26.17
  277.29   23.38   307.9   14.03  315.55   13.08  330.85   12.67  399.71   15.78
  468.57   15.89  491.52      14  514.47    14.8  524.91   14.11  529.78   13.44
     533    7.77     565    7.57     598    8.27  606.29   15.91  613.94   18.93
  621.59   20.85  629.24   21.24  675.14   22.41  820.51    23.7  851.12   25.15
  889.37   28.32  927.63   29.85 1028.71      29 1087.67   30.84 1150.35   31.57
#Mann= 3 , 0 , 0
       0      .1       0  524.91    .035       0  606.29      .1       0
#XS Ineff= 2 , 0
          385.14   27.85     700            25.3
Permanent Ineff=
       F       F
Bank Sta=524.91,606.29
XS Rating Curve= 0 ,0
Exp/Cntr=0.3,0.1

Type RM Length L Ch R = 1 ,3907    ,159.45,153.53,124.99
BEGIN DESCRIPTION:
edited with hec-2 data
END DESCRIPTION:
XS GIS Cut Line= 3
1612085.05142608707915.2875314061611554.02578689707941.109074101
 1611100.4647758707935.495695263
#Sta/Elev= 30
       0   31.12   63.07   28.19  105.12   27.24  182.22   22.02  196.23    20.2
  207.59    15.9  217.26   11.35     245    4.57     278    5.67  287.34   10.86
  301.58   15.91  315.37   18.23   336.4   20.46  364.43   19.88  392.46   24.93
  406.48   25.69  490.58   25.69  531.65   26.74  552.65    23.7  573.66   25.62
  629.66   25.53  650.66   23.69  678.66   17.78  692.67   17.21  741.67   18.53
  776.67   26.32  790.67   27.63  853.68   29.72  951.69   29.97  985.25   30.91
#Mann= 3 , 0 , 0
       0      .1       0  207.59    .035       0  301.58      .1       0
#XS Ineff= 2 , 0
                           650.9           22.55
Permanent Ineff=
       F       F
Bank Sta=207.59,301.58
XS Rating Curve= 0 ,0
Exp/Cntr=0.5,0.3

Type RM Length L Ch R = 1 ,3753    ,55.77,55.72,100.46
BEGIN DESCRIPTION:
edited with hec-2 data
END DESCRIPTION:
XS GIS Cut Line= 3
1612116.69888864707698.1296415181611665.87137425707808.648036987
 1611074.9809427707885.244944781
#Sta/Elev= 30
       0   35.19   21.62   32.85   36.04   32.08   50.45    32.4   64.87   30.76
   72.07   30.85  108.11   27.92  230.63   22.77   295.5   21.21  302.71   19.43
  309.91   15.99  324.33    9.47     335    5.77     362    4.17     376    4.97
  389.19    6.77  410.81   15.85  425.23    18.6  446.85   18.29  555.94   21.32
  619.47   18.46  654.76   20.63  739.46   16.48  810.05   16.24  817.11   16.45
  845.34    20.2  873.57   28.71  915.93   29.42 1007.69   29.16 1060.01   30.24
#Mann= 3 , 0 , 0
       0      .1       0  309.91    .035       0  410.81      .1       0
#XS Ineff= 2 , 0
                           552.7           21.87
Permanent Ineff=
       F       F
Bank Sta=309.91,410.81
XS Rating Curve= 0 ,0
Exp/Cntr=0.5,0.3

Type RM Length L Ch R = 3 ,3724    ,,,
BEGIN DESCRIPTION:
Rolling Mill Road, CE042607-PF3, Bridge Out, 75' width between abutments assumed
END DESCRIPTION:
Bridge Culvert--1,0,-1,-1, 0
Deck Dist Width WeirC Skew NumUp NumDn MinLoCord MaxHiCord MaxSubmerge Is_Ogee
15,20,2.6,0, 141, 141, , , 0.98, 0, 0,0,,
       0    7.22   14.45   21.67    28.9   36.12   43.34   50.57   57.79   65.02
   72.24   79.47   86.69   93.91  101.14  108.36  115.59  122.81  130.03  137.26
  144.48  151.71  158.93  166.15  173.38   180.6  187.83  195.05  202.28   209.5
  216.72  223.95  231.17   238.4  245.62  252.84  260.07  267.29  274.52  281.74
  288.97  296.19  303.41  310.64  317.86     325     325     400     400  404.55
  411.78     419  426.22  433.45  440.67   447.9  455.12  462.28  469.34  476.39
  483.45  490.51  497.56  504.62  511.67  518.73  525.79  532.84   539.9  546.95
  554.01  561.07  568.12  575.18  582.24  589.29  596.35   603.4  610.46  617.52
  624.57  631.63  638.68  645.74   652.8  659.85  666.91  673.97  681.02  688.08
  695.13  702.19  709.25   716.3  723.36  730.41  737.47  744.53  751.58  758.64
   765.7  772.75  779.81  786.86  793.92  800.98  808.03  815.09  822.14   829.2
  836.26  843.31  850.37  857.43  864.48  871.54  878.59  885.65  892.71  899.76
  906.82  913.87  920.93  927.99  935.04   942.1  949.16  956.21  963.27  970.32
  977.38  984.44  991.49  998.55  1005.6 1012.66 1019.72 1026.77 1033.83 1040.89
 1049.93
   33.81   33.36   32.96   32.65   32.04   31.34   30.89    30.5   30.19   30.14
   30.04   29.85   29.91   30.03    30.2    30.2   30.08   30.34   30.73   31.12
   31.63   32.14   31.83    30.8   30.06   29.41   28.78    28.1   27.15   26.23
   24.87   23.06   21.91   21.65   21.52   21.42   21.47   21.43   21.17   20.89
   20.46   21.21   21.21   21.21   21.21   21.21      40      40   21.21   21.21
   21.21   21.21   21.21   19.49   19.62   19.33   19.17   19.22   19.05   18.71
   18.59    18.5   18.39   18.29   18.28   18.23    18.2    18.2   18.16   18.12
   18.05   17.98   17.79   17.45   17.36   17.41   17.38    17.3    17.2    17.1
   17.13   17.18   17.03   17.06   17.05   16.95   16.89   16.85   16.72    16.6
   16.52   16.24    16.1   16.04   16.01    15.8   15.42   15.08   14.68   14.38
   14.53   15.07   15.53   15.83      16   16.17   16.44    16.6   16.88   17.31
   17.85   18.39   18.93   19.51   20.43   21.12   21.27   22.28      25   27.68
   28.71   28.82   28.73   28.72   28.72   28.83   28.99   29.01   29.04   29.12
   29.18   29.26   29.14   29.09   29.15   29.23   29.36   29.36   29.49   29.64
   29.87
                                                                                
                                                                                
                                                                                
                                                                                
                                               0      40      40       0
                                                                                
                                                                                
                                                                                
                                                                                
                                                                                
                                                                                
                                                                                
                                                                                
                                                                                
        
       0    7.22   14.45   21.67    28.9   36.12   43.34   50.57   57.79   65.02
   72.24   79.47   86.69   93.91  101.14  108.36  115.59  122.81  130.03  137.26
  144.48  151.71  158.93  166.15  173.38   180.6  187.83  195.05  202.28   209.5
  216.72  223.95  231.17   238.4  245.62  252.84  260.07  267.29  274.52  281.74
  288.97  296.19  303.41  310.64  317.86     325     325     400     400  404.55
  411.78     419  426.22  433.45  440.67   447.9  455.12  462.28  469.34  476.39
  483.45  490.51  497.56  504.62  511.67  518.73  525.79  532.84   539.9  546.95
  554.01  561.07  568.12  575.18  582.24  589.29  596.35   603.4  610.46  617.52
  624.57  631.63  638.68  645.74   652.8  659.85  666.91  673.97  681.02  688.08
  695.13  702.19  709.25   716.3  723.36  730.41  737.47  744.53  751.58  758.64
   765.7  772.75  779.81  786.86  793.92  800.98  808.03  815.09  822.14   829.2
  836.26  843.31  850.37  857.43  864.48  871.54  878.59  885.65  892.71  899.76
  906.82  913.87  920.93  927.99  935.04   942.1  949.16  956.21  963.27  970.32
  977.38  984.44  991.49  998.55  1005.6 1012.66 1019.72 1026.77 1033.83 1040.89
 1049.93
   33.81   33.36   32.96   32.65   32.04   31.34   30.89    30.5   30.19   30.14
   30.04   29.85   29.91   30.03    30.2    30.2   30.08   30.34   30.73   31.12
   31.63   32.14   31.83    30.8   30.06   29.41   28.78    28.1   27.15   26.23
   24.87   23.06   21.91   21.65   21.52   21.42   21.47   21.43   21.17   20.89
   20.46   21.21   21.21   21.21   21.21   21.21      40      40   21.21   21.21
   21.21   21.21   21.21   19.49   19.62   19.33   19.17   19.22   19.05   18.71
   18.59    18.5   18.39   18.29   18.28   18.23    18.2    18.2   18.16   18.12
   18.05   17.98   17.79   17.45   17.36   17.41   17.38    17.3    17.2    17.1
   17.13   17.18   17.03   17.06   17.05   16.95   16.89   16.85   16.72    16.6
   16.52   16.24    16.1   16.04   16.01    15.8   15.42   15.08   14.68   14.38
   14.53   15.07   15.53   15.83      16   16.17   16.44    16.6   16.88   17.31
   17.85   18.39   18.93   19.51   20.43   21.12   21.27   22.28      25   27.68
   28.71   28.82   28.73   28.72   28.72   28.83   28.99   29.01   29.04   29.12
   29.18   29.26   29.14   29.09   29.15   29.23   29.36   29.36   29.49   29.64
   29.87
                                                                                
                                                                                
                                                                                
                                                                                
                                               0      40      40       0
                                                                                
                                                                                
                                                                                
                                                                                
                                                                                
                                                                                
                                                                                
                                                                                
                                                                                
        
BR Coef=-1 , 0 , 0 ,, 0 ,,,0.8,-1,,0,
WSPro=,,,, 1 ,,,, 0 ,,,, 0 ,,,,-1 ,-1 ,-1 , 0 , 0 , 0 , 0 , 0
BC Design=,, 0 ,, 0 ,,,,,,
BC Use User HTab Curves=0
BC User HTab FreeFlow(D)= 0

Type RM Length L Ch R = 1 ,3698    ,861.55,861.9,537.2
BEGIN DESCRIPTION:
edited with hec-2 data
END DESCRIPTION:
XS GIS Cut Line= 3
1612101.35107279707639.9926687181611642.86386761707759.264996558
1611065.10433459707833.673421249
#Sta/Elev= 30
       0    37.4   36.16   35.68   57.86   32.93  108.49   34.38  159.13   34.45
  188.06   29.93  216.99   22.49  253.15   23.63  289.32   20.65  303.79   17.47
  313.82   14.01  332.72    7.04     340    5.77     367    4.17     395    6.57
  416.17   12.74  426.75   15.56  441.21   17.31  621.96   16.65  706.65   17.96
  734.89   16.97  741.94   15.18  756.06    9.54  763.12    9.12  777.23    13.9
  784.29   15.03  890.16    19.7  925.45   27.44  939.56   28.83 1056.28   29.67
#Mann= 3 , 0 , 0
       0      .1       0  313.82    .035       0  416.17      .1       0
#XS Ineff= 2 , 0
                           597.3           19.78
Permanent Ineff=
       F       F
Bank Sta=313.82,416.17
XS Rating Curve= 0 ,0
Exp/Cntr=0.5,0.3

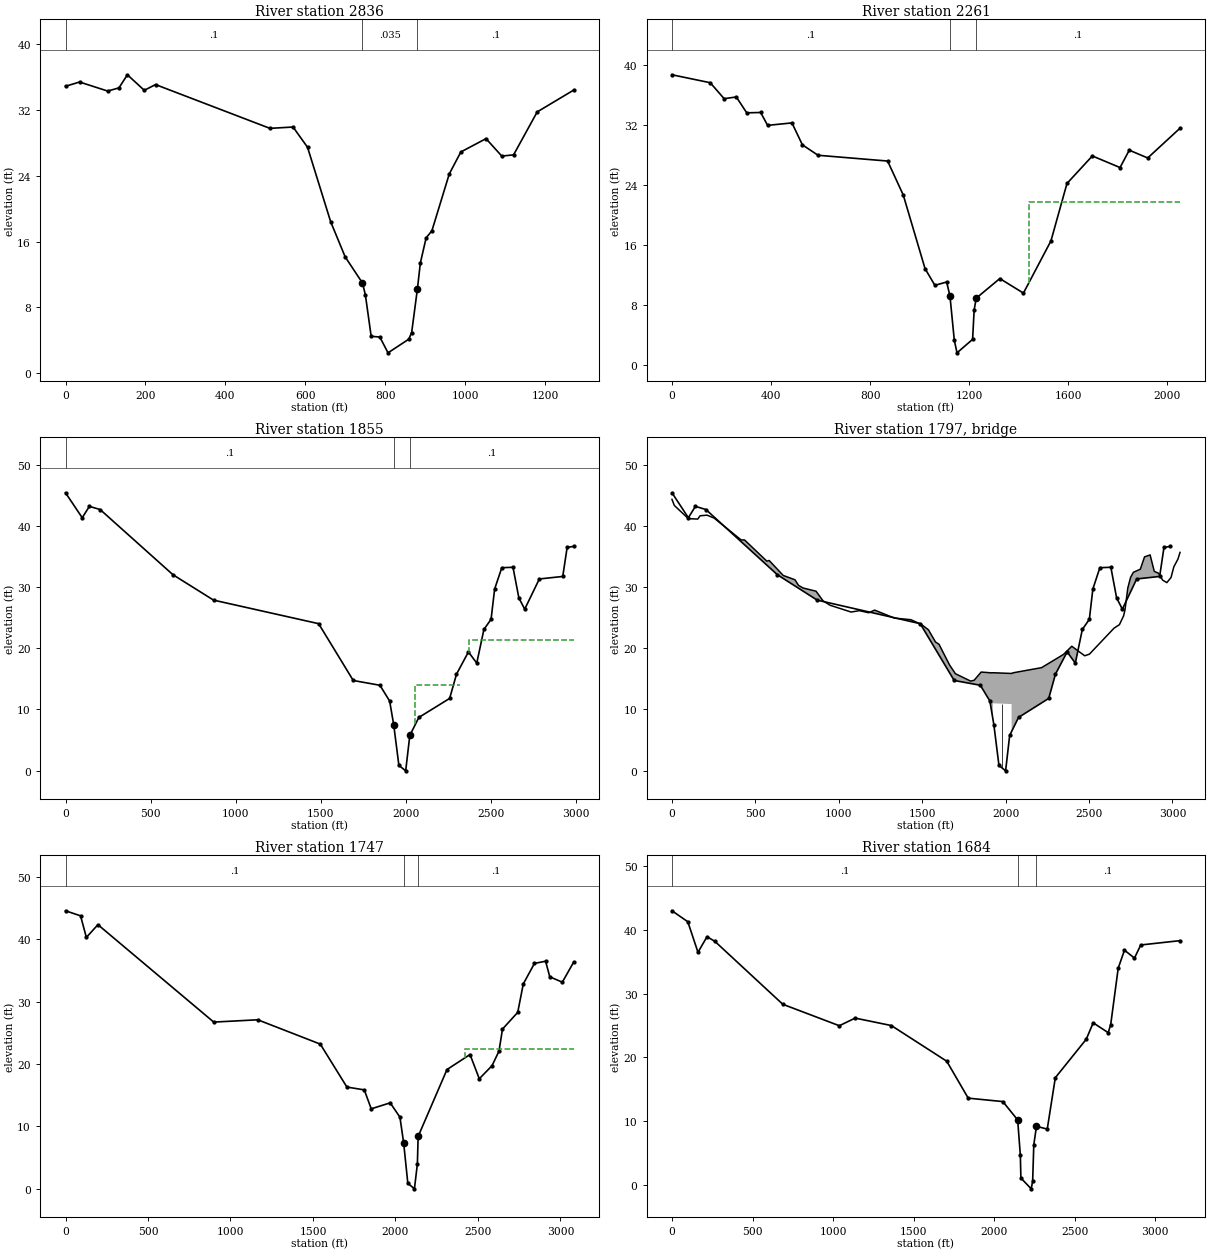
Type RM Length L Ch R = 1 ,2836    ,582.1,574.58,586.39
BEGIN DESCRIPTION:
edited with hec-2 data
END DESCRIPTION:
XS GIS Cut Line= 4
1611834.09539984707381.3813970831611505.37425044707346.425392181
1610845.55808264707520.0612259061610661.97998093707701.959973171
#Sta/Elev= 30
       0   34.86    35.2   35.38  105.59   34.28  133.75   34.67  154.87   36.26
  197.11   34.37  225.26   35.07  511.53   29.75  569.44   29.91  605.63   27.45
  663.54    18.4  699.73   14.14  743.16   10.95   750.4    9.51  764.87    4.48
  786.59    4.39     807    2.47  858.97    4.13  866.21    4.94  880.69   10.28
  887.93   13.39   902.4   16.44  916.88   17.31  960.31   24.21  989.26   26.88
 1052.27    28.5 1091.69   26.38 1121.25   26.53 1180.38   31.75 1271.29   34.39
#Mann= 3 , 0 , 0
       0      .1       0  743.16    .035       0  880.69      .1       0
Bank Sta=743.16,880.69
XS Rating Curve= 0 ,0
Exp/Cntr=0.3,0.1

Type RM Length L Ch R = 1 ,2261    ,419.78,406.51,371.28
BEGIN DESCRIPTION:
edited with hec-2 data
END DESCRIPTION:
XS GIS Cut Line= 4
1611780.66563715707024.0698591021610825.35479356706947.997625381
1610313.64033322707222.8072433771609972.49735837707611.331186324
#Sta/Elev= 30
       0   38.67  154.49   37.61  210.66   35.48  259.82   35.71  301.95   33.59
  358.13   33.64  386.22   31.92  484.53   32.25  526.66   29.32  589.86   27.93
  870.75   27.16  933.95   22.63  1021.9   12.81 1061.63   10.58  1109.3   11.02
 1122.69    9.12    1140    3.27    1151    1.57    1214    3.37 1220.15    7.26
 1228.48    8.86 1323.83   11.48 1419.18    9.54 1530.41   16.51 1595.06   24.17
 1697.53   27.84 1809.32   26.29 1846.58   28.61  1921.1   27.57 2051.52   31.54
#Mann= 3 , 0 , 0
       0      .1       0 1122.69    .035       0 1228.48      .1       0
#XS Ineff= 2 , 0
                         1441.44           21.72
Permanent Ineff=
       F       F
Bank Sta=1122.69,1228.48
XS Rating Curve= 0 ,0
Exp/Cntr=0.5,0.3

Type RM Length L Ch R = 1 ,1855    ,122.57,108.11,100.12
BEGIN DESCRIPTION:
edited with hec-2 data
END DESCRIPTION:
XS GIS Cut Line= 5
 1612244.4544286 706797.455418111610467.67978527706663.815312058
 1610108.6801901706995.728243545 1610094.3203726707304.005297363
1609857.41553023 707635.67207785
#Sta/Elev= 30
       0   45.43   98.28   41.35   140.4   43.21  203.57   42.69  631.78   32.03
  870.45   27.88 1488.19   24.03 1691.77   14.74 1848.53   13.96 1905.73   11.38
 1929.55    7.51    1960     .87    2000    -.03 2024.23    5.75 2077.33     8.7
 2258.46   11.81 2298.75   15.77 2368.83   19.41 2417.88   17.58 2459.92   23.09
 2501.97   24.74 2522.99    29.7 2565.04   33.18 2630.94   33.25 2665.35   28.25
 2699.76    26.4 2785.79   31.34 2923.42   31.75 2949.23   36.49 2986.92   36.67
#Mann= 3 , 0 , 0
       0      .1       0 1929.55    .035       0 2024.23      .1       0
#XS Ineff= 2 ,-1
 2057.43 2317.57   13.93 2371.62 2986.92   21.35
Permanent Ineff=
       F       F
Bank Sta=1929.55,2024.23
XS Rating Curve= 0 ,0
Exp/Cntr=0.5,0.3

Type RM Length L Ch R = 3 ,1797    ,,,
BEGIN DESCRIPTION:
Maudin Avenue, CE0426007PF-4, edited using HEC-2 and survey data
END DESCRIPTION:
Bridge Culvert--1,0,-1,-1, 0
Deck Dist Width WeirC Skew NumUp NumDn MinLoCord MaxHiCord MaxSubmerge Is_Ogee
20,50,2.6,0, 60, 60, , , 0.98, 0, 0,0,,
       0   14.04   98.29  154.45   168.5  210.62  252.74  414.22  435.28  568.68
  582.72  666.97  737.17  758.23  786.32  863.54  905.67  947.79 1074.16 1123.31
 1179.47 1214.58 1333.93 1432.22  1495.4 1537.53 1579.65 1600.71  1663.9    1699
 1790.27 1811.33 1853.45 1914.26 1923.61 2035.76  2045.1 2215.59 2347.45 2396.67
 2474.01 2502.13 2649.78 2682.23 2707.31 2715.67 2732.39 2749.11 2765.83 2807.63
 2832.72 2866.16 2891.24 2916.32  2941.4 2966.49 2991.57 3008.29 3033.37 3045.44
   44.35   43.36    41.2   41.13   41.67   41.77   41.29   37.73   37.71   34.25
   34.36   31.91   31.21    30.3   29.86   29.34   27.76   27.04   25.93   26.16
   25.81   26.25   24.94   24.68    23.9   23.02   21.04   20.66   17.28   15.85
   14.64   14.78   16.12   15.99   16.01   15.89      16   16.84   19.01   20.34
   18.78   19.04   23.29   23.87   25.31   26.29   29.85    31.6   32.43   32.94
   34.95   35.27   32.58   32.28   31.15   30.74   31.58   33.32   34.61   35.68
                                                                                
                                                                                
                                                                                
                                   11.01   10.89
                                                                                
                                                                                
     105  119.04  203.29  259.45   273.5  315.62  357.74  519.22  540.28  673.68
  687.72  771.97  842.17  863.23  891.32  968.54 1010.67 1052.79 1179.16 1228.31
 1284.47 1319.58 1438.93 1537.22  1600.4 1642.53 1684.65 1705.71  1768.9    1804
 1895.27 1916.33 1958.45 2019.26 2028.61 2140.76  2150.1 2320.59 2452.45 2501.67
 2579.01 2607.13 2754.78 2787.23 2812.31 2820.67 2837.39 2854.11 2870.83 2912.63
 2937.72 2971.16 2996.24 3021.32  3046.4 3071.49 3096.57 3113.29 3138.37 3150.44
   44.35   43.36    41.2   41.13   41.67   41.77   41.29   37.73   37.71   34.25
   34.36   31.91   31.21    30.3   29.86   29.34   27.76   27.04   25.93   26.16
   25.81   26.25   24.94   24.68    23.9   23.02   21.04   20.66   17.28   15.85
   14.64   14.78   16.12   15.99   16.01   15.89      16   16.84   19.01   20.34
   18.78   19.04   23.29   23.87   25.31   26.29   29.85    31.6   32.43   32.94
   34.95   35.27   32.58   32.28   31.15   30.74   31.58   33.32   34.61   35.68
                                                                                
                                                                                
                                                                                
                                   11.01   10.89
                                                                                
                                                                                
Pier Skew, UpSta & Num, DnSta & Num=  ,1980, 2 ,2100, 2 , 0 , 0 , 0 ,,
       2       2
      -1      15
       2       2
      -1      15
BR Coef=-1 , 1 , 0 ,, 0 ,,,0.8,0,1.2,0,
WSPro=,,,, 1 ,,,, 0 ,,,, 0 ,,,,-1 ,-1 ,-1 , 0 , 0 , 0 , 0 , 0
BC Design=,, 0 ,, 0 ,,,,,,
BC Use User HTab Curves=0
BC User HTab FreeFlow(D)= 0

Type RM Length L Ch R = 1 ,1747    ,107.61,62.63,28.3
BEGIN DESCRIPTION:
edited with hec-2 data
END DESCRIPTION:
XS GIS Cut Line= 6
1612257.41293393706724.6671884951610393.02607596706584.604738101
1610091.11368047706883.4046343271610022.63870305706967.442106098
1609994.99209993707270.7693457451609786.67886244707579.181151867
#Sta/Elev= 30
       0   44.56   91.26   43.75  126.36   40.29  196.55   42.33  898.52   26.71
 1165.27   27.08 1544.34   23.18  1705.8   16.29 1811.09   15.84 1853.21    12.8
 1968.13   13.76 2027.22   11.46 2049.77    7.34    2075     .87    2115    -.03
    2133    3.97 2137.54    8.37 2312.48    19.1 2452.03   21.51 2508.26   17.62
 2585.58   19.72 2627.75   22.06 2648.84   25.59  2741.2   28.27 2774.99   32.83
 2842.57   36.12 2910.14   36.47 2935.49   33.97 3011.51   33.11 3079.59   36.29
#Mann= 3 , 0 , 0
       0      .1       0 2049.77    .035       0 2137.54      .1       0
#XS Ineff= 2 , 0
                         2423.99           22.36
Permanent Ineff=
       F       F
Bank Sta=2049.77,2137.54
XS Rating Curve= 0 ,0
Exp/Cntr=0.5,0.3

Type RM Length L Ch R = 1 ,1684    ,125.17,53.06,7.2
BEGIN DESCRIPTION:
edited with hec-2 data
END DESCRIPTION:
XS GIS Cut Line= 4
1612256.26004602706621.0689430391610332.59272005 706478.92603685
1609963.02116396707047.4976597131609726.11632159 707540.25973323
#Sta/Elev= 30
       0   43.03   98.27   41.31  161.44   36.51  217.59   38.96  266.73   38.22
  687.87   28.35 1038.83   24.98 1137.09   26.18  1361.7   25.01 1705.63   19.41
    1839   13.61 2054.14   13.07 2145.98   10.19 2162.56    4.65    2166    1.07
    2230    -.63    2239     .57 2246.14    6.31 2262.86    9.19 2329.65    8.75
 2379.75   16.82 2571.77   22.86 2614.81   25.44 2708.01   23.89 2723.55   25.16
 2770.15   34.02 2808.98   36.84 2871.12    35.6 2909.96   37.66  3153.8   38.34
#Mann= 3 , 0 , 0
       0      .1       0 2145.98    .035       0 2262.86      .1       0
Bank Sta=2145.98,2262.86
XS Rating Curve= 0 ,0
Exp/Cntr=0.5,0.3

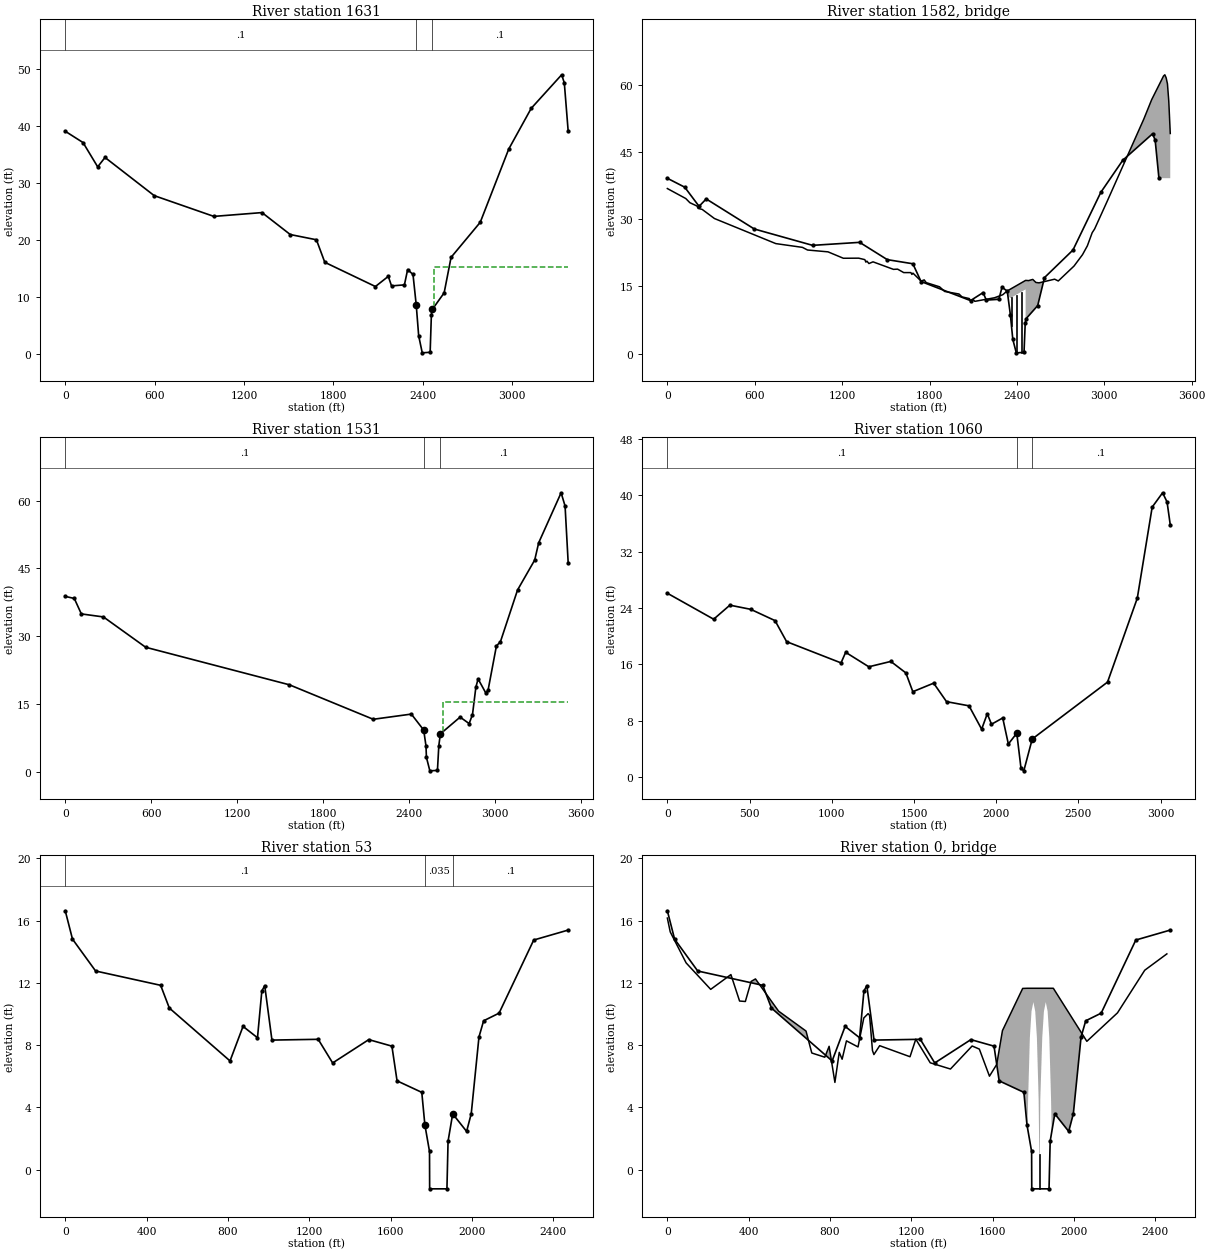
Type RM Length L Ch R = 1 ,1631    ,100.37,100.14,99.98
BEGIN DESCRIPTION:
edited with hec-2 data
END DESCRIPTION:
XS GIS Cut Line= 6
1612261.37436451706495.2189941561610222.68756455 706327.14405252
1610101.03583075706822.3529263881610004.56711738706964.299747467
1609942.55151598707062.1465852861609614.80113053707481.604930177
#Sta/Elev= 30
       0   39.13   119.4   37.14  217.74   32.87   266.9   34.52  597.02   27.81
  997.37   24.16 1320.47   24.83 1510.11   20.97  1685.7   20.05 1741.89   16.09
 2081.65   11.83 2168.15   13.62 2189.77   11.94 2276.27   12.12 2297.89   14.81
 2333.93   13.95 2355.56    8.59    2372    3.17    2396     .17    2449     .27
 2457.24    6.83 2463.68    7.81 2542.96   10.72 2589.39   16.96 2785.17   23.12
 2976.26   35.99 3127.28   43.16  3331.6   49.06 3349.37   47.65 3375.33   39.15
#Mann= 3 , 0 , 0
       0      .1       0 2355.56    .035       0 2463.68      .1       0
#XS Ineff= 2 , 0
       0                 2475.23       0   15.26
Permanent Ineff=
       F       F
Bank Sta=2355.56,2463.68
XS Rating Curve= 0 ,0
Exp/Cntr=0.5,0.3

Type RM Length L Ch R = 3 ,1582    ,,,
BEGIN DESCRIPTION:
North Main Street, CE042607FS-2, edited using HEC-2 and survey data
END DESCRIPTION:
Bridge Culvert--1,0,-1,-1, 0
Deck Dist Width WeirC Skew NumUp NumDn MinLoCord MaxHiCord MaxSubmerge Is_Ogee
20,50,2.6,0, 60, 60, , , 0.98, 0, 0,0,,
       0  126.47  154.57  203.75  210.78  238.88   323.2  744.75  927.43  962.56
 1103.08 1208.47 1313.86 1356.02 1363.04 1370.07 1384.12 1412.22 1552.74 1580.85
    1623 1672.19 1679.21 1686.24 1742.45 1763.52 1777.58 1868.91 1904.04 2002.41
 2023.49 2072.67 2086.72 2100.77 2111.01 2246.06 2302.92 2331.35 2338.46    2460
 2480.61 2509.04 2530.37 2551.69 2659.15 2684.12  2792.3 2850.55 2883.84 2917.13
 2933.77 3018.84 3271.47  3325.6  3406.8 3415.82 3424.84 3433.87 3442.89  3453.2
   36.84   34.61   33.68   32.93    32.4   32.19   30.15   24.55   23.71   23.12
   22.71   21.28    21.3   20.97   20.42   20.64    20.1   20.48    18.8   18.85
   18.08   18.08   17.67   17.96   16.18   16.45   15.84   14.91   13.87    13.3
   12.65   12.29    11.6   12.04   11.66   12.46   13.14   13.93   14.07   16.34
   16.29   16.56   15.88   15.79   16.61   16.21   19.54   22.08   24.05   26.99
   27.82   33.91   52.35   56.69   61.95   62.23   61.56   60.21   56.39   49.13
                                                                                
                                                                                
                                                                                
                                                                   12.07   14.34
                                                                                
                                                                                
     160  286.47  314.57  363.75  370.78  398.88   483.2  904.75 1087.43 1122.56
 1263.08 1368.47 1473.86 1516.02 1523.04 1530.07 1544.12 1572.22 1712.74 1740.85
    1783 1832.19 1839.21 1846.24 1902.45 1923.52 1937.58 2028.91 2064.04 2162.41
 2183.49 2232.67 2246.72 2260.77 2271.01 2406.06 2462.92 2491.35 2498.46    2620
 2640.61 2669.04 2690.37 2711.69 2819.15 2844.12  2952.3 3010.55 3043.84 3077.13
 3093.77 3178.84 3431.47  3485.6  3566.8 3575.82 3584.84 3593.87 3602.89  3613.2
   36.84   34.61   33.68   32.93    32.4   32.19   30.15   24.55   23.71   23.12
   22.71   21.28    21.3   20.97   20.42   20.64    20.1   20.48    18.8   18.85
   18.08   18.08   17.67   17.96   16.18   16.45   15.84   14.91   13.87    13.3
   12.65   12.29    11.6   12.04   11.66   12.46   13.14   13.93   14.07   16.34
   16.29   16.56   15.88   15.79   16.61   16.21   19.54   22.08   24.05   26.99
   27.82   33.91   52.35   56.69   61.95   62.23   61.56   60.21   56.39   49.13
                                                                                
                                                                                
                                                                                
                                                                   12.07   14.34
                                                                                
                                                                                
Pier Skew, UpSta & Num, DnSta & Num=  ,2363, 2 ,2523, 2 , 0 , 0 , 0 ,,
       2       2
      -5    13.5
       2       2
      -5    13.5
Pier Skew, UpSta & Num, DnSta & Num=  ,2397, 2 ,2557, 2 , 0 , 0 , 0 ,,
       2       2
      -5    13.5
       2       2
      -5    13.5
Pier Skew, UpSta & Num, DnSta & Num=  ,2431, 2 ,2591, 2 , 0 , 0 , 0 ,,
       2       2
      -5    14.5
       2       2
      -5    14.5
BR Coef=-1 , 1 , 0 ,, 0 ,,,0.8,0,1.2,0,
WSPro=,,,, 1 ,,,, 0 ,,,, 0 ,,,,-1 ,-1 ,-1 , 0 , 0 , 0 , 0 , 0
BC Design=,, 0 ,, 0 ,,,,,,
BC Use User HTab Curves=0
BC User HTab FreeFlow(D)= 0

Type RM Length L Ch R = 1 ,1531    ,295.27,471.18,562.14
BEGIN DESCRIPTION:
edited with hec-2 data
END DESCRIPTION:
XS GIS Cut Line= 6
1612285.76160109706397.3577614131610140.91366255706236.881584197
1610049.75603642 706629.872338311609992.62763086706841.507113427
1609887.45942971707054.4402613941609561.56784351707434.863507435
#Sta/Elev= 30
       0   38.78   63.18   38.32  112.31    34.9  266.74   34.23  561.57   27.52
 1565.36   19.21 2150.84   11.58 2416.71   12.73 2502.94     9.2 2519.07    5.67
    2522    3.17    2546     .17    2599     .27 2608.62    5.76 2619.52    8.35
 2757.27   12.06 2820.31   10.63 2843.73   12.62 2867.15   18.64 2882.77   20.51
 2937.42   17.36 2953.03    18.1 3010.95   27.83 3038.61   28.72 3158.43    40.2
 3278.26   46.83 3305.91   50.64  3462.6   61.71 3490.25   58.78 3511.88   46.25
#Mann= 3 , 0 , 0
       0      .1       0 2502.94    .035       0 2619.52      .1       0
#XS Ineff= 2 , 0
       0                 2635.14       0   15.34
Permanent Ineff=
       F       F
Bank Sta=2502.94,2619.52
XS Rating Curve= 0 ,0
Exp/Cntr=0.5,0.3

Type RM Length L Ch R = 1 ,1060    ,615.42,1006.14,1017.77
BEGIN DESCRIPTION:
edited with hec-2 data
END DESCRIPTION:
XS GIS Cut Line= 4
1611700.07248883705973.9427127991610054.80258752706151.373781219
1609328.94821931706659.4718380121608928.85205381706987.336897254
#Sta/Elev= 30
       0   26.09  281.62   22.41  380.19    24.4  506.92   23.81  654.77   22.21
  725.18   19.23 1056.09   16.22 1084.25   17.72 1225.06   15.67 1358.83   16.43
 1450.36    14.8  1492.6   12.14 1619.33   13.35 1697.53   10.73 1834.24   10.14
 1911.14    6.83 1945.32    9.02 1970.95    7.53 2039.31    8.42 2073.49    4.73
 2124.76    6.26 2150.39     1.3 2167.48     .93 2218.75    5.44 2676.58    13.5
 2857.58   25.39 2948.08   38.29 3011.43   40.32 3038.58   39.02  3058.1   35.77
#Mann= 3 , 0 , 0
       0      .1       0 2124.76    .035       0 2218.75      .1       0
Bank Sta=2124.76,2218.75
XS Rating Curve= 0 ,0
Exp/Cntr=0.5,0.3

Type RM Length L Ch R = 1 ,53      ,73.45,107.66,128.23
BEGIN DESCRIPTION:
edited with hec-2 data
END DESCRIPTION:
XS GIS Cut Line= 4
1610617.46285824705839.7103023831609010.52617268706123.014169708
1608527.51630022 705918.663839371608211.70215419705890.797884002
#Sta/Elev= 30
       0   16.64   35.54   14.82  149.27   12.77  469.12   11.85  511.77   10.39
  810.31    6.99  874.28    9.21  945.36    8.48  966.68   11.48   980.9   11.83
 1016.44    8.33 1243.89    8.38 1314.97    6.86 1492.67    8.36 1606.39    7.94
 1631.72    5.71 1753.33    4.97 1768.53    2.88 1791.33    1.17    1792   -1.23
    1877   -1.23 1882.54    1.83 1905.34    3.59 1973.75    2.46 1996.55     3.6
 2034.55    8.53 2057.36    9.57 2133.36   10.06 2303.74   14.76 2473.21    15.4
#Mann= 3 , 0 , 0
       0      .1       0 1768.53    .035       0 1905.34      .1       0
Bank Sta=1768.53,1905.34
XS Rating Curve= 0 ,0
Exp/Cntr=0.5,0.3

Type RM Length L Ch R = 3 ,0       ,,,
BEGIN DESCRIPTION:
West Cecil Avenue (State Route 7), CE042607PF-5, edited using HEC-2 and survey data
END DESCRIPTION:
Bridge Culvert--1,0,-1,-1, 0
Deck Dist Width WeirC Skew NumUp NumDn MinLoCord MaxHiCord MaxSubmerge Is_Ogee
33,35,2.6,0, 60, 60, , , 0.98, 0, 0,0,,
       0   14.21   92.34   213.1  312.54  355.16  383.58  411.99   433.3  546.95
  681.91  710.33  774.26  795.57  823.98  845.29   859.5  880.81  937.63  966.05
  987.36  994.46 1008.66 1015.77 1044.18 1193.35 1221.76  1292.8 1392.24 1498.79
 1534.31 1584.03 1619.55 1647.96 1747.39  1770.5 1771.02 1774.15 1782.66 1790.88
    1800 1809.12 1817.34 1825.85 1828.98 1832.02 1834.15 1843.66 1851.88    1861
 1870.12 1878.34 1886.85 1889.98  1890.5 1898.15  2062.9 2213.62 2347.65 2456.44
   16.17   15.28   13.29   11.59   12.54   10.84   10.81    12.1   12.26   10.19
    8.91     7.5    7.23    7.93    5.61    7.54     7.1    8.28    7.89    9.75
   10.03    9.92    7.66     7.4    7.97    7.26    8.39    6.87    6.47    7.95
    7.75    6.01    6.76    8.94   11.65   11.66   11.66   11.66   11.66   11.66
   11.66   11.66   11.66   11.66   11.66   11.66   11.66   11.66   11.66   11.66
   11.66   11.66   11.66   11.66   11.66   11.66    8.25   10.08   12.82   13.87
                                                                                
                                                                                
                                                                                
                                           -1.23    1.02    4.55    8.48   10.18
   10.77   10.18    8.48    4.55    1.02    1.02    4.55    8.48   10.18   10.77
   10.18    8.48    4.55    1.02   -1.23
      70   84.21  162.34   283.1  382.54  425.16  453.58  481.99   503.3  616.95
  751.91  780.33  844.26  865.57  893.98  915.29   929.5  950.81 1007.63 1036.05
 1057.36 1064.46 1078.66 1085.77 1114.18 1263.35 1291.76  1362.8 1462.24 1568.79
 1604.31 1654.03 1689.55 1717.96 1817.39  1840.5 1841.02 1844.15 1852.66 1860.88
    1870 1879.12 1887.34 1895.85 1898.98 1902.02 1904.15 1913.66 1921.88    1931
 1940.12 1948.34 1956.85 1959.98  1960.5 1968.15  2132.9 2283.62 2417.65 2526.44
   16.17   15.28   13.29   11.59   12.54   10.84   10.81    12.1   12.26   10.19
    8.91     7.5    7.23    7.93    5.61    7.54     7.1    8.28    7.89    9.75
   10.03    9.92    7.66     7.4    7.97    7.26    8.39    6.87    6.47    7.95
    7.75    6.01    6.76    8.94   11.65   11.66   11.66   11.66   11.66   11.66
   11.66   11.66   11.66   11.66   11.66   11.66   11.66   11.66   11.66   11.66
   11.66   11.66   11.66   11.66   11.66   11.66    8.25   10.08   12.82   13.87
                                                                                
                                                                                
                                                                                
                                           -1.23    1.02    4.55    8.48   10.18
   10.77   10.18    8.48    4.55    1.02    1.02    4.55    8.48   10.18   10.77
   10.18    8.48    4.55    1.02   -1.23
Pier Skew, UpSta & Num, DnSta & Num=  ,1830.5, 2 ,1900.5, 2 , 0 , 0 , 0 ,,
    3.04    3.04
      -2    1.02
    3.04    3.04
      -2    1.02
BR Coef=-1 , 0 , 0 ,, 0 ,,,0.8,-1,,0,
WSPro=,,,, 1 ,,,, 0 ,,,, 0 ,,,,-1 ,-1 ,-1 , 0 , 0 , 0 , 0 , 0
BC Design=,, 0 ,, 0 ,,,,,,
BC Use User HTab Curves=0
BC User HTab FreeFlow(D)= 0

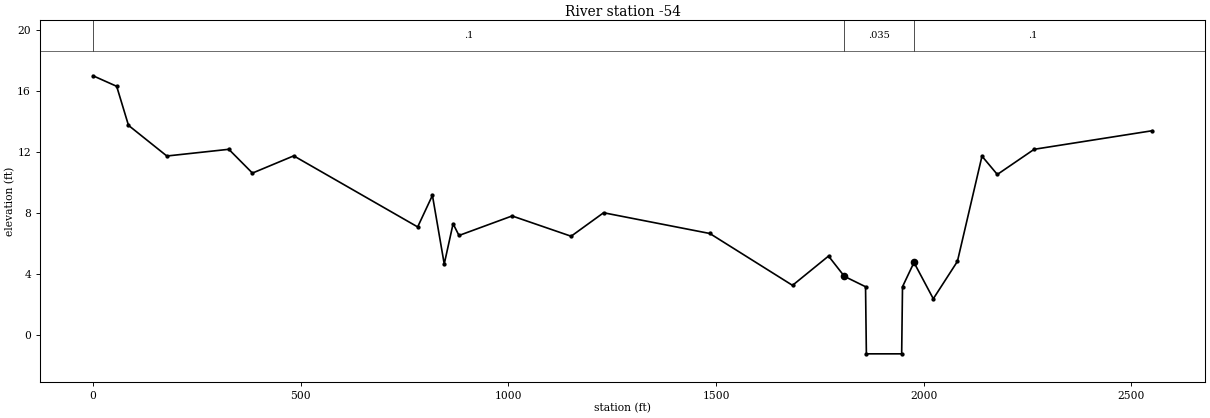
Type RM Length L Ch R = 1 ,-54     ,697.98,923.94,920.56
BEGIN DESCRIPTION:
edited with hec-2 data
END DESCRIPTION:
XS GIS Cut Line= 5
1610636.98637393705766.0775909721609024.39350514706047.019149795
1608675.79362492705866.4942112271608355.20623593705757.556749374
1608221.36878209705633.056791335
#Sta/Elev= 30
       0      17   56.84   16.31   85.27   13.75  177.64   11.74  326.85   12.18
  383.69   10.62  483.17   11.75   781.6    7.09  817.12    9.16  845.55    4.66
  866.86     7.3  881.07    6.53 1008.97    7.81 1151.08    6.48 1229.24    8.02
 1485.04    6.66 1684.18    3.26 1770.89    5.18 1809.05    3.85    1860    3.17
    1862   -1.23    1947   -1.23    1949    3.17 1976.64    4.76 2023.15    2.38
  2081.2    4.83 2140.35   11.73 2177.31   10.53 2266.03   12.18 2550.83    13.4
#Mann= 3 , 0 , 0
       0      .1       0 1809.05    .035       0 1976.64      .1       0
Bank Sta=1809.05,1976.64
XS Rating Curve= 0 ,0
Exp/Cntr=0.5,0.3