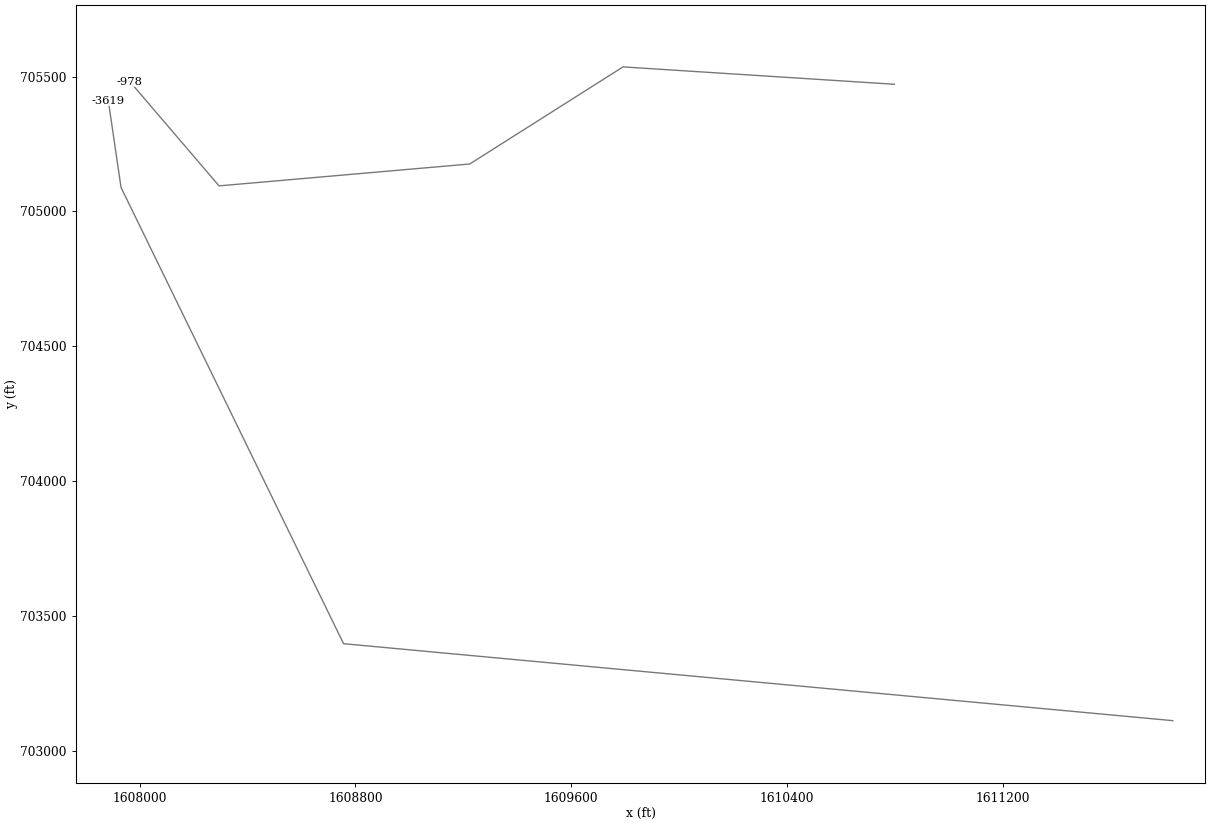
HEC-RAS study NortheastCreek.prj: Northeast Creek

--- NortheastCreek.g04 (geometry) --- (continued)

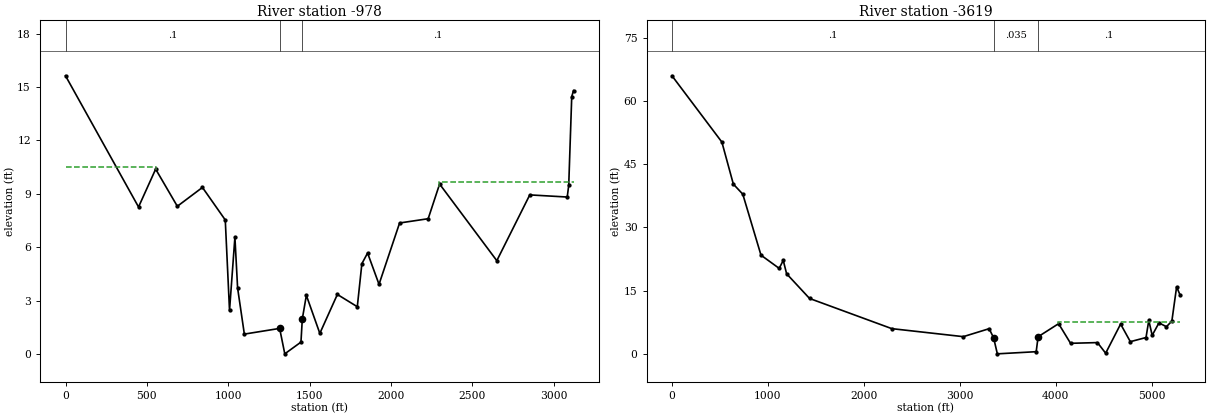
Type RM Length L Ch R = 1 ,-978    ,2806.72,2640.93,1747.23
XS GIS Cut Line= 5
1610798.53611532705471.6002778711609792.44967848705536.044761688
1609223.87805372705175.9493999631608294.29583825705094.810828179
1607963.77696529 705481.28546156
#Sta/Elev= 30
       0   15.64  448.92    8.26  554.13   10.39  687.41     8.3  841.72    9.36
  982.01    7.53 1008.15    2.44 1041.29    6.56 1057.86     3.7 1099.29    1.11
 1316.26    1.43 1347.86       0 1447.29     .66 1455.54    1.96 1480.44    3.29
 1563.29    1.15 1671.01    3.34 1793.58    2.65 1821.69    5.07 1856.82    5.67
 1927.09    3.91 2053.57    7.36 2229.23     7.6  2299.5    9.55 2651.11    5.24
 2853.75    8.94 3084.02    8.82 3093.23    9.49 3111.65   14.47  3122.8   14.81
#Mann= 3 , 0 , 0
       0      .1       0 1316.26    .035       0 1455.54      .1       0
#XS Ineff= 2 , 0
          555.74   10.49 2293.92            9.68
Permanent Ineff=
       F       F
Bank Sta=1316.26,1455.54
XS Rating Curve= 0 ,0
Exp/Cntr=0.3,0.1

Type RM Length L Ch R = 1 ,-3619   ,115.29,110.13,116.75
XS GIS Cut Line= 4
1611830.98421483 703111.718907521608756.08444013703397.084997147
1607930.79331629705089.0697457641607883.63232128705411.158898041
#Sta/Elev= 30
       0   66.02  520.23   50.28  639.74    40.3  738.16   37.91  927.97   23.43
 1117.78   20.29 1159.96   22.19 1195.11   19.01 1434.13   13.15  2291.8    5.98
 3036.98    4.08 3306.17    5.97  3352.9    3.82 3391.84       0 3796.84     .51
 3816.92    4.06 4030.49    7.16  4155.1     2.5 4435.47    2.67 4521.14     .15
  4676.9    7.07 4778.15    2.89  4941.7    3.87 4970.61    7.94 5005.98    4.39
 5076.73    7.35 5154.55    6.44 5211.15    7.78 5260.67    15.9 5296.13   14.01
#Mann= 3 , 0 , 0
       0      .1       0  3352.9    .035       0 3816.92      .1       0
#XS Ineff= 2 , 0
                         4020.27             7.6
Permanent Ineff=
       F       F
Bank Sta=3352.9,3816.92
XS Rating Curve= 0 ,0
Exp/Cntr=0.3,0.1
Stream Node=Northeast Creek ,Upper           , 0 , 0 ,Upstream end
Stream Node=Northeast Creek ,Upper           , 0 , 1 ,Downstream end

Chan Stop Cuts=-1
Use User Specified Reach Order=0