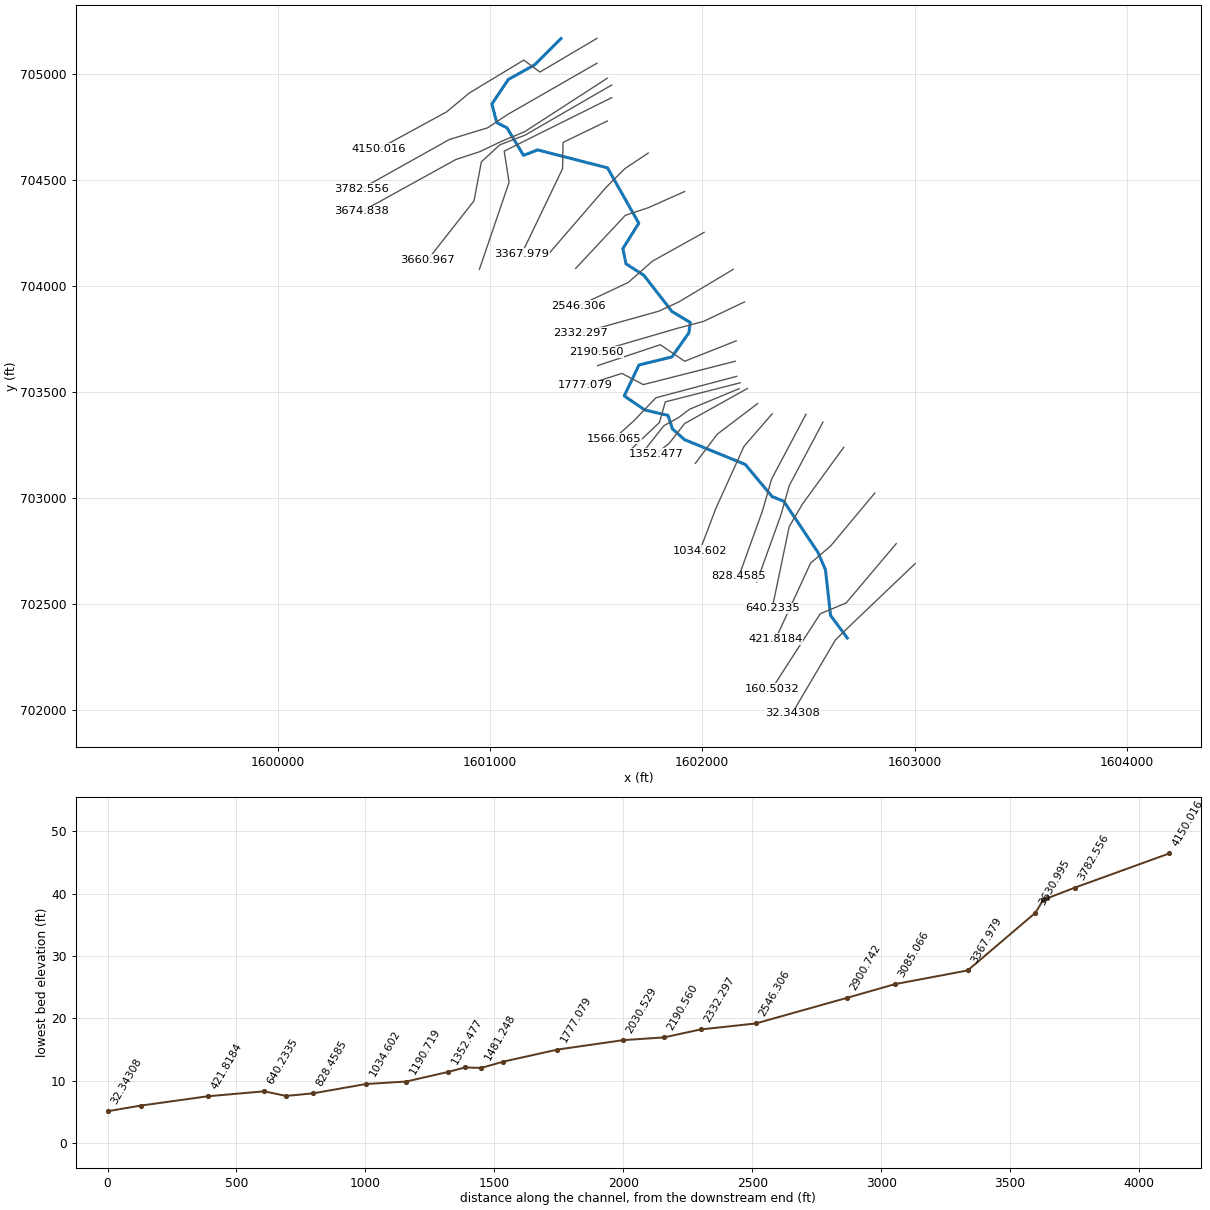
--- NortheastRiverTrib1.prj (project) ---

Proj Title=NortheastRiverTrib1
Current Plan=p01
Default Exp/Contr=0.3,0.1
English Units
Geom File=g01
Flow File=f01
Plan File=p01
Y Axis Title=Elevation
X Axis Title(PF)=Main Channel Distance
X Axis Title(XS)=Station
BEGIN DESCRIPTION:
Northeast River Trib 1 - Georeferenced HEC-RAS model.  This was formerly an approximate method stream.  Projection:  MD Stateplane.  Horizontal datum:  NAD83.  Vertrial datum: NAVD88.  Units:Feet.  Created by: Jodell L. Kormanik-Sonterre, USACE- St Paul District as part of FEMA Map Modernization study for Cecil County, MD.
END DESCRIPTION:
DSS Export Rating Curves= 0
DSS Export Rating Curve Sorted= 0
DSS Export Volume Flow Curves= 0
DXF OffsetX= 0
DXF OffsetY= 0
DXF ScaleX= 1
DXF ScaleY= 10

--- NortheastRiverTrib1.p01 (plan) ---

Plan Title=NortheastRiverTrib1_100year
Program Version=4.00
Short Identifier=NERivTrib100
Geom File=g01
Flow File=f01
Subcritical Flow
K Sum by GR= 0
Std Step Tol= 0.01
Critical Tol= 0.01
Num of Std Step Trials= 20
Max Error Tol= 0.3
Flow Tol Ratio= 0.001
Split Flow NTrial= 30
Split Flow Tol= 0.02
Split Flow Ratio= 0.02
Log Output Level= 0
Friction Slope Method= 1
Unsteady Friction Slope Method= 2
Unsteady Bridges Friction Slope Method= 1
Parabolic Critical Depth
Global Vel Dist= 0 , 0 , 0
Global Log Level= 0
CheckData=True
Encroach Param=-1 ,0,0, 0
Computation Interval=1HOUR
Output Interval=1HOUR
Run HTab= 0
Run UNet= 0
Run PostProcess= 0
Run WQNet= 0
UNET Theta= 1
UNET Theta Warmup= 1
UNET ZTol= 0.02
UNET ZSATol= 0.05
UNET MxIter= 20
UNET MaxInSteps= 0
UNET DtIC= 0
UNET DtMin= 0
UNET MaxCRTS= 20
UNET WFStab= 2
UNET SFStab= 1
UNET WFX= 1
UNET SFX= 1
UNET DSS MLevel= 4
UNET DZMax Abort= 100
UNET Convert EG Bridges= 0
UNET Use Existing IB Tables=-1
UNET Froude Reduction=False
UNET Froude Limit= 1
UNET Froude Power= 10
UNET Time Slicing=0,0, 5
Instantaneous Interval=1HOUR
Write IC File= 0
Echo Input=False
Echo Output=False
Write Detailed= 0
Detailed Automatic Start=False, 10
WQ ULTIMATE=-1
WQ Max Comp Step=1HOUR
WQ Output Interval=15MIN
WQ Output Selected Increments= 0
WQ Output face flow=0
WQ Output face velocity=0
WQ Output face area=0
WQ Output face dispersion=0
WQ Output cell volume=0
WQ Output cell surface area=0
WQ Output cell continuity=0
WQ Output face conc=0
WQ Output face dconc_dx=0
WQ Output face courant=0
WQ Output face peclet=0
WQ Output face adv mass=0
WQ Output face disp mass=0
WQ Output cell mass=0
WQ Output cell source sink temp=0
WQ Output cell source sink nsm=0
WQ Output MaxMinRange=-1
WQ Daily Max Min Mean=-1
WQ Daily Range=0
WQ Daily Time=0
WQ Create Restart=0
WQ Fixed Restart=0
WQ System Summary=False
Sorting and Armoring Iterations= 10
XS Update Threshold= 0.02
Hydraulics Update Threshold= 0.02
Energy Slope Method= 1
Volume Change Method= 0
XS Weighting Method= 0
Number of US Weighted Cross Sections= 1
Number of DS Weighted Cross Sections= 1
Upstream XS Weight=0.25
Main XS Weight=0.5
Downstream XS Weight=0.25
Number of DS XS's Weighted with US Boundary= 1
Upstream Boundary Weight= 1
Weight of XSs Associated with US Boundary= 0
Number of US XS's Weighted with DS Boundary= 1
Downstream Boundary Weight= 0.5
Weight of XSs Associated with DS Boundary= 0.5
Sediment Output Level= 4
Mass or Volume Output= 0
Output Increment Type= 1
Profile and TS Output Increment= 10
XS Output Flag= 0
XS Output Increment= 10
Disregard all LS=0
Disregard all Conn=0
Disregard all Breaches=0
Disregard all Pumps=0

--- NortheastRiverTrib1.f01 (steady flow) ---

Flow Title=NortheastRiverTrib1_100year
Program Version=4.00
Number of Profiles= 2
Profile Names=100CUR,100ULT
River Rch & RM=NERiverTrib1,Reach1          ,4150.016
    2025    2036
River Rch & RM=NERiverTrib1,Reach1          ,1034.602
    2184    2195
River Rch & RM=NERiverTrib1,Reach1          ,828.4585
    2416    2427
Boundary for River Rch & Prof#=NERiverTrib1,Reach1          , 1
Up Type= 0
Dn Type= 3
Dn Slope=0.006
Boundary for River Rch & Prof#=NERiverTrib1,Reach1          , 2
Up Type= 0
Dn Type= 3
Dn Slope=0.006
DSS Import GetInterval= 0
DSS Import GetPeak= 0
DSS Import FillOption= 0

--- NortheastRiverTrib1.g01 (geometry) ---

Geom Title=NortheastRiverTrib1
Program Version=4.00

River Reach=NERiverTrib1    ,Reach1
Reach XY= 30
1601334.68419947705164.6794678721601209.85106562705040.651709065
1601086.62868185704972.194829196 1601009.3126764704857.026196018
1601031.86317797704769.240314797 1601080.1856814704744.273688018
1601158.30706194704614.6083038451601224.34781666704640.380305663
1601553.74621502704555.8159246741601701.12985046704294.874406144
1601626.22997013704175.6788976941601640.72672117704104.000517607
1601725.29110222704049.2350137231601858.17798658703878.495501608
1601943.54774266703827.7568730121601937.10474221703778.628994524
1601857.37261155703665.071111456 1601701.9352255703627.218483776
1601632.67297058703481.4455984381601729.31797744703415.404843748
1601838.84898523 703389.632841931601859.78873672703326.008212402
1601916.97036576703275.2695838061602202.87851106703158.490200534
1602329.32239503703007.0796897861602384.08789891 702985.33456324
1602545.17680687702744.4304388171602580.52054369702662.497230783
1602604.61854605702447.2217430031602683.33868709702341.190532595

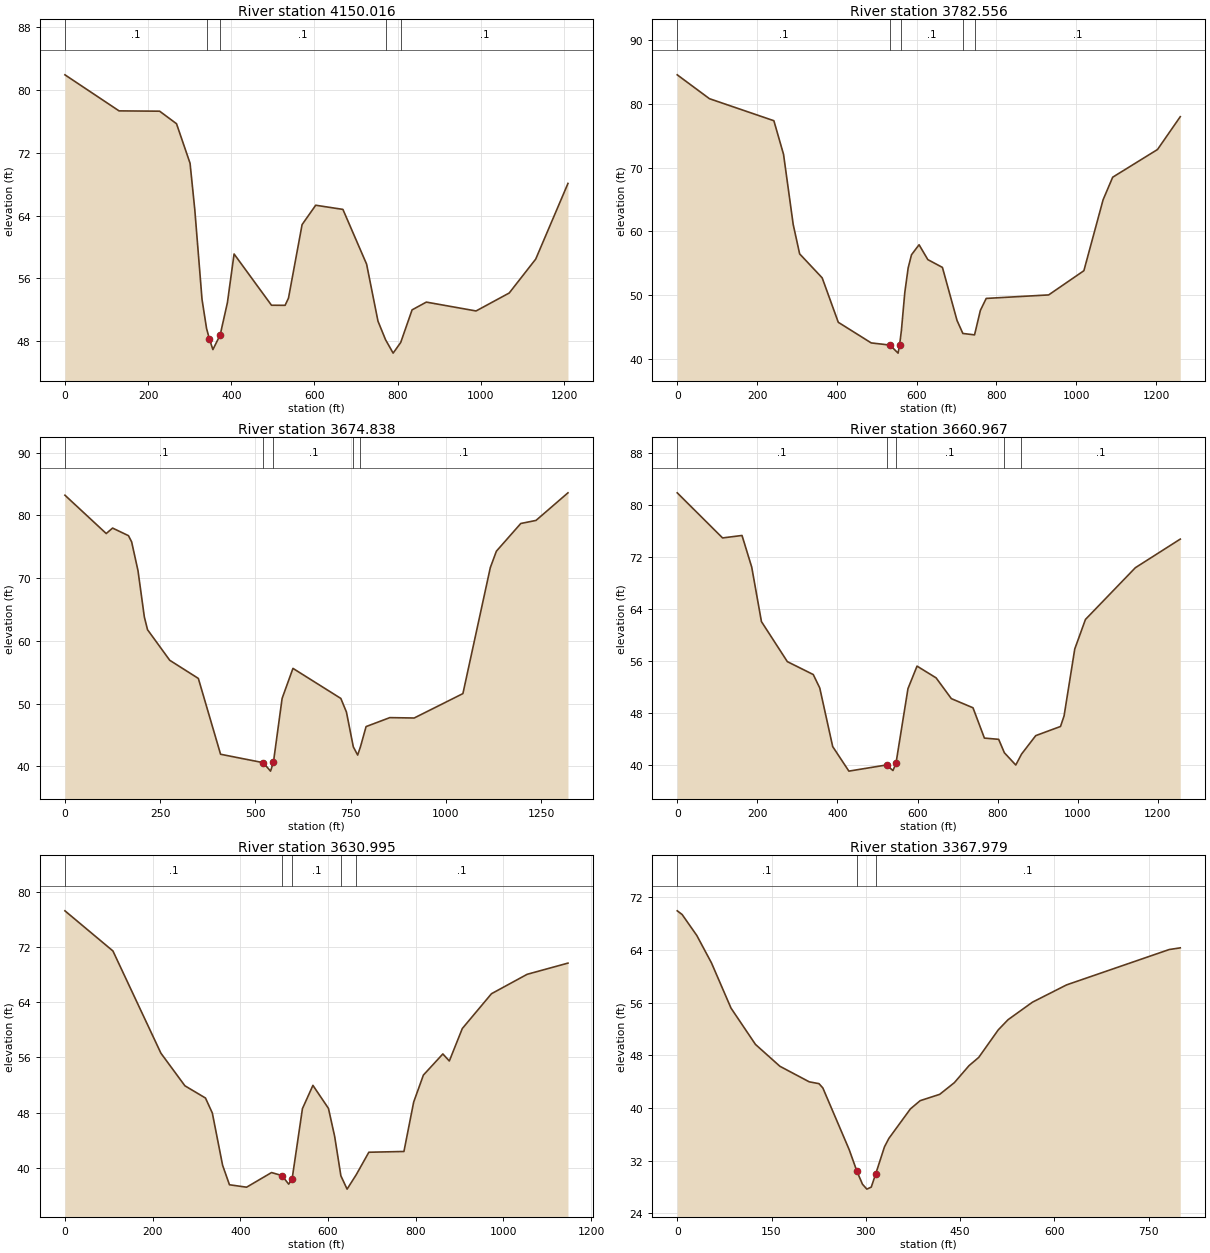
Type RM Length L Ch R = 1 ,4150.016,262.06,367.46,373.75
XS GIS Cut Line= 6
1601504.31479011705165.8960499321601235.52927142705007.069983885
1601159.66882476705063.4234585321600902.46578676704908.090163097
1600796.51036224704819.8005024641600476.43703634704645.451617643
#Sta/Elev= 30
       0   81.95  130.09   77.35  227.66   77.31  268.31   75.71  300.84   70.67
   312.2   64.77  329.64   53.29   340.5    49.6  347.08    48.3   355.8   46.89
  373.2748.76578  390.68   52.88  406.71   59.09  496.66   52.55  529.37   52.54
  537.55   53.46  570.26   62.84  602.97   65.31  668.39   64.78   725.4   57.79
  752.73   50.52  770.96   48.15  789.18   46.44   807.4    47.8  834.74   51.96
  869.01   52.95  988.57   51.82 1068.29   54.11 1132.06   58.44 1209.57   68.09
#Mann= 5 ,-1 , 0
       0      .1       0   340.5    .045       0  373.27      .1       0
  770.96    .045       0   807.4      .1       0
Bank Sta=347.08,373.27
XS Rating Curve= 0 ,0
Exp/Cntr=0.3,0.1

Type RM Length L Ch R = 1 ,3782.556,108.69,107.72,101.3
XS GIS Cut Line= 5
1601504.31479011705048.7960526791601082.75479996704806.789391652
1600989.07480218704744.3360597791600809.52147304  704689.6893944
1600395.76814933 704458.09162204
#Sta/Elev= 30
       0   84.54   80.71    80.8  242.14   77.35  266.36   72.09  290.57    61.1
  306.72   56.49  363.22   52.73  403.57   45.77  486.09   42.54  533.08    42.2
  553.39   40.94  557.32   42.28   561.8   44.53  570.22   50.42  578.63   54.28
  587.04   56.35  605.99   57.92  627.94   55.59  664.53   54.37  701.11   46.06
  715.75   44.02  745.02    43.8  759.65   47.64  774.28   49.51  930.76   50.06
    1019   53.85 1067.13   64.96  1091.2    68.5 1203.51   72.84 1260.52   77.98
#Mann= 5 ,-1 , 0
       0      .1       0  533.08    .045       0   561.8      .1       0
  715.75    .045       0  745.02      .1       0
Bank Sta=533.08,557.32
XS Rating Curve= 0 ,0
Exp/Cntr=0.3,0.1

Type RM Length L Ch R = 1 ,3674.838,15.84,13.87,14.17
XS GIS Cut Line= 6
1601552.93704392704978.0989374821601163.45546749704726.081446841
1601053.48419885704680.2600848971600952.67720261704632.147654876
1600840.41486587704595.4905653451600395.94765507 704350.34627898
#Sta/Elev= 30
       0   83.21  108.39    77.1  125.06   77.97  166.75   76.76  175.09   75.77
  191.76   71.18  208.44    63.8  216.78   61.77  275.14   56.89  350.18      54
  408.54   41.91  520.25   40.57  539.74   39.22  547.32   40.65  570.07   50.81
  598.55    55.6   724.2   50.81  738.92   48.64  756.98   43.09  768.38   41.78
  775.74    43.1  790.47   46.32  852.81   47.75  916.76   47.69 1044.67   51.58
 1116.61   71.67  1132.6   74.29 1196.56    78.7 1236.53   79.19 1320.43   83.59
#Mann= 5 ,-1 , 0
       0      .1       0  520.25    .045       0  547.32      .1       0
  756.98    .045       0  775.74      .1       0
Bank Sta=520.25,547.32
XS Rating Curve= 0 ,0
Exp/Cntr=0.3,0.1

Type RM Length L Ch R = 1 ,3660.967,25.33,29.97,31.33
XS GIS Cut Line= 6
1601573.55665675704946.0239841191601165.74653558704710.043970153
1601046.61099455704664.2226082531600959.55040684704584.035224855
1600925.18438542704400.7497771081600707.53291625704123.530537412
#Sta/Elev= 30
       0   81.88  113.22   74.93  161.75   75.31  186.01   70.43  210.27   62.04
  274.97   55.87  339.67   53.88  355.85   51.82   388.2   42.78  428.64      39
  522.6639.95166  538.66   39.09  546.16   40.18  576.16   51.71  598.81   55.18
  646.39   53.37  684.46   50.17  738.54   48.76  767.02   44.09  802.63    43.9
  816.88   41.83  845.37   39.94  859.61   41.61  895.22   44.47  957.05   45.88
  965.95    47.5  992.65   57.82 1019.35   62.37 1143.94   70.34  1256.1   74.75
#Mann= 5 ,-1 , 0
       0      .1       0  522.66    .045       0  546.16      .1       0
  816.88    .045       0  859.61      .1       0
Bank Sta=522.66,546.16
XS Rating Curve= 0 ,0
Exp/Cntr=0.3,0.1

Type RM Length L Ch R = 1 ,3630.995,180.08,263.02,267.11
XS GIS Cut Line= 5
1601573.55665675704886.4562136081601172.61973988704687.133289188
1601067.23060744704634.4387229681601090.14128837704487.810364783
1600950.38613451704077.709175482
#Sta/Elev= 30
       0   77.23  109.44   71.42  218.88   56.62  273.61    51.9  320.51   50.13
  336.14   47.96   359.6   40.39  375.23   37.57  414.32   37.22  471.23   39.34
  494.92    38.9  510.36   37.66  518.19   38.44  541.66   48.59  565.58   51.96
     601   48.63  615.17   44.57  629.34   38.87  643.51   36.94  664.77   39.07
  693.11   42.28  773.15   42.39  795.34   49.54  817.52   53.45  861.89   56.51
  876.68   55.49  906.27   60.19  972.82   65.23 1054.17   68.04 1147.25   69.66
#Mann= 5 ,-1 , 0
       0      .1       0  494.92    .045       0  518.19      .1       0
  629.34    .045       0  664.77      .1       0
Bank Sta=494.92,518.19
XS Rating Curve= 0 ,0
Exp/Cntr=0.3,0.1

Type RM Length L Ch R = 1 ,3367.979,304.72,282.91,258.3
XS GIS Cut Line= 4
1601552.93704392704776.4849449691601344.44984709704675.677948698
1601342.15877898704551.960271493 1601149.7090589704151.023354575
#Sta/Elev= 30
       0   69.94    7.78   69.38    31.1    66.2   54.43   62.04   85.53   55.17
  124.41   49.66  163.28   46.34  209.93   43.98  225.48    43.7  231.58   43.05
  273.59   33.66   285.7   30.42  294.59   28.44  301.59   27.69  308.59      28
  315.86   30.06   329.6   34.11   336.6   35.39  370.85   39.87  386.38   41.12
  417.44   42.08  440.73   43.85  464.02   46.43  479.55   47.69  510.61   51.87
  526.14   53.41  564.96   56.07  619.32    58.7  782.37   64.06  800.05   64.32
#Mann= 3 , 0 , 0
       0      .1       0   285.7    .045       0  315.86      .1       0
Bank Sta=285.7,315.86
XS Rating Curve= 0 ,0
Exp/Cntr=0.3,0.1

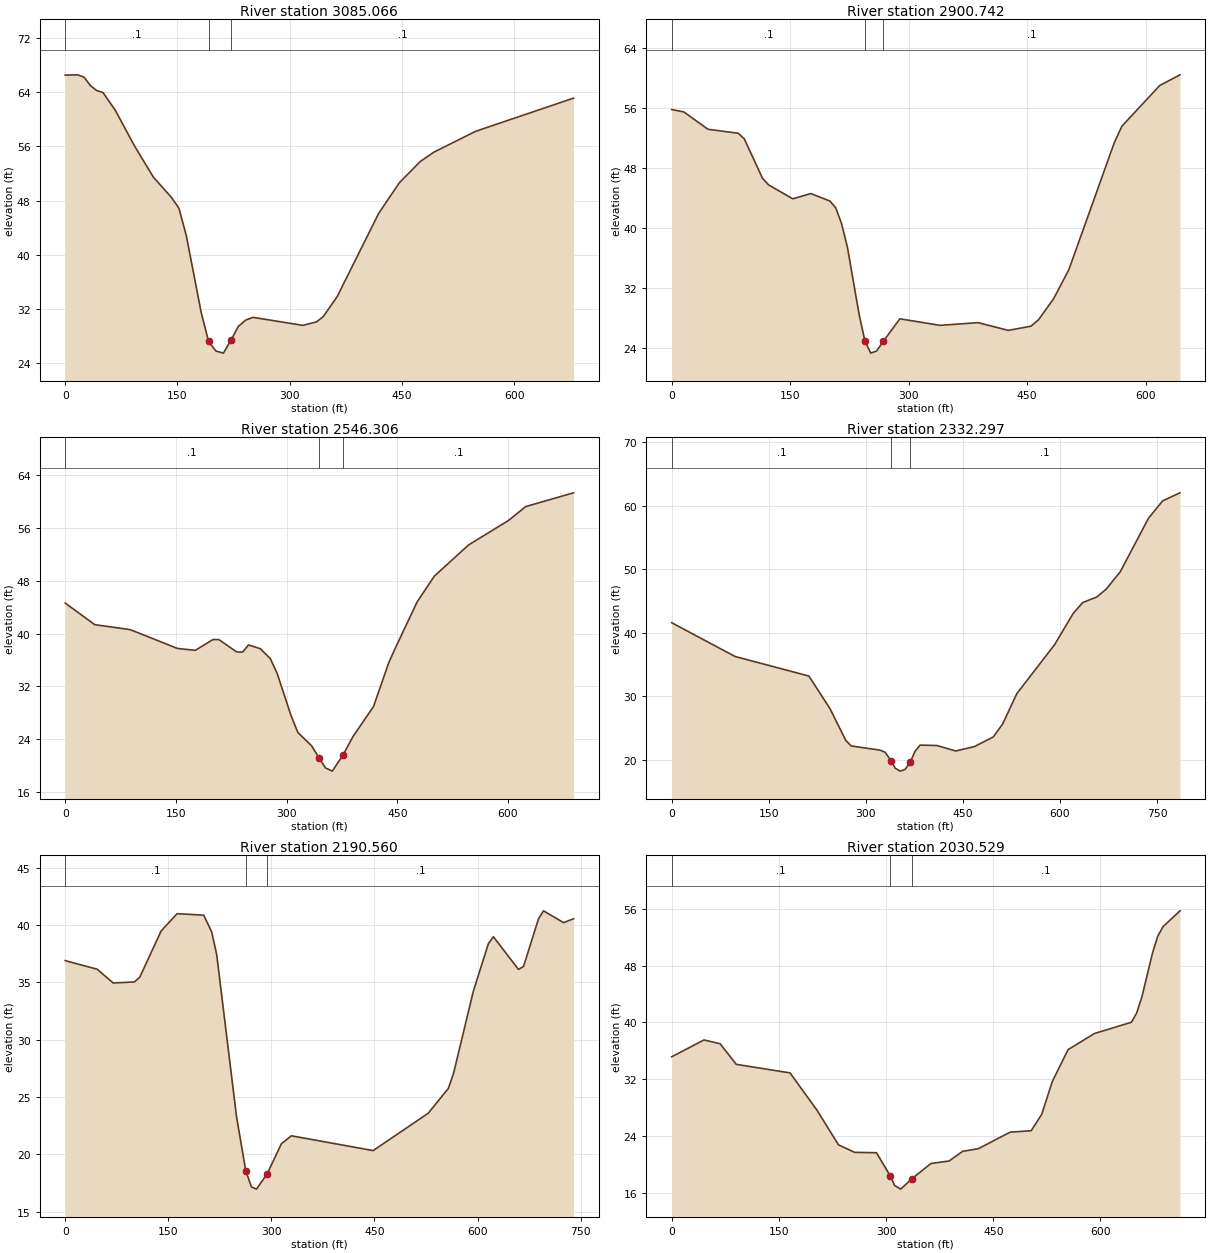
Type RM Length L Ch R = 1 ,3085.066,195.38,184.32,177
XS GIS Cut Line= 4
  1601745.386764  704625.27445061601635.41549537704551.960271493
1601543.77277152704460.3175476191601271.13566802704144.150150299
#Sta/Elev= 30
       0   66.52   16.83   66.56   25.24   66.21   33.65   64.98   42.06   64.24
   50.48   63.95    67.3   61.26   92.54   56.08  117.78   51.47  142.07   48.45
  151.97   46.88  161.87   42.81  181.67   31.51  191.57   27.21  201.47    25.8
  211.36   25.49  221.84   27.45  231.16   29.41  241.06   30.36  250.96   30.77
  317.23   29.59  335.72   30.09  344.96    30.9  363.45   33.84  418.91   46.12
  446.63   50.65  474.36   53.76  492.85   55.16  548.31   58.22  679.26   63.12
#Mann= 3 , 0 , 0
       0      .1       0  191.57    .045       0  221.84      .1       0
Bank Sta=191.57,221.84
XS Rating Curve= 0 ,0
Exp/Cntr=0.3,0.1

Type RM Length L Ch R = 1 ,2900.742,343.98,354.44,267.03
XS GIS Cut Line= 4
1601917.21687126704444.280070961 1601747.6778321704368.674823776
1601637.70656347704332.017734215 1601404.0176176704082.291311681
#Sta/Elev= 30
       0   55.75   15.33   55.43   45.99   53.12   84.31   52.59   91.97   51.84
  114.97    46.6  122.63   45.72  153.29   43.86  176.28   44.56  200.39   43.56
  207.77   42.65  215.15   40.54  222.53    37.4  237.28   28.48  244.66   24.93
  252.04   23.31  259.42   23.59  267.92   24.88  288.93   27.88   339.9   27.01
  387.84   27.37  426.18   26.34  454.94    26.9  464.53   27.76   483.7   30.58
  502.88   34.43   560.4   51.34  569.99   53.53  617.92   58.95  643.57   60.37
#Mann= 3 , 0 , 0
       0      .1       0  244.66    .045       0  267.92      .1       0
Bank Sta=244.66,267.92
XS Rating Curve= 0 ,0
Exp/Cntr=0.3,0.1

Type RM Length L Ch R = 1 ,2546.306,228.71,214.01,194.46
XS GIS Cut Line= 4
1602008.85959516704251.8303508461601766.00637689704116.657333136
1601651.45297205704015.8503368791601417.76402619703905.879068241
#Sta/Elev= 30
       0   44.62   40.06   41.35   88.12    40.6  152.21   37.75  176.25   37.47
  200.28    39.1  208.29   39.09  232.33   37.23  240.34    37.2  248.35   38.28
  264.37   37.72  277.94   36.21  287.26   33.97  305.91   27.64  315.24   25.05
  333.88   23.03  343.78   21.24  352.53    19.7  361.86    19.2   376.5   21.63
  389.83   24.41   417.8   28.98  438.27   35.55     446   37.49  476.95   44.81
  500.16   48.69  546.58   53.41  600.73   57.11  623.94   59.21   688.8   61.29
#Mann= 3 , 0 , 0
       0      .1       0  343.78    .045       0   376.5      .1       0
Bank Sta=343.78,376.5
XS Rating Curve= 0 ,0
Exp/Cntr=0.3,0.1

Type RM Length L Ch R = 1 ,2332.297,137.56,141.74,105
XS GIS Cut Line= 4
1602146.32368092704077.7091754821601889.72405407703924.207613021
1601795.79026213703880.6773191691601426.92829859703777.579254836
#Sta/Elev= 30
       0   41.58   97.88   36.27  212.08   33.19  244.71   28.05  269.18   23.06
  277.33    22.2  322.15   21.54  329.87   21.21  339.51   19.78   345.3   18.71
  353.01   18.24  360.73   18.51  368.44   19.61  376.16   21.36  383.87   22.33
  409.81   22.27  438.88   21.41  467.95    22.1  497.03   23.62  511.56   25.67
  533.37   30.42  591.51   38.09  620.59   43.05  635.12   44.74  656.93   45.62
  671.47   46.85  693.27    49.6  736.88   58.01  758.69   60.73  785.54      62
#Mann= 3 , 0 , 0
       0      .1       0  339.51    .045       0  368.44      .1       0
Bank Sta=339.51,368.44
XS Rating Curve= 0 ,0
Exp/Cntr=0.3,0.1

Type RM Length L Ch R = 1 ,2190.560,179.86,160.03,84.29
XS GIS Cut Line= 4
1602199.01824714703924.207613021  1602006.568527703832.564889148
1601885.14191793  703800.4899358 1601500.2424777703688.227599055
#Sta/Elev= 30
       0   36.89   46.52   36.14   69.78   34.94  100.79   35.03  108.54   35.45
  139.56   39.47  162.82   40.98  201.58   40.85  213.16   39.39   220.4   37.43
  249.36   23.26  262.81   18.55  271.08   17.16  278.32   16.97  293.88    18.3
  314.52   20.92     329   21.62  448.12   20.33  528.33   23.59   557.5   25.75
  564.79   26.99  593.96   34.24  615.83   38.37  623.12   38.97  659.58   36.12
  666.87   36.38  688.75   40.54  696.04   41.23  725.21    40.2  739.68   40.54
#Mann= 3 , 0 , 0
       0      .1       0  262.81    .045       0  293.88      .1       0
Bank Sta=262.81,293.88
XS Rating Curve= 0 ,0
Exp/Cntr=0.3,0.1

Type RM Length L Ch R = 1 ,2030.529,121.2,253.45,226.9
XS GIS Cut Line= 4
1602160.07008952703740.9221652751601917.21687126703644.697305232
1601802.66346642703722.5936205091601507.11568193703624.077692375
#Sta/Elev= 30
       0   35.15   45.18   37.52   67.77   36.99   90.35   34.09  165.65   32.88
   203.3   27.64  233.41   22.76     256    21.7  286.62   21.64  305.92   18.37
  312.01   17.03  320.48   16.52  335.94   17.96   362.8   20.13   388.2   20.48
  407.13   21.84  429.27   22.22  473.54   24.54  503.05   24.74  517.81   27.05
  532.57   31.66   554.7   36.16   591.6   38.43  643.25   40.01  650.63   41.31
     658   43.59  672.76   49.73  680.14   52.13  687.52   53.47  711.29    55.7
#Mann= 3 , 0 , 0
       0      .1       0  305.92    .045       0  335.94      .1       0
Bank Sta=305.92,335.94
XS Rating Curve= 0 ,0
Exp/Cntr=0.3,0.1

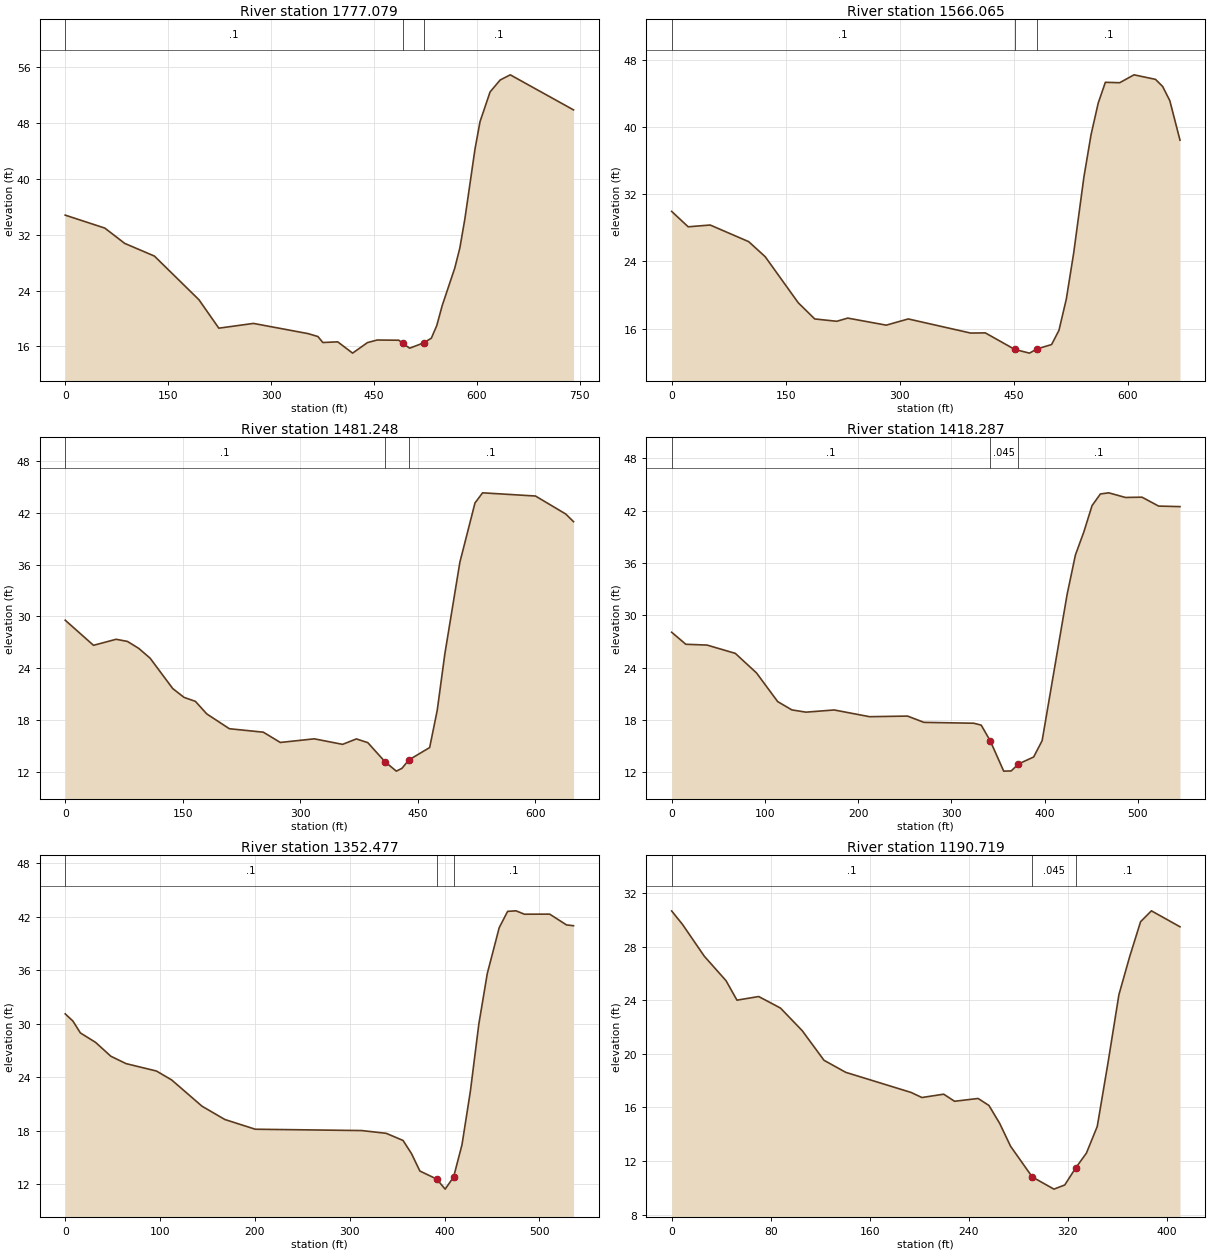
Type RM Length L Ch R = 1 ,1777.079,74.66,211.01,227.22
XS GIS Cut Line= 4
1602155.48795332703644.6973052321601722.47608307703534.726036593
1601621.66908677703587.4206028131601449.83897957703532.434968501
#Sta/Elev= 30
       0   34.81   57.78   32.95   86.67   30.76     130   28.94     195   22.67
  223.89    18.6  274.44   19.28  353.89   17.82  368.33    17.4  375.56   16.54
  397.22   16.64  418.89   15.02  440.56   16.53  454.66    16.9  486.25   16.87
  492.19   16.41  502.05   15.73  522.28   16.48  533.64   17.16  541.54   18.96
  549.44   21.82  567.86   27.23  575.21    30.1  582.56   34.28  597.26   44.26
  604.61   48.21   619.3   52.48     634   54.19   648.7   54.93  740.92    49.9
#Mann= 3 , 0 , 0
       0      .1       0  492.19    .045       0  522.28      .1       0
Bank Sta=492.19,522.28
XS Rating Curve= 0 ,0
Exp/Cntr=0.3,0.1

Type RM Length L Ch R = 1 ,1566.065,30.77,84.82,98.31
XS GIS Cut Line= 4
1602162.36115763703573.6741942471601782.04385358703472.867197976
1601678.94578919703365.1869974431601585.01199725703280.417477861
#Sta/Elev= 30
       0   29.94   21.73   28.11   50.69   28.32  101.38   26.34  123.11   24.55
  166.56   19.07  188.28   17.14  217.25   16.86  231.74   17.24  282.43    16.4
  311.39   17.14  393.45   15.46  412.83   15.48   451.6   13.51  470.98   13.07
  480.67   13.57  500.05   14.09  509.74   15.78  519.44   19.51  529.13   24.99
  542.53      34  551.96   39.06  561.39   42.83  570.82   45.31  589.67   45.26
  608.53    46.2  636.82   45.66  646.25   44.81  655.68   43.12  669.06   38.42
#Mann= 3 , 0 , 0
       0      .1       0   451.6    .045       0  480.67      .1       0
Bank Sta=451.6,480.67
XS Rating Curve= 0 ,0
Exp/Cntr=0.3,0.1

Type RM Length L Ch R = 1 ,1481.248,81,62.96,32.76
XS GIS Cut Line= 4
1602179.09212986703543.2518167641601826.09018047703453.270927683
1601798.40375307703356.3684317771601665.16282116703230.049106747
#Sta/Elev= 30
       0   29.56   36.12   26.65   65.01   27.35   79.46    27.1   93.91   26.29
  108.36   25.16  137.25   21.64   151.7   20.62  166.15   20.16   180.6   18.71
  209.49   16.99  252.83   16.59  274.51    15.4  317.85   15.82  353.97   15.18
  371.57   15.81  386.13   15.38  408.27   13.15  422.53   12.08  429.81   12.41
  438.44   13.37  465.07   14.81  474.72   19.11  484.36    25.6  503.65   36.28
  522.94   43.14  532.59   44.31  600.11   43.94  638.69   41.86  648.67   40.97
#Mann= 3 , 0 , 0
       0      .1       0  408.27    .045       0  438.44      .1       0
Bank Sta=408.27,438.44
XS Rating Curve= 0 ,0
Exp/Cntr=0.3,0.1

Type RM Length L Ch R = 1 ,1418.287,56.85,65.81,70.04
XS GIS Cut Line= 5
1602173.90092474703515.5653893651601940.29669353703418.662893429
 1601890.1150438703380.594055742 1601819.1685736 703340.79481636
1601727.45728287703224.857901603
#Sta/Elev= 30
       0   28.07   15.16   26.69   37.89    26.6   68.21   25.65   90.94   23.41
  113.68   20.12  128.83   19.17  143.99   18.91   174.3   19.16  212.19   18.39
  252.91   18.46  270.48   17.74  323.92   17.64  331.95   17.42   341.7    15.6
  356.02   12.15  364.05   12.17  371.84   12.97  388.13   13.77  397.24   15.64
  424.02    32.4  432.94   36.93  441.87   39.54  450.79   42.59  459.72   43.92
  468.64   44.05  486.49   43.52  504.34   43.55   522.2   42.53  545.07   42.47
#Mann= 3 , 0 , 0
       0      .1       0   341.7    .045       0  371.84      .1       0
Bank Sta=341.7,371.84
XS Rating Curve= 0 ,0
Exp/Cntr=0.3,0.1

Type RM Length L Ch R = 1 ,1352.477,168.88,161.76,157.76
XS GIS Cut Line= 4
1602212.76465574703516.3974918131601917.21687126703351.440588877
1601843.90269215703257.5067969261601782.04385358 703209.39436686
#Sta/Elev= 30
       0   31.09    8.02    30.3   16.03   28.95   32.07   27.89    48.1   26.34
   64.13   25.51    96.2   24.68  112.23   23.68   144.3   20.73  168.35   19.24
  200.41   18.15  312.64      18  338.47   17.69  356.23   16.89  365.11   15.42
  373.98   13.46  391.74   12.56  400.62   11.43   409.5   12.78  418.38   16.41
  427.26   22.44  436.14   29.95  445.02    35.6  457.62   40.76  466.49   42.59
  475.36   42.65  484.23   42.27  510.83   42.28  528.57   41.07  535.99   40.98
#Mann= 3 , 0 , 0
       0      .1       0  391.74    .045       0   409.5      .1       0
Bank Sta=391.74,409.5
XS Rating Curve= 0 ,0
Exp/Cntr=0.3,0.1

Type RM Length L Ch R = 1 ,1190.719,145.55,156.12,172.71
XS GIS Cut Line= 3
1602260.87708576703445.3743808271602070.71843372703301.037090734
1601967.62036937703163.573004931
#Sta/Elev= 30
       0   30.67    8.79   29.66   26.36   27.29   43.94   25.46   52.73   24.01
    70.3   24.28   87.88   23.42  105.46   21.73  123.03   19.52  140.61   18.62
  193.34   17.12  202.13   16.74   219.7   16.99  228.49   16.46  247.48   16.67
  256.23   16.15  264.98    14.8  273.73    13.1  291.23   10.81  308.73     9.9
  317.48   10.21  326.23   11.47  334.98   12.59  343.73   14.58  352.48   19.37
  361.23   24.42  369.98   27.28  378.73   29.87  387.48   30.68  410.56   29.49
#Mann= 3 , 0 , 0
       0      .1       0  291.23    .045       0  326.23      .1       0
Bank Sta=291.23,326.23
XS Rating Curve= 0 ,0
Exp/Cntr=0.3,0.1

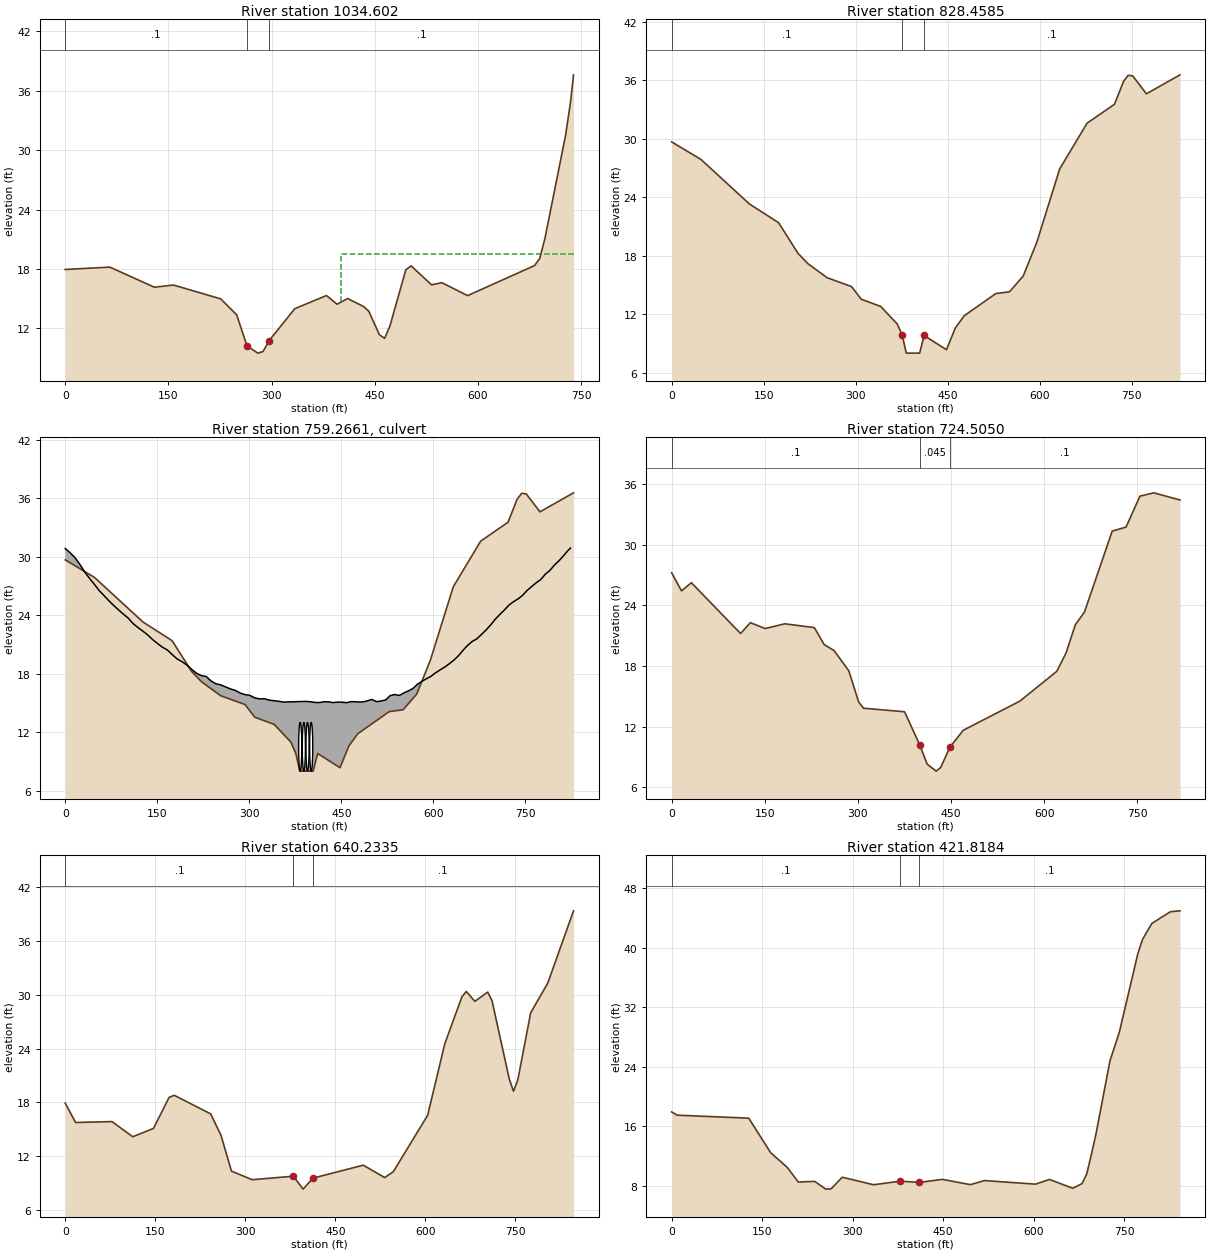
Type RM Length L Ch R = 1 ,1034.602,191.41,206.14,209.64
XS GIS Cut Line= 4
1602329.60912867703397.2619508061602196.72717905703243.760388315
1602063.84522942702950.5036719591601987.99870454702750.570896193
#Sta/Elev= 30
       0   17.95   64.81   18.19  129.62   16.16  157.39   16.38  226.08   14.98
  249.14   13.38   264.2   10.24  279.88     9.5  287.56    9.66  296.49   10.77
  333.67   13.99  379.79   15.32  395.16   14.44  410.53   15.02  433.58   14.21
  441.27   13.73  456.64   11.36  464.32      11  472.01   12.25  495.06   17.92
  502.75   18.32  532.47    16.4  547.45   16.62  584.88   15.31  682.21   18.35
  689.69   19.06  697.18   21.07  727.13   31.45  734.61   34.93  738.82   37.62
#Mann= 3 , 0 , 0
       0      .1       0   264.2    .045       0  296.49      .1       0
#XS Ineff= 2 , 0
                          400.98           19.48
Permanent Ineff=
       F       F
Bank Sta=264.2,296.49
XS Rating Curve= 0 ,0
Exp/Cntr=0.5,0.3

Type RM Length L Ch R = 1 ,828.4585,97.17,103.95,93.38
BEGIN DESCRIPTION:
Lowered stations 382.39 thru 404.23 to accomodate culvert opening.
END DESCRIPTION:
XS GIS Cut Line= 4
1602488.84660709703395.3309980481602326.74957798703089.662314579
1602284.82516596702942.9268723881602172.96347964702632.453620613
#Sta/Elev= 30
       0   29.67   47.54   27.88  126.77    23.3  174.31   21.38  206.01   18.23
  221.85   17.19  253.55   15.73  293.16   14.83  309.01   13.53   340.7   12.79
  367.83   10.98  375.94    9.81  382.39       8  404.23       8  411.51    9.81
  447.91    8.35  462.47   10.59  477.03   11.84  528.36   14.11  550.68   14.29
     573    15.9  595.32   19.39  632.53    26.9  677.17   31.59  721.81   33.53
  736.69   35.89  744.13    36.5  751.57   36.44   773.9    34.6  828.61   36.55
#Mann= 3 , 0 , 0
       0      .1       0  375.94    .045       0  411.51      .1       0
Bank Sta=375.94,411.51
XS Rating Curve= 0 ,0
Exp/Cntr=0.5,0.3

Type RM Length L Ch R = 2 ,759.2661,,,
BEGIN DESCRIPTION:
OLD PHILADELPHIA ROAD:
MDE Bridge #: CE041007PF-3
Road Profile take from DEM.
Culvert dimensions from bridge surveys.
END DESCRIPTION:
Bridge Culvert--1,0,-1,-1, 0
Deck Dist Width WeirC Skew NumUp NumDn MinLoCord MaxHiCord MaxSubmerge Is_Ogee
25,50,2.6,0, 110, 110, , , 0.98, 0, 0.5,0.5,,
       0    7.92   15.85   23.77   31.69   39.62   47.54   55.46   63.39   71.31
   79.23   87.16   95.08     103  110.93  118.85  126.77   134.7  142.62  150.54
  158.47  166.39  174.31  182.24  190.16  198.08  206.01  213.93  221.85  229.78
   237.7  245.62  253.55  261.47  269.39  277.32  285.24  293.16  301.09  309.01
  316.93  324.86  332.78  342.31  349.59  356.87  364.15  371.43  378.71  385.99
  393.27  400.55  407.83  415.11  422.39  429.67  436.95  444.24  451.52   458.8
  466.08  473.36  480.64  487.92  492.43  499.87  507.31  514.75  522.19  529.63
  537.07  544.51  551.95  559.39  566.83  574.27  581.71  589.15  596.59  604.03
  611.47  618.91  626.36   633.8  641.24  648.68  656.12  663.56     671  678.44
  685.88  693.32  700.76   708.2  715.64  723.08  730.52  737.96   745.4  752.84
  760.28  767.72  775.17  782.61  790.05  797.49  804.93  812.37  819.81  823.62
   30.84   30.41   29.91   29.22   28.44   27.78   27.16   26.52      26   25.47
   24.98   24.53   24.09   23.68   23.12   22.72   22.35   21.96   21.49   21.09
   20.71   20.43   19.96   19.52   19.24    18.9   18.45   18.04    17.8   17.71
   17.25   16.96   16.85   16.64   16.43   16.28   16.01   15.85   15.77   15.51
   15.41   15.43   15.28   15.21   15.15   15.08   15.11   15.11   15.13   15.14
   15.15   15.11   15.04   15.04   15.12    15.1   15.03   15.08   15.07   15.02
   15.13   15.12   15.08   15.13   15.21   15.35   15.13   15.19    15.3   15.74
   15.86   15.76   16.02   16.23   16.48   16.92   17.22   17.49   17.74    18.1
    18.4   18.68   19.03    19.4   19.85   20.41   20.91   21.31   21.57   22.01
   22.47   22.98   23.56   24.06   24.51   25.02   25.37   25.66   26.02   26.53
   26.93   27.32   27.65    28.2   28.59   29.14   29.58    30.1   30.65   30.88
                                                                                
                                                                                
                                                                                
                                                                                
                                                                                
                                                                                
                                                                                
                                                                                
                                                                                
                                                                                
                                                                                
       0    7.92   15.85   23.77   31.69   39.62   47.54   55.46   63.39   71.31
   79.23   87.16   95.08     103  110.93  118.85  126.77   134.7  142.62  150.54
  158.47  166.39  174.31  182.24  190.16  198.08  206.01  213.93  221.85  229.78
   237.7  245.62  253.55  261.47  269.39  277.32  285.24  293.16  301.09  309.01
  316.93  324.86  332.78  342.31  349.59  356.87  364.15  371.43  378.71  385.99
  393.27  400.55  407.83  415.11  422.39  429.67  436.95  444.24  451.52   458.8
  466.08  473.36  480.64  487.92  492.43  499.87  507.31  514.75  522.19  529.63
  537.07  544.51  551.95  559.39  566.83  574.27  581.71  589.15  596.59  604.03
  611.47  618.91  626.36   633.8  641.24  648.68  656.12  663.56     671  678.44
  685.88  693.32  700.76   708.2  715.64  723.08  730.52  737.96   745.4  752.84
  760.28  767.72  775.17  782.61  790.05  797.49  804.93  812.37  819.81  823.62
   30.84   30.41   29.91   29.22   28.44   27.78   27.16   26.52      26   25.47
   24.98   24.53   24.09   23.68   23.12   22.72   22.35   21.96   21.49   21.09
   20.71   20.43   19.96   19.52   19.24    18.9   18.45   18.04    17.8   17.71
   17.25   16.96   16.85   16.64   16.43   16.28   16.01   15.85   15.77   15.51
   15.41   15.43   15.28   15.21   15.15   15.08   15.11   15.11   15.13   15.14
   15.15   15.11   15.04   15.04   15.12    15.1   15.03   15.08   15.07   15.02
   15.13   15.12   15.08   15.13   15.21   15.35   15.13   15.19    15.3   15.74
   15.86   15.76   16.02   16.23   16.48   16.92   17.22   17.49   17.74    18.1
    18.4   18.68   19.03    19.4   19.85   20.41   20.91   21.31   21.57   22.01
   22.47   22.98   23.56   24.06   24.51   25.02   25.37   25.66   26.02   26.53
   26.93   27.32   27.65    28.2   28.59   29.14   29.58    30.1   30.65   30.88
                                                                                
                                                                                
                                                                                
                                                                                
                                                                                
                                                                                
                                                                                
                                                                                
                                                                                
                                                                                
                                                                                
BR Coef=-1 , 0 , 0 ,, 0 ,,,0.8,0,,0,
WSPro=,,,, 1 ,,,, 0 ,,,, 0 ,,,,-1 ,-1 ,-1 , 0 , 0 , 0 , 0 , 0
Culvert=1,5,,50,0.015,0.5,1,1,1,8,383,8,414,Culvert #1  , 0 ,25
Culvert Bottom n=0.015
Culvert=1,5,,50,0.015,0.5,1,1,1,8,389,8,420,Culvert #2  , 0 ,25
Culvert Bottom n=0.015
Culvert=1,5,,50,0.015,0.5,1,1,1,8,395,8,426,Culvert #3  , 0 ,25
Culvert Bottom n=0.015
Culvert=1,5,,50,0.015,0.5,1,1,1,8,401,8,432,Culvert #4  , 0 ,25
Culvert Bottom n=0.015
BC Design=,, 0 ,, 0 ,,,,,,
BC Use User HTab Curves=0
BC User HTab FreeFlow(D)= 0

Type RM Length L Ch R = 1 ,724.5050,99.97,84.27,64.01
XS GIS Cut Line= 4
1602568.84000862703358.410574362 1602410.1875042703059.237280309
1602369.63346484702917.2981424031602256.97047763702604.600871876
#Sta/Elev= 30
       0   27.23   15.85   25.44   31.69   26.25  110.93   21.22  126.77   22.29
  150.54   21.71  182.24   22.18  229.78    21.8  245.62   20.12  261.47   19.53
  285.24   17.53  301.09   14.45  309.01   13.82  375.04   13.47  399.41    10.2
  411.44    8.28     426    7.59  433.28    7.95  447.84    9.94  469.68   11.64
  560.66   14.52  620.19   17.47  635.07   19.28  649.95   22.07  664.83   23.35
  709.47   31.36  731.79   31.76  754.11   34.82  776.44   35.15  818.63   34.44
#Mann= 3 , 0 , 0
       0      .1       0  399.41    .045       0  447.84      .1       0
Bank Sta=399.41,447.84
XS Rating Curve= 0 ,0
Exp/Cntr=0.5,0.3

Type RM Length L Ch R = 1 ,640.2335,232.21,218.41,242.79
XS GIS Cut Line= 4
1602666.39613889703239.1782521161602471.65535064702971.123284817
1602409.79651202702865.7341523771602329.60912867702480.834712148
#Sta/Elev= 30
       0   17.92    17.3   15.76   77.87   15.86  112.48   14.17  147.09    15.1
  173.05   18.56   181.7   18.79  242.26   16.72  259.57   14.32  276.87   10.34
  311.48    9.38  380.03    9.77  396.26    8.33  412.49    9.55  496.43      11
  532.18    9.62  546.48   10.27  603.68   16.56  632.29   24.54  660.89   29.79
  668.04   30.37  682.34   29.27  703.79    30.3  710.94   29.34  739.54   20.64
  746.69   19.24  753.84   20.48  775.29   27.98  803.89   31.32  846.69   39.36
#Mann= 3 , 0 , 0
       0      .1       0  380.03    .045       0  412.49      .1       0
Bank Sta=380.03,412.49
XS Rating Curve= 0 ,0
Exp/Cntr=0.3,0.1

Type RM Length L Ch R = 1 ,421.8184,261.7,261.32,229.79
XS GIS Cut Line= 4
1602813.02449705703023.8178510371602604.53730027702774.091428503
1602510.60350826 702693.904045121602345.64660531702336.497422054
#Sta/Elev= 30
       0   17.92    9.12   17.48  127.66   17.08  164.14   12.43   191.5   10.47
  209.73     8.5  237.09    8.58  255.33    7.54  264.45    7.59  282.68    9.14
  334.52    8.13  378.94    8.61  410.36    8.44  448.82    8.85  495.08    8.14
  518.21    8.69  603.01    8.21  626.14    8.84  664.69    7.66  680.11    8.28
  687.82    9.55  695.53   12.17  703.24   14.96  726.37   24.77  741.79   28.59
  772.62    39.2  780.33    41.1  795.75   43.25  826.59   44.83  842.46   44.95
#Mann= 3 , 0 , 0
       0      .1       0  378.94    .045       0  410.36      .1       0
Bank Sta=378.94,410.36
XS Rating Curve= 0 ,0
Exp/Cntr=0.3,0.1

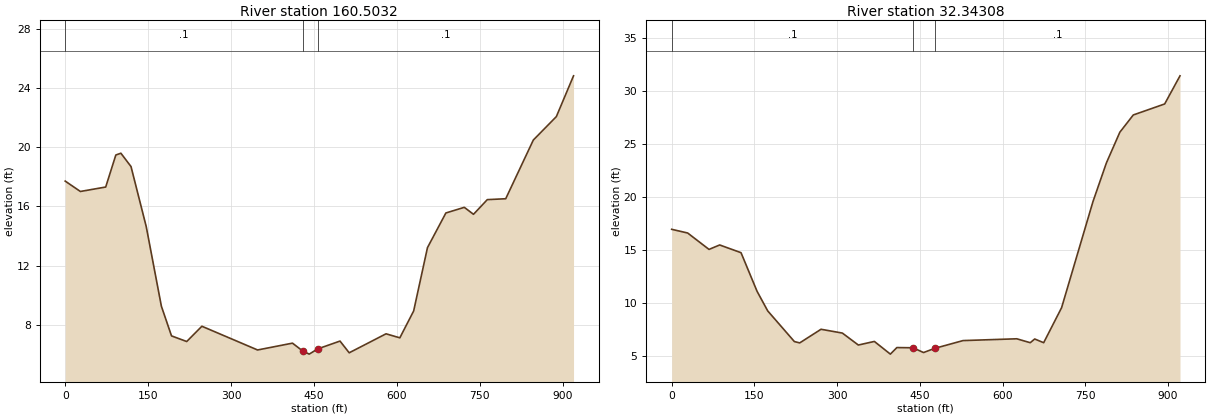
Type RM Length L Ch R = 1 ,160.5032,98.77,128.16,143.39
XS GIS Cut Line= 4
1602913.83149329702785.5467689931602677.85147932702506.036461204
1602556.42487025702455.6329631061602327.31806058702100.517408118
#Sta/Elev= 30
       0   17.71   27.48   17.01   73.29   17.31   91.61   19.47  100.77   19.59
  119.09   18.69  146.58   14.65  174.06    9.27  192.38    7.27  219.87    6.89
  247.35    7.92  348.12    6.32  411.28    6.78  429.86    6.25   441.6    6.04
  456.75    6.39  497.28    6.92  513.94    6.13  580.58    7.41  605.57    7.14
  630.56    8.95  655.55   13.22  688.88   15.56   722.2   15.94  738.86   15.47
  763.85   16.46  797.17   16.52  847.15   20.48   888.8   22.06  919.88   24.81
#Mann= 3 , 0 , 0
       0      .1       0  429.86    .045       0  456.75      .1       0
Bank Sta=429.86,456.75
XS Rating Curve= 0 ,0
Exp/Cntr=0.3,0.1

Type RM Length L Ch R = 1 ,32.34308,25.57,32.34,29.13
XS GIS Cut Line= 4
 1603003.1831491702691.6129770281602707.63536461702409.811601162
1602627.44798121702331.9152858561602423.54292062 701985.96400328
#Sta/Elev= 30
       0   16.94   29.02   16.59    67.7   15.04   87.05   15.46  125.74   14.73
  154.75   11.09   174.1    9.23  222.46    6.33  232.13     6.2  270.82    7.49
   309.5    7.13  338.52       6  367.54    6.34  396.55    5.14  408.36    5.76
  437.64    5.74  456.72    5.29  476.68    5.68  528.28    6.42  625.79    6.59
  650.16    6.22  658.29    6.57  674.54    6.22  707.04    9.53  763.92   19.56
   788.3   23.22  812.67   26.12  837.05   27.75  893.93   28.79  921.73   31.45
#Mann= 3 , 0 , 0
       0      .1       0  437.64    .045       0  476.68      .1       0
Bank Sta=437.64,476.68
XS Rating Curve= 0 ,0
Exp/Cntr=0.3,0.1

Chan Stop Cuts=-1
Use User Specified Reach Order=0