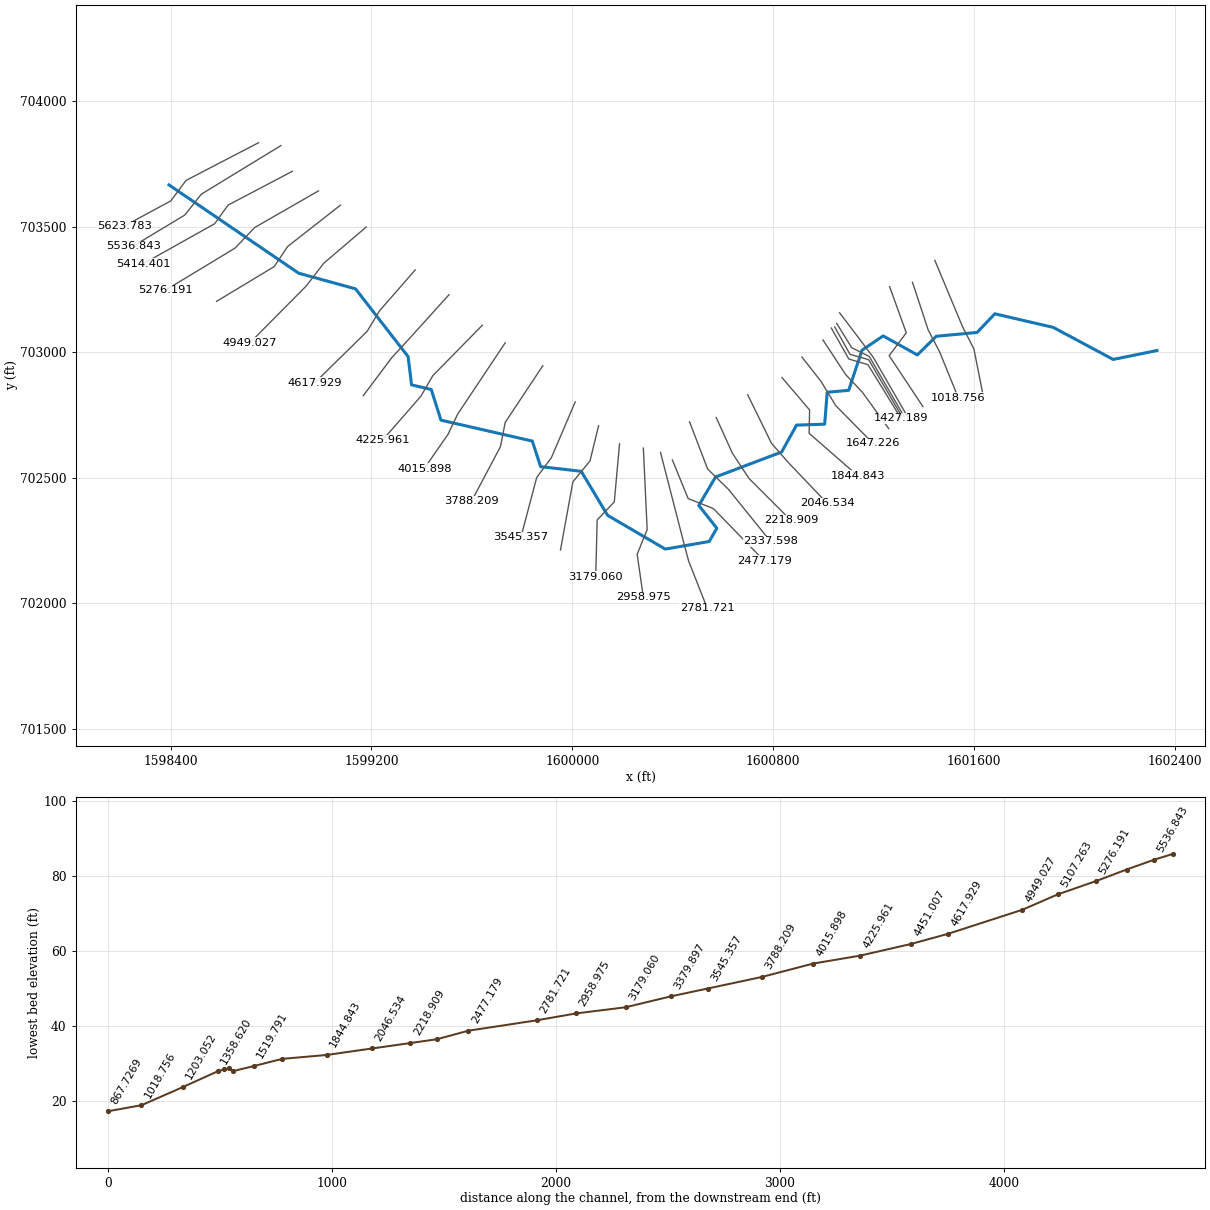
--- NortheastRiverTrib2.prj (project) ---

Proj Title=NortheastRiverTrib2
Current Plan=p01
Default Exp/Contr=0.3,0.1
English Units
Geom File=g01
Flow File=f01
Plan File=p01
Y Axis Title=Elevation
X Axis Title(PF)=Main Channel Distance
X Axis Title(XS)=Station
BEGIN DESCRIPTION:
Northeast River Trib 2 - Georeferenced HEC-RAS model.  This was formerly an approximate method stream.  Projection:  MD Stateplane.  Horizontal datum:  NAD83.  Vertrial datum: NAVD88.  Units:Feet.  Created by: Jodell L. Kormanik-Sonterre, USACE- St Paul District as part of FEMA Map Modernization study for Cecil County, MD.
END DESCRIPTION:
DSS Export Rating Curves= 0
DSS Export Rating Curve Sorted= 0
DSS Export Volume Flow Curves= 0
DXF OffsetX= 0
DXF OffsetY= 0
DXF ScaleX= 1
DXF ScaleY= 10

--- NortheastRiverTrib2.p01 (plan) ---

Plan Title=NortheastRiverTrib2_100year
Program Version=4.00
Short Identifier=NERivTrib2_100
Geom File=g01
Flow File=f01
Subcritical Flow
K Sum by GR= 0
Std Step Tol= 0.01
Critical Tol= 0.01
Num of Std Step Trials= 20
Max Error Tol= 0.3
Flow Tol Ratio= 0.001
Split Flow NTrial= 30
Split Flow Tol= 0.02
Split Flow Ratio= 0.02
Log Output Level= 0
Friction Slope Method= 1
Unsteady Friction Slope Method= 2
Unsteady Bridges Friction Slope Method= 1
Parabolic Critical Depth
Global Vel Dist= 0 , 0 , 0
Global Log Level= 0
CheckData=True
Encroach Param=-1 ,0,0, 0
Computation Interval=1HOUR
Output Interval=1HOUR
Run HTab= 0
Run UNet= 0
Run PostProcess= 0
Run WQNet= 0
UNET Theta= 1
UNET Theta Warmup= 1
UNET ZTol= 0.02
UNET ZSATol= 0.05
UNET MxIter= 20
UNET MaxInSteps= 0
UNET DtIC= 0
UNET DtMin= 0
UNET MaxCRTS= 20
UNET WFStab= 2
UNET SFStab= 1
UNET WFX= 1
UNET SFX= 1
UNET DSS MLevel= 4
UNET DZMax Abort= 100
UNET Convert EG Bridges= 0
UNET Use Existing IB Tables=-1
UNET Froude Reduction=False
UNET Froude Limit= 1
UNET Froude Power= 10
UNET Time Slicing=0,0, 5
Instantaneous Interval=1HOUR
Write IC File= 0
Echo Input=False
Echo Output=False
Write Detailed= 0
Detailed Automatic Start=False, 10
WQ ULTIMATE=-1
WQ Max Comp Step=1HOUR
WQ Output Interval=15MIN
WQ Output Selected Increments= 0
WQ Output face flow=0
WQ Output face velocity=0
WQ Output face area=0
WQ Output face dispersion=0
WQ Output cell volume=0
WQ Output cell surface area=0
WQ Output cell continuity=0
WQ Output face conc=0
WQ Output face dconc_dx=0
WQ Output face courant=0
WQ Output face peclet=0
WQ Output face adv mass=0
WQ Output face disp mass=0
WQ Output cell mass=0
WQ Output cell source sink temp=0
WQ Output cell source sink nsm=0
WQ Output MaxMinRange=-1
WQ Daily Max Min Mean=-1
WQ Daily Range=0
WQ Daily Time=0
WQ Create Restart=0
WQ Fixed Restart=0
WQ System Summary=False
Sorting and Armoring Iterations= 10
XS Update Threshold= 0.02
Hydraulics Update Threshold= 0.02
Energy Slope Method= 1
Volume Change Method= 0
XS Weighting Method= 0
Number of US Weighted Cross Sections= 1
Number of DS Weighted Cross Sections= 1
Upstream XS Weight=0.25
Main XS Weight=0.5
Downstream XS Weight=0.25
Number of DS XS's Weighted with US Boundary= 1
Upstream Boundary Weight= 1
Weight of XSs Associated with US Boundary= 0
Number of US XS's Weighted with DS Boundary= 1
Downstream Boundary Weight= 0.5
Weight of XSs Associated with DS Boundary= 0.5
Sediment Output Level= 4
Mass or Volume Output= 0
Output Increment Type= 1
Profile and TS Output Increment= 10
XS Output Flag= 0
XS Output Increment= 10
Disregard all LS=0
Disregard all Conn=0
Disregard all Breaches=0
Disregard all Pumps=0

--- NortheastRiverTrib2.f01 (steady flow) ---

Flow Title=NortheastRiverTrib2_100year
Program Version=4.00
Number of Profiles= 2
Profile Names=100CUR,100ULT
River Rch & RM=NERiverTrib2,Reach1          ,5623.783
     100     100
River Rch & RM=NERiverTrib2,Reach1          ,4949.027
     128     128
River Rch & RM=NERiverTrib2,Reach1          ,4617.929
     158     158
River Rch & RM=NERiverTrib2,Reach1          ,3788.209
     203     203
River Rch & RM=NERiverTrib2,Reach1          ,3179.060
     246     246
River Rch & RM=NERiverTrib2,Reach1          ,2046.534
     309     309
River Rch & RM=NERiverTrib2,Reach1          ,1018.756
     344     344
River Rch & RM=NERiverTrib2,Reach1          ,271.5907
     431     431
Boundary for River Rch & Prof#=NERiverTrib2,Reach1          , 1
Up Type= 0
Dn Type= 3
Dn Slope=0.007
Boundary for River Rch & Prof#=NERiverTrib2,Reach1          , 2
Up Type= 0
Dn Type= 3
Dn Slope=0.007
DSS Import GetInterval= 0
DSS Import GetPeak= 0
DSS Import FillOption= 0

--- NortheastRiverTrib2.g01 (geometry) ---

Geom Title=NortheastRiverTrib2
Program Version=4.00

River Reach=NERiverTrib2    ,Reach1
Reach XY= 30
1598393.62427332703666.7675333321598910.27140619703315.059391245
1599136.65825628703252.8030074691599346.06609258702982.755836323
1599359.81100847702870.3709357381599438.23788153702851.774873048
1599477.04705584702729.6876789031599840.88306488702646.409659058
1599874.03256792702544.5355765071600035.73746085702525.939513817
1600140.84564126702350.4897050411600370.62889019702216.056391895
1600545.75628132702246.2942148151600575.99410421702299.210404933
1600504.17927478702389.9238736931600570.95446707702503.315709651
1600834.27550834 702602.84854342 1600893.4912449702709.940832913
1601005.62317157702713.7205607891601015.70244585702840.971398905
1601101.37627746702848.5308546421601154.29246756703008.539334252
1601238.70638987703065.2352522311601374.77659301702989.640694931
1601450.37115034703063.9753429441601612.89944853703079.094254419
1601683.45436865703153.4289024171601916.53758703703099.252803028
1602155.12654369702971.5632814771602329.32239503703007.079689786

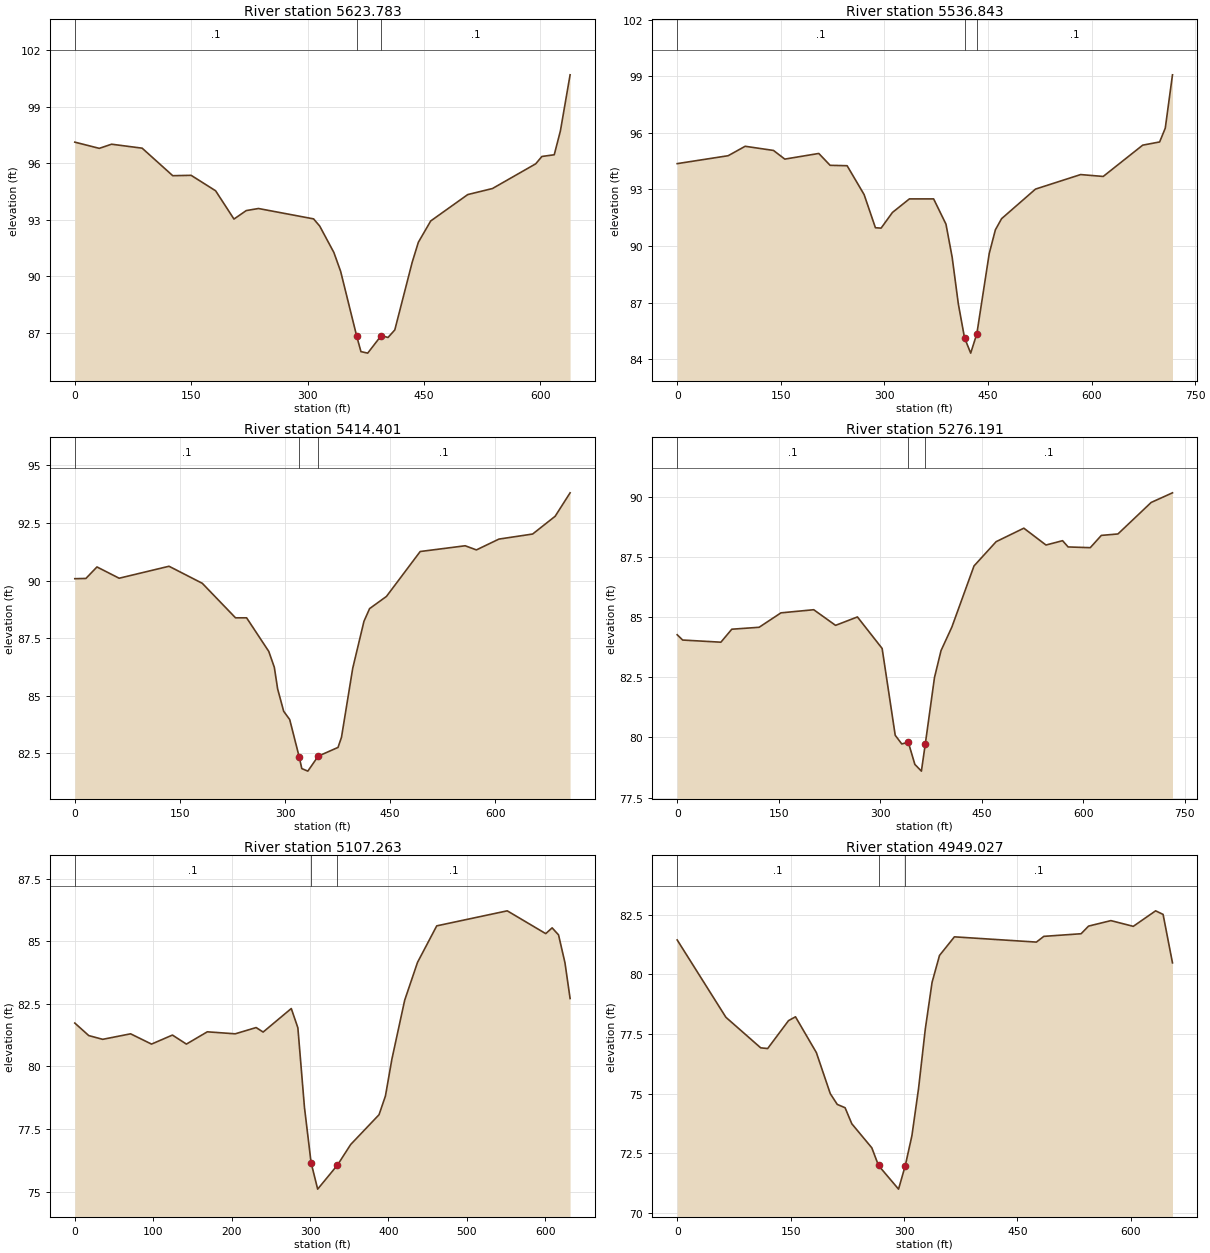
Type RM Length L Ch R = 1 ,5623.783,83.3,86.94,86.26
XS GIS Cut Line= 4
1598749.95566438703834.9132194071598461.50758298703684.996124476
1598400.78167112703603.395680383  1598214.808566 703502.81838885
#Sta/Elev= 30
       0   97.11   31.56   96.78   47.33      97   86.78   96.79  126.22   95.33
  149.89   95.35  181.45   94.53  205.11   93.03  220.89   93.48  236.67   93.59
  307.67   93.04  315.56   92.66  333.81   91.26  342.53   90.26  363.19   86.83
  368.71      86  377.43   85.92  394.89   86.85  403.61   86.75  412.34   87.15
  434.76   90.74  442.71    91.8  458.63   92.93  506.38   94.33  538.21   94.65
  593.92   95.96  601.88   96.35  617.79   96.44  625.75   97.71  638.23  100.68
#Mann= 3 , 0 , 0
       0      .1       0  363.19    .045       0  394.89      .1       0
Bank Sta=363.19,394.89
XS Rating Curve= 0 ,0
Exp/Cntr=0.3,0.1

Type RM Length L Ch R = 1 ,5536.843,122.69,122.44,118.53
XS GIS Cut Line= 4
1598839.14684746703823.5271109341598522.23349488 703629.96326685
1598455.81452878703546.4651380181598250.86457615703423.115629509
#Sta/Elev= 30
       0   94.37   73.82   94.79   98.43   95.29  139.44   95.07  155.85   94.61
  205.06   94.91  221.46   94.28  246.07   94.26  270.68   92.73  287.08   90.97
  295.29   90.95  311.69   91.78   336.3    92.5  371.35    92.5  389.24   91.16
  398.18   89.41  407.13   86.93  416.07   85.14  425.02   84.32  433.96   85.35
  451.85    89.6   460.8   90.86  469.74   91.45  518.89   93.02  584.25   93.79
  616.93   93.69  674.12   95.35  698.63   95.52   706.8   96.25  717.25   99.08
#Mann= 3 , 0 , 0
       0      .1       0  416.07    .045       0  433.96      .1       0
Bank Sta=416.07,433.96
XS Rating Curve= 0 ,0
Exp/Cntr=0.3,0.1

Type RM Length L Ch R = 1 ,5414.401,137.56,138.21,138.88
XS GIS Cut Line= 4
1598884.69128135703721.0521346481598628.50384063703586.316517681
1598575.36866775703512.3068125841598290.71595585703352.901293904
#Sta/Elev= 30
       0   90.08   15.82   90.09   31.64   90.59   63.27    90.1  134.45   90.62
  181.91   89.88  229.36   88.38  245.18   88.38  276.82   86.92  284.73   86.23
  289.46   85.29  298.07   84.32  306.69   83.96  320.21   82.34  323.93   81.83
  332.54   81.72  347.33   82.37  375.63   82.75  380.57   83.19  396.61   86.19
  412.66   88.23  420.68   88.78  444.75   89.31  492.89   91.26  557.07   91.51
  573.11   91.33  605.21    91.8  653.34   92.02  685.44   92.79  706.81   93.81
#Mann= 3 , 0 , 0
       0      .1       0  320.21    .045       0  347.33      .1       0
Bank Sta=320.21,347.33
XS Rating Curve= 0 ,0
Exp/Cntr=0.3,0.1

Type RM Length L Ch R = 1 ,5276.191,168.89,168.93,169.57
XS GIS Cut Line= 4
1598989.06394237703643.2470600611598734.77418643703497.125334606
1598656.96911184703415.5248905421598378.00945415703246.630948126
#Sta/Elev= 30
       0   84.27    8.07   84.05   64.59   83.96   80.73    84.5   121.1   84.58
  153.39   85.18  201.83   85.31  234.13   84.66  266.42   85.01  302.95    83.7
   322.3   80.09  331.97   79.73  341.64    79.8  351.32   78.88  360.99    78.6
  366.66   79.71  380.33   82.49     390   83.61  406.03   84.59  438.76   87.13
   471.5   88.14  512.41    88.7  545.14      88  569.69   88.18  577.87   87.92
  610.61   87.89  626.97    88.4  651.52   88.46  700.62   89.77  732.14   90.17
#Mann= 3 , 0 , 0
       0      .1       0  341.64    .045       0  366.66      .1       0
Bank Sta=341.64,366.66
XS Rating Curve= 0 ,0
Exp/Cntr=0.3,0.1

Type RM Length L Ch R = 1 ,5107.263,166.66,158.24,157.65
XS GIS Cut Line= 4
1599076.35744071703586.3165176811598865.71443389703421.217944786
1598812.57926102703341.5151854461598582.95940673703202.984199002
#Sta/Elev= 30
       0   81.73   17.79   81.23   35.58   81.08   71.15    81.3   97.83   80.89
  124.51   81.25   142.3   80.89  168.98   81.38  204.56    81.3  231.24   81.55
  240.14   81.37  276.05   82.31  284.46   81.54  292.87   78.36  301.29   76.16
   309.7    75.1  334.94   76.06  351.76   76.88  387.95   78.07  396.13   78.82
   404.3   80.28  420.65   82.64     437   84.15  461.53   85.61  551.46   86.21
  600.51    85.3  608.68   85.53  616.86   85.25  625.03   84.14   631.6   82.71
#Mann= 3 , 0 , 0
       0      .1       0  301.29    .045       0  334.94      .1       0
Bank Sta=301.29,334.94
XS Rating Curve= 0 ,0
Exp/Cntr=0.3,0.1

Type RM Length L Ch R = 1 ,4949.027,318.83,331.1,314.11
XS GIS Cut Line= 4
1599178.83241701703499.0230193591599009.93847463703354.798978657
1598939.72413902703263.7101108581598715.79733896703037.885626078
#Sta/Elev= 30
       0   81.44   64.43    78.2  110.46   76.92  119.66   76.89  147.28   78.06
  156.48   78.22   184.1   76.72  202.51      75  211.71   74.55  222.09   74.41
  230.93   73.74  257.45   72.73  266.29   71.99   292.8      71  301.64   71.98
  310.48   73.24  319.31   75.23  328.15    77.7   337.1   79.66  346.96   80.79
  366.68   81.57  475.12   81.35  484.97   81.59  534.26    81.7  544.12   82.02
   573.7   82.25  603.27   82.01  632.84   82.66   642.7   82.51  655.13   80.48
#Mann= 3 , 0 , 0
       0      .1       0  266.29    .045       0  301.64      .1       0
Bank Sta=266.29,301.64
XS Rating Curve= 0 ,0
Exp/Cntr=0.3,0.1

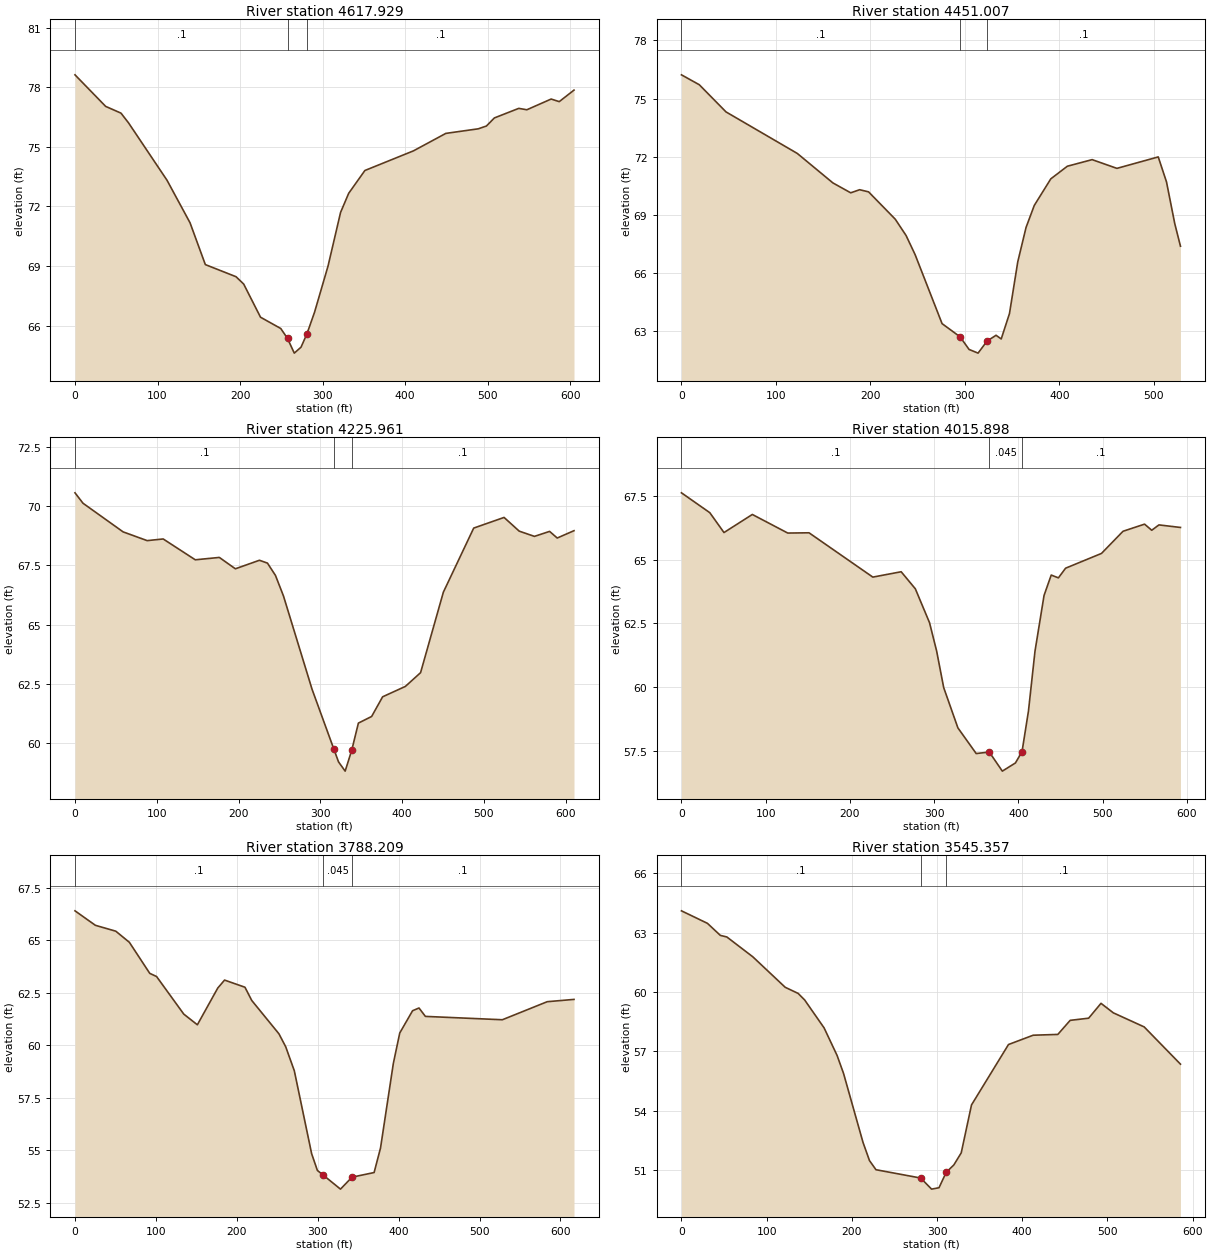
Type RM Length L Ch R = 1 ,4617.929,164.95,166.92,159.24
XS GIS Cut Line= 4
1599374.29394583 703328.231392221599231.96758989703165.030504048
1599182.62778652703083.4300599841598973.88246442702878.480107397
#Sta/Elev= 30
       0   78.63   37.15   77.04   55.73    76.7   65.02    76.2  111.46   73.32
  139.32   71.18   157.9   69.07  195.05   68.46  204.34   68.09  224.72   66.42
  249.26   65.85  257.44   65.35  265.62   64.61   273.8   64.91  280.94   65.58
  290.17   66.67  306.53      69  321.71    71.7  331.52   72.66  351.14   73.81
     410    74.8  449.24   75.68  488.48   75.91  498.29   76.05   508.1   76.46
  537.53   76.94  547.34   76.87  576.77   77.41  586.58   77.28  604.44   77.86
#Mann= 3 , 0 , 0
       0      .1       0  257.44    .045       0  280.94      .1       0
Bank Sta=257.44,280.94
XS Rating Curve= 0 ,0
Exp/Cntr=0.3,0.1

Type RM Length L Ch R = 1 ,4451.007,192.97,225.05,200.35
XS GIS Cut Line= 4
 1599509.0295628703229.5517854241599349.62404412703053.067104027
 1599281.3073933 702979.057398931599167.44630852702827.242619261
#Sta/Elev= 30
       0   76.22   18.87   75.71   47.16   74.31  122.62   72.17  160.36   70.65
  179.22   70.14  188.65    70.3  198.09   70.19  226.38   68.78  237.82   67.94
  247.34   66.96  275.92    63.4  294.98   62.72   304.5   62.07  314.03   61.88
  323.55    62.5  333.08    62.8  338.54   62.61  347.29   63.92  356.04   66.58
  364.79   68.35  373.54   69.49  391.04   70.86  408.54   71.51  434.79   71.85
  461.04    71.4  504.79   71.99  513.54    70.7  522.29   68.55  528.31   67.39
#Mann= 3 , 0 , 0
       0      .1       0  294.98    .045       0  323.55      .1       0
Bank Sta=294.98,323.55
XS Rating Curve= 0 ,0
Exp/Cntr=0.3,0.1

Type RM Length L Ch R = 1 ,4225.961,197.21,210.06,209.54
XS GIS Cut Line= 4
1599641.86749505703108.0999616681599444.50828144702906.945378602
1599397.06616281702825.3449345231599243.35369837 702648.86025314
#Sta/Elev= 30
       0   70.57    9.81   70.13   58.84   68.92   88.26   68.55  107.87   68.62
   147.1   67.74  176.52   67.84  196.13   67.36  225.55   67.72  235.36    67.6
  245.16   67.08  254.97   66.21   289.9   62.27  316.35   59.76  322.29    59.2
  330.39   58.81  338.48    59.7  346.58   60.84  362.78   61.12  376.19   61.95
  404.04   62.39  422.61   62.97  450.46   66.37  487.59   69.08  524.72   69.53
  543.28   68.95  561.85   68.73  580.42   68.94   589.7   68.66  610.23   68.97
#Mann= 3 , 0 , 0
       0      .1       0  316.35    .045       0  338.48      .1       0
Bank Sta=316.35,338.48
XS Rating Curve= 0 ,0
Exp/Cntr=0.3,0.1

Type RM Length L Ch R = 1 ,4015.898,196.95,227.69,218.84
XS GIS Cut Line= 4
1599732.95636284703037.8856260781599543.18788826702753.232914165
1599505.23419334702673.5301548241599410.34995602702536.896853119
#Sta/Elev= 30
       0   67.62   33.65   66.84   50.48   66.06   84.13   66.77  126.19   66.04
  151.43   66.05  227.15   64.31   260.8   64.52  277.63   63.85  294.45   62.52
  302.87   61.41  311.28   59.97  328.11   58.39  349.86   57.38  365.37   57.44
  380.88   56.69  396.38   57.01  404.23   57.45  411.89   59.05  419.64    61.4
  430.39   63.59  438.91   64.39  447.43   64.28  455.96   64.66  498.57   65.24
  524.13   66.11   549.7   66.39  558.22   66.15  566.75   66.36  592.31   66.26
#Mann= 3 , 0 , 0
       0      .1       0  365.37    .045       0  404.23      .1       0
Bank Sta=365.37,404.23
XS Rating Curve= 0 ,0
Exp/Cntr=0.3,0.1

Type RM Length L Ch R = 1 ,3788.209,241.15,242.85,212.92
XS GIS Cut Line= 4
1599882.87345777702946.7967582491599732.95636284702720.972273484
1599713.97951539702624.1903514271599598.22074588702405.956605628
#Sta/Elev= 30
       0    66.4   25.21   65.71   50.41   65.43   67.22    64.9   92.42   63.42
  100.83   63.27  134.43   61.48  151.24   60.97  176.44   62.72  184.85    63.1
  210.05   62.76  218.45   62.13  252.06   60.54  260.46   59.92  271.06   58.78
  292.46   54.83  299.59   54.03  306.72   53.81  328.12   53.14  342.39   53.71
  369.68   53.93  377.61    55.1  393.45   59.13  401.38   60.58  417.22   61.64
  425.15   61.77  433.07   61.37  528.16   61.21  583.62   62.07  616.72   62.18
#Mann= 3 , 0 , 0
       0      .1       0  306.72    .045       0  342.39      .1       0
Bank Sta=306.72,342.39
XS Rating Curve= 0 ,0
Exp/Cntr=0.3,0.1

Type RM Length L Ch R = 1 ,3545.357,150.58,165.46,143.68
XS GIS Cut Line= 4
1600011.91602056702802.5727175471599917.03178324702580.543602258
1599858.20355612702500.8408429471599795.57995948702263.630249664
#Sta/Elev= 30
       0    64.1   30.45   63.47   45.67   62.86   53.29   62.78   83.74   61.78
   121.8   60.24  137.02   59.93  144.64    59.6  167.47   58.19   182.7    56.8
  190.31   55.89  213.15   52.41  220.76   51.49  228.37   51.03  280.86   50.61
  293.66   50.05  302.36   50.12  310.85    50.9  319.76   51.27  328.46   51.88
  340.52    54.3  383.95   57.35  412.91   57.82  441.87   57.86  456.35   58.57
  478.07   58.68  492.55   59.43  507.03   58.95  543.23   58.24  585.85   56.36
#Mann= 3 , 0 , 0
       0      .1       0  280.86    .045       0  310.85      .1       0
Bank Sta=280.86,310.85
XS Rating Curve= 0 ,0
Exp/Cntr=0.3,0.1

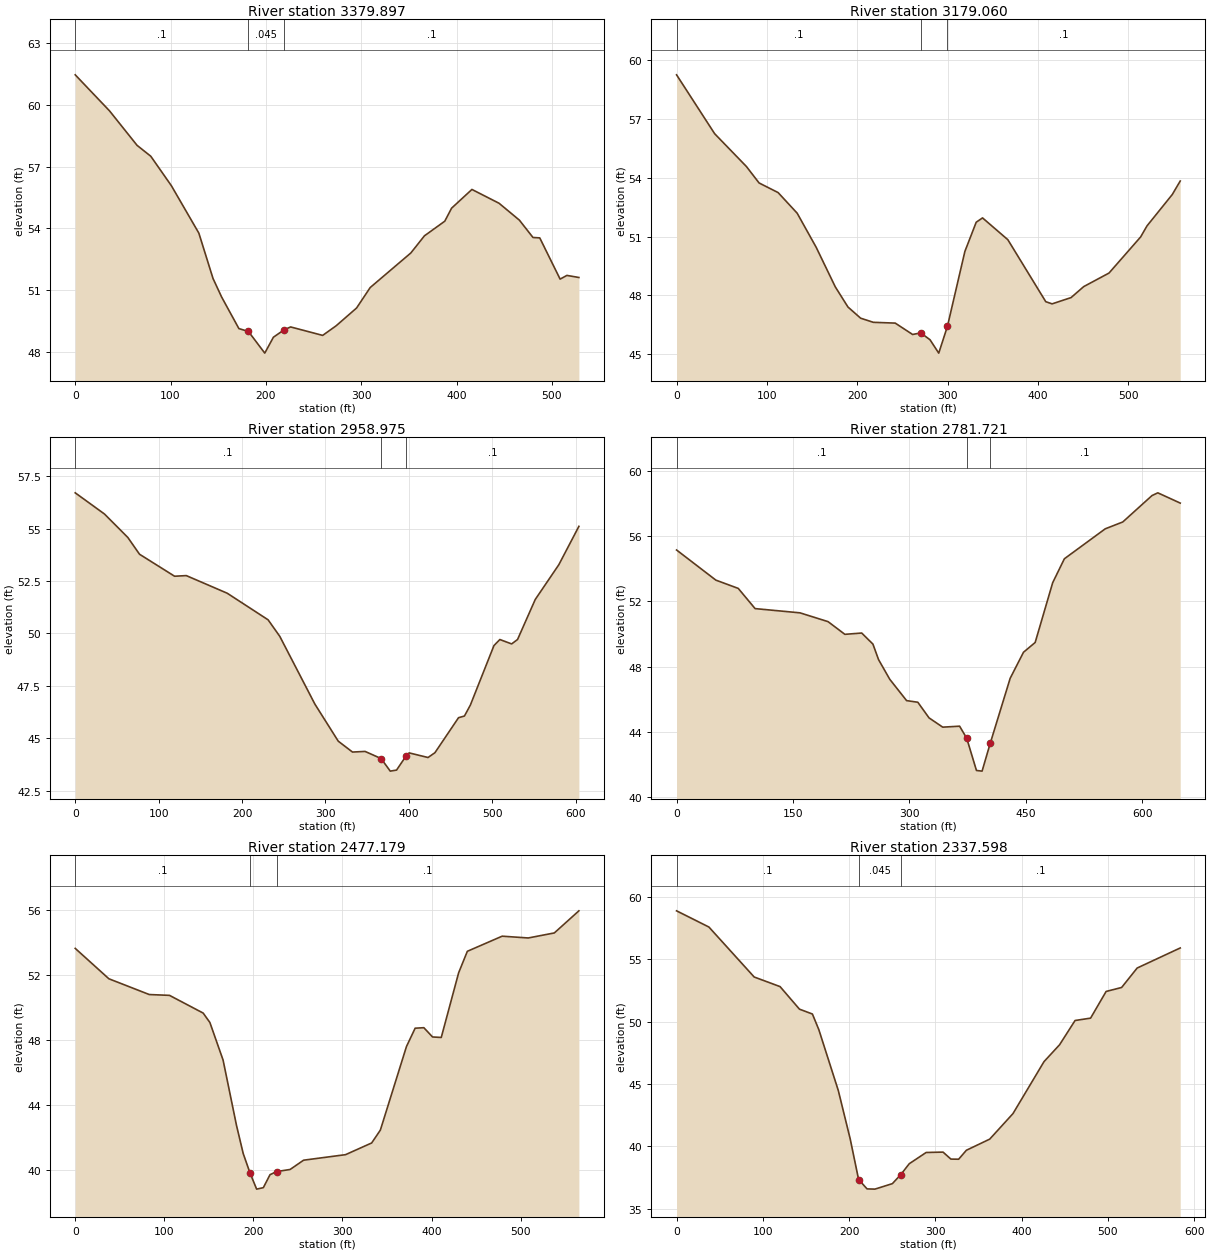
Type RM Length L Ch R = 1 ,3379.897,184.43,200.84,177.2
XS GIS Cut Line= 4
1600104.90257308702707.6884802581600070.74424767702567.259809047
1600002.42759679702483.7616802161599953.08779338702212.392761543
#Sta/Elev= 30
       0   61.45   36.02    59.7   64.84   58.03   79.25    57.5  100.86   56.07
  129.67   53.77  144.52   51.57  153.57   50.67  171.66   49.14  181.66      49
  198.79   47.95  207.83   48.72     219   49.08  225.92   49.22  259.52   48.81
  273.75   49.28   295.1   50.14  309.33   51.13  352.01   52.81  366.24   53.64
  387.59   54.35   394.7   54.98  416.05   55.89  444.51   55.22  465.85    54.4
  480.08   53.56   487.2   53.54  508.54   51.54  515.65   51.72  528.23   51.62
#Mann= 3 , 0 , 0
       0      .1       0  181.66    .045       0     219      .1       0
Bank Sta=181.66,219
XS Rating Curve= 0 ,0
Exp/Cntr=0.3,0.1

Type RM Length L Ch R = 1 ,3179.060,176.19,220.09,214.44
XS GIS Cut Line= 4
1600188.40070191  702635.57645991600167.52616972702404.058920875
1600099.20951883702331.9469005321600093.51646459702106.122415766
#Sta/Elev= 30
       0   59.24   42.17   56.24   77.31   54.57   91.37   53.73  112.45   53.24
  133.54   52.19  154.62   50.45  175.71   48.44  189.77   47.41  203.82   46.84
  217.88   46.63   242.1   46.59  261.38   46.01  270.42   46.09  280.67   45.74
  290.31   45.06  299.95   46.43  319.24   50.24  331.79   51.73  338.79   51.95
   366.8   50.84  408.82   47.68  415.82   47.57  436.82   47.89  450.83   48.45
  478.84   49.14  513.85   50.98  520.85   51.54  548.86   53.14  557.69   53.83
#Mann= 3 , 0 , 0
       0      .1       0  270.42    .045       0  299.95      .1       0
Bank Sta=270.42,299.95
XS Rating Curve= 0 ,0
Exp/Cntr=0.3,0.1

Type RM Length L Ch R = 1 ,2958.975,158.24,177.25,189.57
XS GIS Cut Line= 4
1600283.28493923702618.4972971831600298.46641718702293.993205607
1600258.61503752702195.3135988121600283.28493923702024.521971658
#Sta/Elev= 30
       0   56.71   35.04    55.7   63.07   54.58   77.08   53.78  119.13   52.73
  133.15   52.76   182.2   51.92  231.25   50.65  245.27   49.86  287.31   46.63
  315.34   44.86  332.41   44.34  347.51   44.37  366.72   44.03   377.7   43.43
  385.25   43.48  396.79   44.16  400.35    44.3     423   44.08  431.28   44.31
  459.57   45.98  466.65   46.06  473.72   46.58  502.01   49.42  509.08   49.71
  523.23    49.5   530.3   49.71  551.52   51.62  579.81   53.28  603.85   55.11
#Mann= 3 , 0 , 0
       0      .1       0  366.72    .045       0  396.79      .1       0
Bank Sta=366.72,396.79
XS Rating Curve= 0 ,0
Exp/Cntr=0.3,0.1

Type RM Length L Ch R = 1 ,2781.721,200.74,304.54,288.74
XS GIS Cut Line= 4
1600351.60159005702601.4181344811600436.99740367702269.323303908
 1600463.5649901702168.7460123751600537.57469517701980.875222519
#Sta/Elev= 30
       0   55.16   50.59   53.31    79.5    52.8  101.19   51.56  159.01    51.3
  195.15   50.76  216.83   49.98  238.51   50.06  252.97   49.38   260.2   48.43
  274.65   47.22  296.34   45.91  310.79   45.81  325.25   44.85   342.9   44.28
  364.62   44.34   373.8    43.6  386.34   41.62  393.58   41.58  404.04   43.28
  429.78   47.28  446.93   48.88  461.97   49.48  484.54   53.15  499.59   54.62
  552.26   56.46  574.83   56.88  612.44    58.5  619.97   58.67  648.85   58.04
#Mann= 3 , 0 , 0
       0      .1       0   373.8    .045       0  404.04      .1       0
Bank Sta=373.8,404.04
XS Rating Curve= 0 ,0
Exp/Cntr=0.3,0.1

Type RM Length L Ch R = 1 ,2477.179,170.16,139.58,121.32
XS GIS Cut Line= 4
1600399.04370874702571.0551785531600461.66730537702417.342714101
1600562.24459688702377.4913344381600765.29686473702168.746012375
#Sta/Elev= 30
       0   53.63   37.79   51.76   83.15   50.79  105.82   50.74  143.61   49.65
  151.17   49.07  165.98   46.76  181.04   42.74  188.57   41.01   196.1   39.83
  203.63   38.82  211.16   38.91  218.69   39.71  226.22    39.9  241.27   40.03
  256.33    40.6  303.46   40.94  332.76   41.66  342.52   42.45  371.82   47.59
  381.58   48.72  391.35   48.75  401.12   48.18  410.88   48.15  430.41   52.13
  440.18   53.45  479.24   54.38  508.53   54.27  537.83   54.58  565.38   55.94
#Mann= 3 , 0 , 0
       0      .1       0   196.1    .045       0  226.22      .1       0
Bank Sta=196.1,226.22
XS Rating Curve= 0 ,0
Exp/Cntr=0.3,0.1

Type RM Length L Ch R = 1 ,2337.598,136.82,118.69,107.4
XS GIS Cut Line= 4
1600467.36035956702722.8699582371600539.47237995702534.999168366
1600622.97050872702453.3987242881600789.96676643702246.551086947
#Sta/Elev= 30
       0   58.89   37.49   57.59   89.98   53.58  119.97   52.81  142.46      51
  157.46   50.61  164.95   49.35  187.45   44.48  201.24    40.6  211.02   37.33
  220.81   36.58  229.91   36.56  250.17      37  259.96   37.73  269.75    38.6
  289.32    39.5   308.9   39.53  317.99   38.97  326.98   38.96  335.98   39.68
  362.97   40.57  389.96   42.62  425.94   46.79  443.94   48.14  461.93   50.09
  479.92   50.28  497.92   52.42  515.91   52.74   533.9    54.3  583.83   55.91
#Mann= 3 , 0 , 0
       0      .1       0  211.02    .045       0  259.96      .1       0
Bank Sta=211.02,259.96
XS Rating Curve= 0 ,0
Exp/Cntr=0.3,0.1

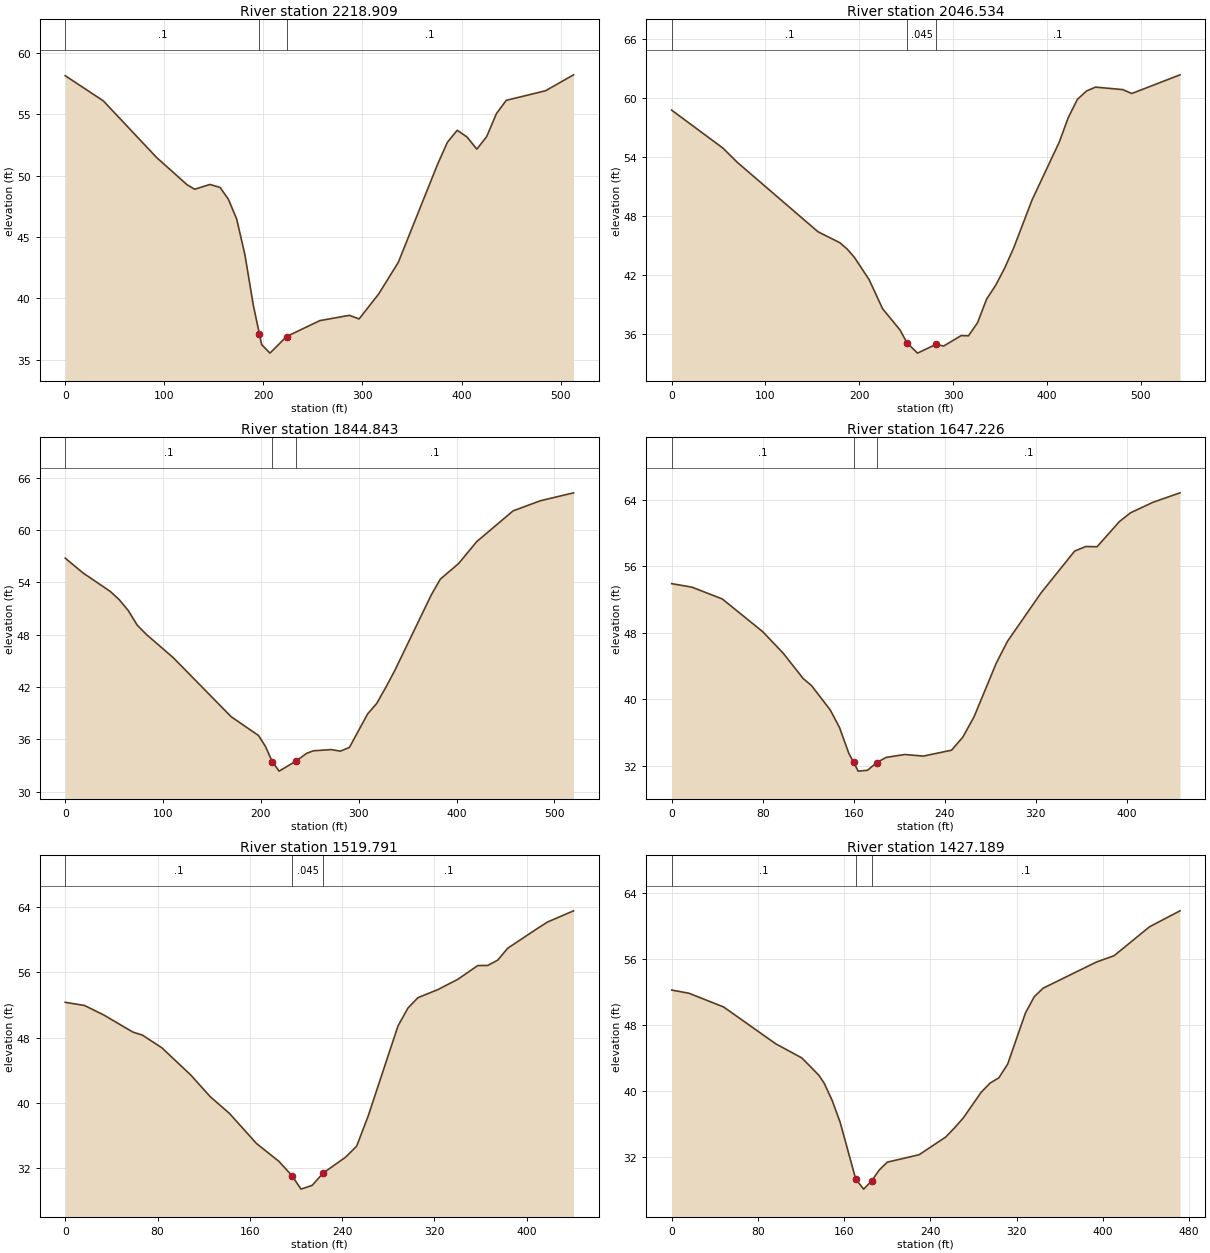
Type RM Length L Ch R = 1 ,2218.909,165.21,172.38,175.81
XS GIS Cut Line= 4
1600573.63070537702739.9491209391600638.15198673 702597.62276499
1600704.57095282702497.0454734561600871.56721048702330.049215779
#Sta/Elev= 30
       0   58.15   38.43    56.1   92.23   51.48  122.97   49.26  130.66   48.89
  146.03   49.28  156.27   49.04  164.66   48.08  173.05   46.46  181.43   43.52
  189.82   39.44  195.97    37.1  198.21   36.23   206.6   35.53  223.38   36.88
  256.93   38.18   286.7   38.61   296.6   38.32   316.4   40.36  336.19   42.94
  375.79   50.93  385.69   52.72  395.59    53.7  405.49   53.15  415.39   52.16
  425.29   53.18  435.19   55.06  445.09   56.14  484.69   56.92  512.97   58.22
#Mann= 3 , 0 , 0
       0      .1       0  195.97    .045       0  223.38      .1       0
Bank Sta=195.97,223.38
XS Rating Curve= 0 ,0
Exp/Cntr=0.3,0.1

Type RM Length L Ch R = 1 ,2046.534,200.55,201.69,144.8
XS GIS Cut Line= 4
1600698.87789857702831.0379887371600793.76213589702637.474144652
1600860.18110204702561.5667548031601015.79125121702398.365866661
#Sta/Elev= 30
       0   58.78   54.57   54.93   70.16   53.46  155.92   46.43   179.3   45.31
   187.1   44.67  194.89   43.81  210.49   41.56  224.87    38.6  243.47   36.44
  250.81   35.15  262.08   34.09   281.8   34.98  289.98   34.81  308.58   35.87
  316.43   35.85   326.1   37.18  335.78   39.58  345.45   40.99  355.12   42.75
  364.79   44.82  384.14   49.64  413.15   55.52  422.82   58.02   432.5   59.87
  442.17   60.72  451.84   61.12  480.86   60.87  490.53   60.47  541.93   62.37
#Mann= 3 , 0 , 0
       0      .1       0  250.81    .045       0   281.8      .1       0
Bank Sta=250.81,281.8
XS Rating Curve= 0 ,0
Exp/Cntr=0.3,0.1

Type RM Length L Ch R = 1 ,1844.843,161.28,197.62,179.78
XS GIS Cut Line= 4
1600835.51120034 702899.354639621600945.57691561702770.312076867
1600943.67923082 702677.325524331601137.24307491702508.431581929
#Sta/Elev= 30
       0   56.78    18.4   55.07      46   52.97    55.2   52.02    64.4   50.78
    73.6    49.1    82.8   48.05  110.41   45.37  169.61    38.6  197.61   36.44
  204.61    35.2  211.62   33.44  218.62   32.36  236.01   33.52  246.62   34.39
  253.62   34.69   271.9   34.83  281.19   34.65  290.48   35.08  309.06   38.92
  318.35   40.12  327.64   41.96  336.93   43.92  374.09   52.56  383.38   54.38
  401.96   56.15  420.54   58.67   457.7    62.2  485.58   63.36   519.5   64.27
#Mann= 3 , 0 , 0
       0      .1       0  211.62    .045       0  236.01      .1       0
Bank Sta=211.62,236.01
XS Rating Curve= 0 ,0
Exp/Cntr=0.3,0.1

Type RM Length L Ch R = 1 ,1647.226,111.95,127.43,115.26
XS GIS Cut Line= 4
1600915.21395965702980.955083698 1600991.1213495702884.173161626
1601049.94957662702787.3912395981601197.96898681702637.474144652
#Sta/Elev= 30
       0   53.89   17.79   53.47   44.48   52.05   80.07   48.11   97.86   45.55
  115.65   42.47     123   41.62  139.38    38.7  147.57   36.58  155.77   33.46
  159.92   32.41  163.96   31.33  172.15   31.43  180.34   32.36  188.53   32.98
  204.92   33.33   221.3   33.14  246.09   33.85  255.93   35.41  265.77   37.84
  285.44   44.34  295.28   46.96  324.79   52.78   354.3   57.81  364.14   58.36
  373.98   58.33  393.65   61.36  403.49   62.42  423.16   63.68  446.93   64.82
#Mann= 3 , 0 , 0
       0      .1       0  159.92    .045       0  180.34      .1       0
Bank Sta=159.92,180.34
XS Rating Curve= 0 ,0
Exp/Cntr=0.3,0.1

Type RM Length L Ch R = 1 ,1519.791,75.92,92.6,97.96
XS GIS Cut Line= 4
1600998.71208848703049.2717345511601089.80095628702910.740748078
1601156.21992242702840.5264124721601260.59258345 702696.30237177
#Sta/Elev= 30
       0   52.32   16.76   51.93   33.51   50.76   58.64   48.67   67.02   48.29
   83.78   46.74  108.91   43.39  125.66   40.75  142.42   38.68   165.8      35
  185.07   32.83  196.41   31.08  204.34   29.41  213.97   29.87  223.61   31.39
  242.88   33.32  252.52   34.67  262.45   38.34  288.37   49.42  297.01   51.62
  305.65   52.89  322.93   53.88  340.21   55.14  357.49   56.83  366.14   56.84
  374.78   57.49  383.42   58.95  409.34   61.39  417.98   62.17  440.48   63.54
#Mann= 3 , 0 , 0
       0      .1       0  196.41    .045       0  223.61      .1       0
Bank Sta=196.41,223.61
XS Rating Curve= 0 ,0
Exp/Cntr=0.3,0.1

Type RM Length L Ch R = 1 ,1427.189,19.52,19.89,20.8
XS GIS Cut Line= 4
1601032.14666052 703096.676923291601101.83281566702973.386033431
1601178.21956261702950.6040211771601309.55116269 702737.52520071
#Sta/Elev= 30
       0   52.26   16.08   51.87   48.24    50.2   96.49   45.73  120.61   44.02
  128.65   42.97  136.69   41.88  141.62   40.91  148.93   38.83  156.23   36.22
  170.84   29.26  178.15   28.06  185.45   29.05  192.75   30.41  200.06   31.34
  229.56   32.24  254.23   34.39  262.45   35.51  270.67   36.73  287.12   39.83
  295.34   40.94  303.56   41.59  311.78   43.27  328.23   49.47  336.45   51.46
  344.68   52.49  394.01   55.66  410.46   56.43  443.35   59.95  471.63   61.89
#Mann= 3 , 0 , 0
       0      .1       0  170.84    .045       0  185.45      .1       0
Bank Sta=170.84,185.45
XS Rating Curve= 0 ,0
Exp/Cntr=0.3,0.1

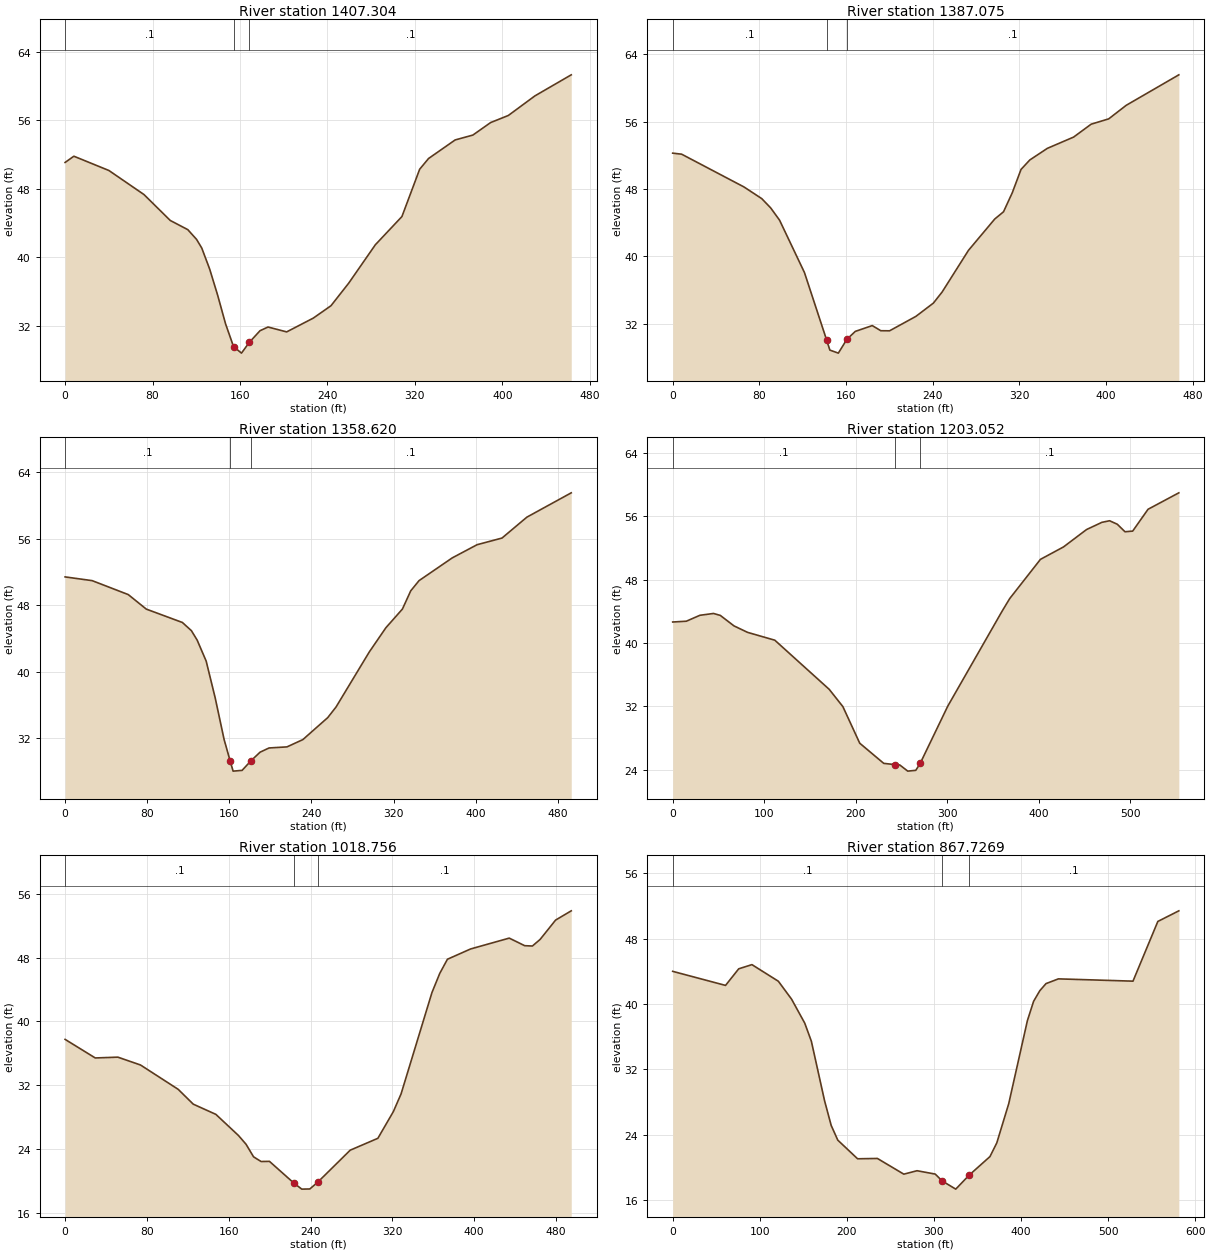
Type RM Length L Ch R = 1 ,1407.304,22.94,20.23,18.09
XS GIS Cut Line= 5
 1601045.5736991703101.0010730481601106.55354068702991.879251361
1601157.90498619702977.4366573241601181.17360994702970.215360314
1601312.76168898702745.552786246
#Sta/Elev= 30
       0   51.08    8.02   51.81   40.09   50.14   72.17   47.33   96.23    44.3
  112.26   43.23  120.28   42.09     125   41.09  132.28   38.62  139.55   35.58
  146.82   32.22  154.09   29.57  161.36    28.8  168.63   30.07  178.35   31.42
  185.68   31.85  202.71   31.28  227.05   32.89  243.27   34.34   259.5   36.98
  283.84   41.46  308.17   44.76   324.4   50.29  332.51   51.54  356.85   53.71
  373.07   54.28   389.3   55.74  405.52   56.57  429.86   58.86  463.07   61.32
#Mann= 3 , 0 , 0
       0      .1       0  154.09    .045       0  168.63      .1       0
Bank Sta=154.09,168.63
XS Rating Curve= 0 ,0
Exp/Cntr=0.3,0.1

Type RM Length L Ch R = 1 ,1387.075,34.84,28.45,21.41
XS GIS Cut Line= 4
1601053.60982257703115.2568176391601113.37708747703018.392629713
 1601183.4490532702983.3566468511601321.53204441702745.318057463
#Sta/Elev= 30
       0   52.26    8.23   52.14    65.8   48.25   82.25   46.86   90.48   45.76
    98.7    44.3  121.65   38.09  142.05   30.11  145.12   28.88  152.95   28.52
  160.78   30.15   168.6    31.1  184.26   31.79  192.16   31.18  200.25   31.17
  224.53   32.88  240.72   34.46  248.81   35.78  273.09   40.72  297.36   44.44
  305.46    45.3  313.55   47.56  321.64   50.33  329.73   51.45  345.92   52.83
   370.2   54.17  386.38    55.7  402.57   56.33  418.75   57.94  467.35   61.56
#Mann= 3 , 0 , 0
       0      .1       0  142.05    .045       0  160.78      .1       0
Bank Sta=142.05,160.78
XS Rating Curve= 0 ,0
Exp/Cntr=0.3,0.1

Type RM Length L Ch R = 1 ,1358.620,168.62,155.57,142.82
XS GIS Cut Line= 4
1601065.13105457703157.4397650811601142.93612915703054.964788795
1601199.86667155 702979.057398931601334.60228851702745.642175183
#Sta/Elev= 30
       0   51.41   26.37   50.96   61.52   49.28    79.1   47.53  114.26   45.92
  123.05   44.93  128.67   43.79  137.42   41.27  146.17   36.86  154.92   31.81
   160.9   29.19  163.67   28.01  172.42    28.1  181.17   29.27  189.92   30.29
  198.67    30.8  216.17   30.93  231.63   31.81  255.88   34.46  263.96   35.74
  296.29   42.36  312.46   45.28  328.62   47.54   336.7   49.73  344.79   50.96
  377.12    53.7  401.36   55.29  425.61   56.09  449.86   58.61  493.06   61.54
#Mann= 3 , 0 , 0
       0      .1       0   160.9    .045       0  181.17      .1       0
Bank Sta=160.9,181.17
XS Rating Curve= 0 ,0
Exp/Cntr=0.3,0.1

Type RM Length L Ch R = 1 ,1203.052,174.75,184.3,190.09
XS GIS Cut Line= 4
1601264.38795291703261.8124261051601330.80691905 703077.73700574
1601262.49026819702986.6481379121601397.22588515702783.595870093
#Sta/Elev= 30
       0   42.66   14.88   42.76   29.77   43.51   44.65   43.74   52.09   43.49
   66.98   42.17   81.86   41.35  111.63   40.36  171.16   34.14  186.04   31.96
  204.44   27.34  230.69   24.79   243.2   24.63  248.19   24.59  256.94   23.81
  265.69   23.91  270.49   24.78  300.69   32.03  359.96   44.01  368.36   45.62
  401.96   50.58  427.17   52.15  452.37   54.35  469.17   55.26  477.57   55.46
  485.97   55.02  494.37   54.07  502.77   54.15  519.57   56.91  553.24   58.99
#Mann= 3 , 0 , 0
       0      .1       0   243.2    .045       0  270.49      .1       0
Bank Sta=243.2,270.49
XS Rating Curve= 0 ,0
Exp/Cntr=0.3,0.1

Type RM Length L Ch R = 1 ,1018.756,139.51,151.03,141.9
XS GIS Cut Line= 4
1601355.47682071703278.8915888071601418.10041735703089.123114228
1601463.64485125703001.8296158911601537.65455636702819.651880279
#Sta/Elev= 30
       0   37.76   29.49   35.43    51.6   35.53   73.71   34.55  110.57    31.5
  125.31   29.64  147.43   28.36  169.54   25.71  176.91   24.62  184.28   23.04
  191.65   22.45  199.83   22.47  223.52   19.77  231.42   18.99  239.31   19.01
  247.21   19.88  278.79   23.87  305.85   25.36  320.96    28.7  328.52   30.92
  358.74   43.63   366.3   46.01  373.85    47.8  396.52   49.09   434.3   50.45
  449.41    49.5  456.96   49.46  464.52   50.29  479.63   52.71  494.93   53.87
#Mann= 3 , 0 , 0
       0      .1       0  223.52    .045       0  247.21      .1       0
Bank Sta=223.52,247.21
XS Rating Curve= 0 ,0
Exp/Cntr=0.3,0.1

Type RM Length L Ch R = 1 ,867.7269,98.82,100.93,101.77
XS GIS Cut Line= 4
1601444.66800384703366.185087144 1601554.7337191703102.406907424
  1601600.278153703013.2157243791601638.23184788702821.549565017
#Sta/Elev= 30
       0      44   60.68   42.28   75.85   44.31   91.02   44.82  121.36   42.79
  136.53    40.6   151.7   37.66  159.28   35.45  174.45   28.17  182.04   25.16
  189.62   23.36  212.38   21.08  235.13   21.12  265.47    19.2  280.64   19.62
  301.54   19.21  309.63   18.36  325.12   17.37  340.62   19.09  364.42   21.35
  372.28   23.03  385.97   27.82  407.38   37.96  414.51   40.33  421.65   41.63
  428.78    42.5  443.05   43.08  528.69    42.8  557.23    50.1  581.36    51.4
#Mann= 3 , 0 , 0
       0      .1       0  309.63    .045       0  340.62      .1       0
Bank Sta=309.63,340.62
XS Rating Curve= 0 ,0
Exp/Cntr=0.3,0.1