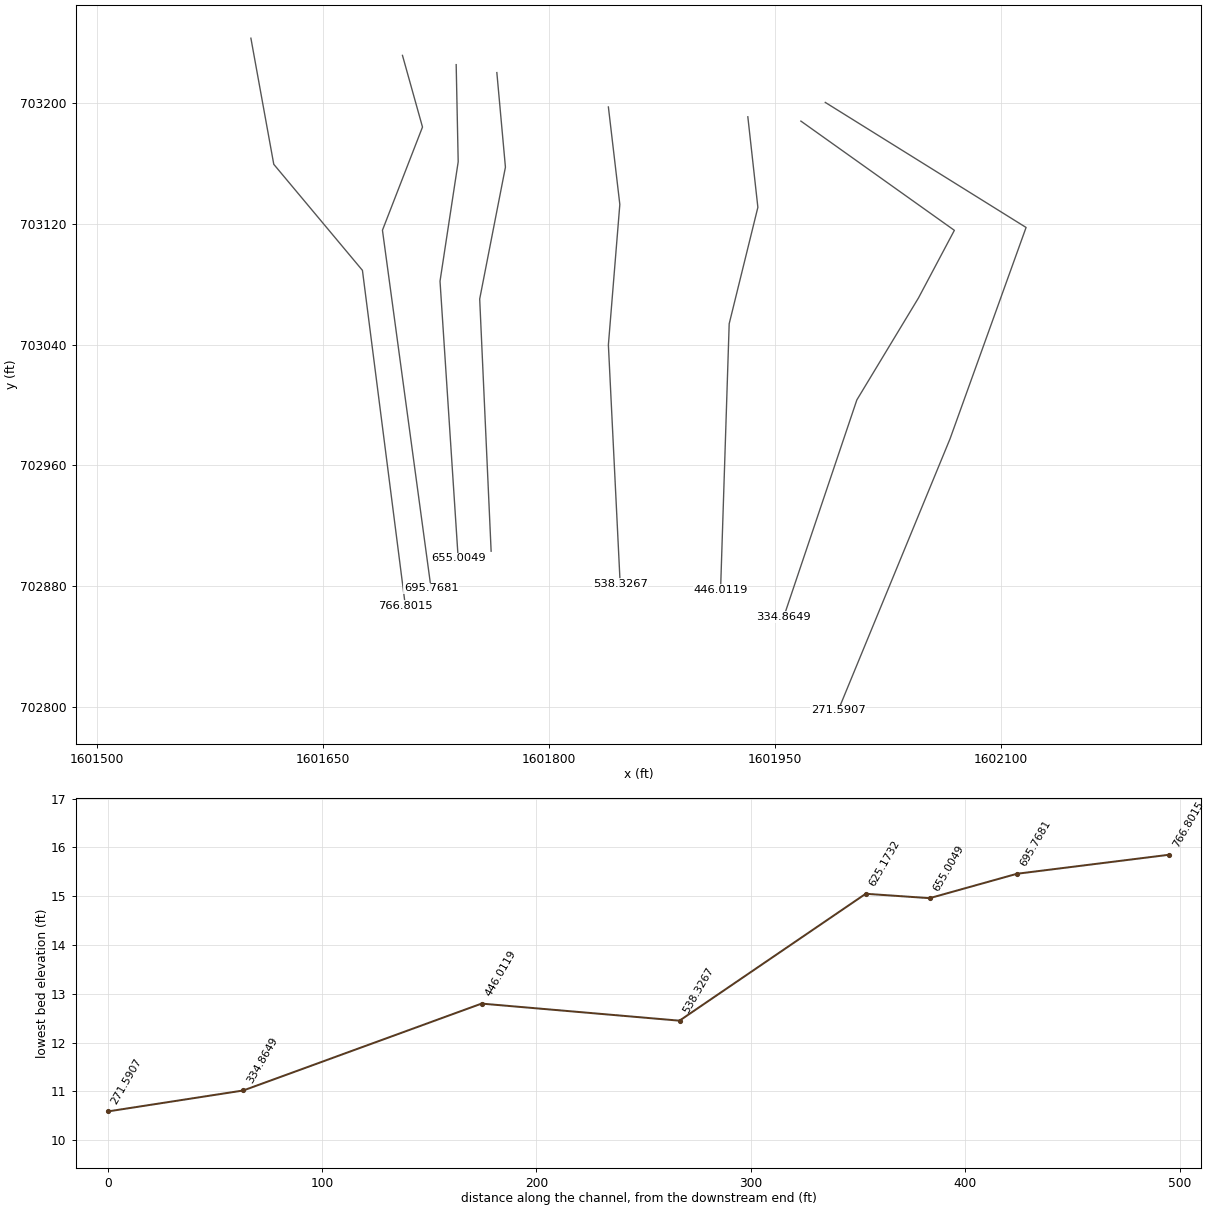
HEC-RAS study NortheastRiverTrib2.prj: NortheastRiverTrib2

--- NortheastRiverTrib2.g01 (geometry) --- (continued)

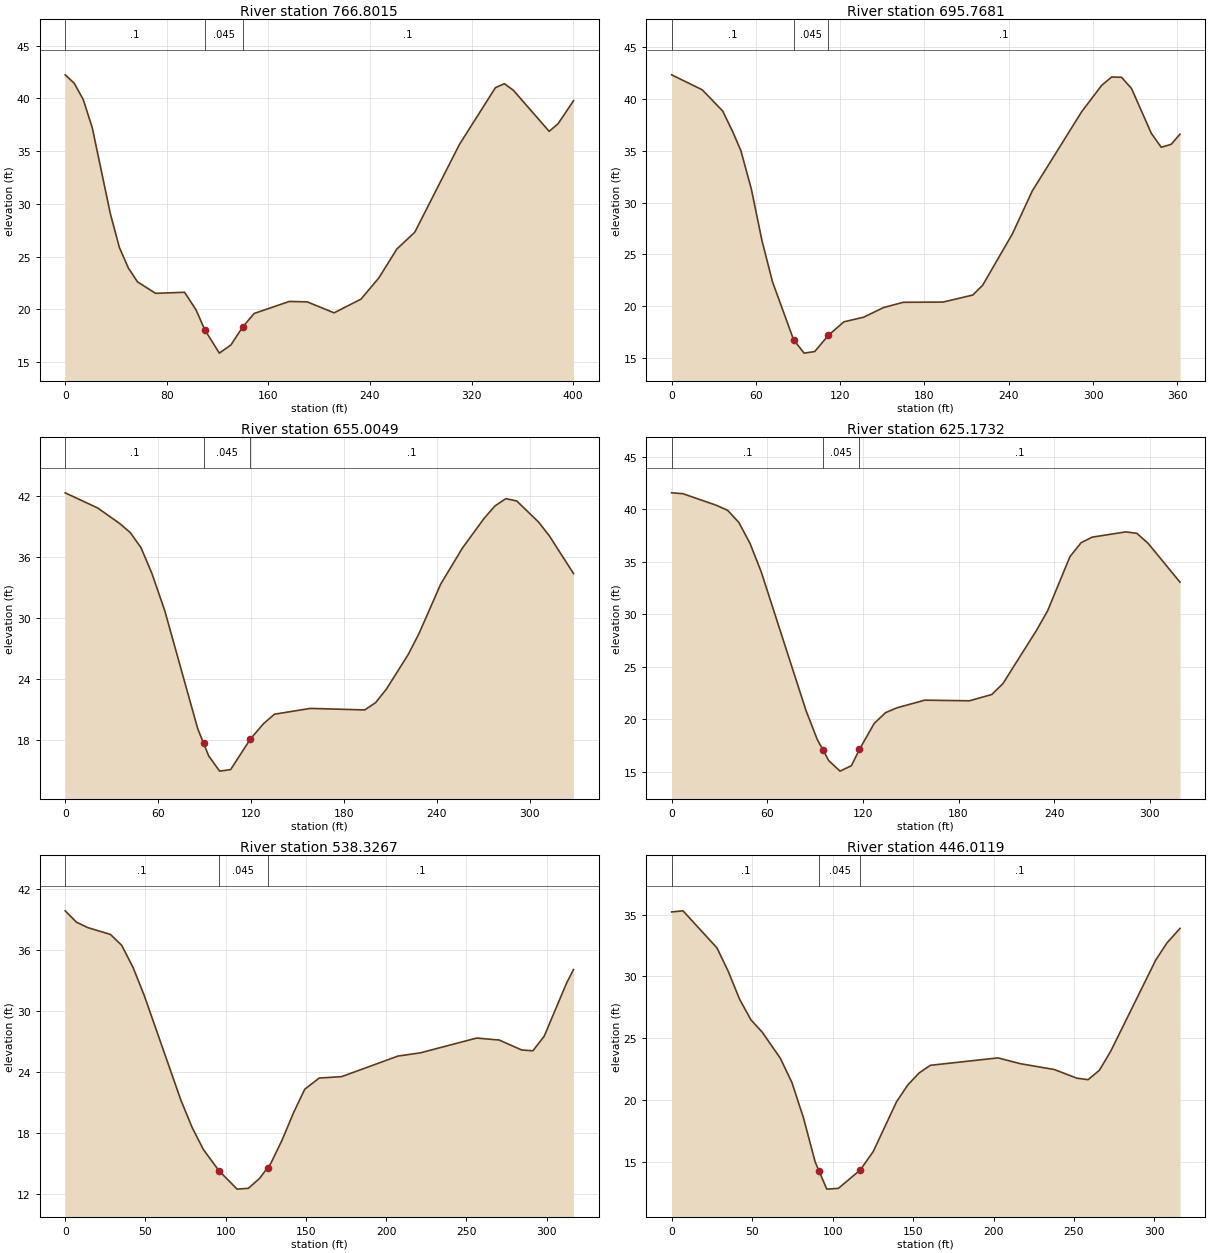
Type RM Length L Ch R = 1 ,766.8015,83.53,71.03,40.62
XS GIS Cut Line= 4
1601602.17583773703242.8355786351601617.35731567703159.337449804
1601676.18554281703089.1231142281601704.65081403702867.093998939
#Sta/Elev= 30
       0   42.24    7.11   41.44   14.23   39.89   21.34   37.21   35.57   29.06
   42.69   25.86    49.8   23.91   56.92   22.61   71.15   21.52      94   21.62
  103.13   19.93  109.97   18.05   121.4   15.85  130.53   16.63  139.66   18.31
  148.79   19.61  176.47   20.75  190.58   20.71  211.75   19.67  232.93   20.97
  247.04   22.99  261.16   25.72  275.27   27.31  310.56   35.66  338.79   41.02
  345.84    41.4   352.9   40.78  381.13   36.88  388.19   37.61  400.31   39.79
#Mann= 3 , 0 , 0
       0      .1       0  109.97    .045       0  139.66      .1       0
Bank Sta=109.97,139.66
XS Rating Curve= 0 ,0
Exp/Cntr=0.3,0.1

Type RM Length L Ch R = 1 ,695.7681,35.88,40.76,43.01
XS GIS Cut Line= 4
1601702.75312929703231.4494701771601716.03692251703184.007351518
1601689.46933602703115.690700665 1601721.7299767702878.480107397
#Sta/Elev= 30
       0   42.34   21.81   40.89   36.35   38.84   43.62    36.8   49.27   35.02
   56.78   31.28   64.29   26.33    71.8   22.35   86.82   16.75   94.33   15.46
  101.84   15.61  111.52   17.17  122.57   18.48   136.7   18.93  150.83   19.86
  164.95   20.37  193.21   20.39  214.41   21.07  221.47   22.02  242.66   26.99
  256.79   31.13  292.11   38.81  306.24   41.33  313.31   42.13  320.37    42.1
  327.44   41.02  341.57   36.68  348.63   35.34  355.69   35.63  361.96   36.61
#Mann= 3 , 0 , 0
       0      .1       0   86.82    .045       0  111.52      .1       0
Bank Sta=86.82,111.52
XS Rating Curve= 0 ,0
Exp/Cntr=0.3,0.1

Type RM Length L Ch R = 1 ,655.0049,30.82,29.83,29.68
XS GIS Cut Line= 4
1601738.38904041703225.3282865881601739.72915876703161.002604946
1601727.66809349703081.9356212321601739.72915876702898.339404851
#Sta/Elev= 30
       0   42.29      21    40.8   35.01    39.3   42.01   38.39   49.01   36.89
   56.01   34.37   64.34    30.7   85.58   19.13    89.4   17.69   92.66   16.46
   99.74   14.96  106.83   15.11   119.6   18.11  128.07   19.62  135.15   20.55
  158.35   21.12  193.43   20.97  200.44   21.68  207.46   23.02  221.49    26.4
   228.5   28.47  242.53   33.33  256.56   36.87  270.59   39.79  277.61   41.01
  284.62   41.72  291.64   41.49  305.67   39.43  312.68   38.07  328.31   34.36
#Mann= 3 , 0 , 0
       0      .1       0    89.4    .045       0   119.6      .1       0
Bank Sta=89.4,119.6
XS Rating Curve= 0 ,0
Exp/Cntr=0.3,0.1

Type RM Length L Ch R = 1 ,625.1732,85.17,86.85,89.4
XS GIS Cut Line= 4
1601765.37672587703220.0633616891601771.06978011703157.439765081
1601753.99061738703070.1462667441601761.58135641702903.150009111
#Sta/Elev= 30
       0   41.56    7.03   41.48   28.12   40.37   35.14   39.89   42.17   38.74
    49.2   36.73   56.23   34.02   84.28   20.83   91.41   18.05   94.89    17.1
   98.55   16.05  105.68   15.05  112.81   15.57  117.83   17.12  127.08   19.59
  134.21   20.62  141.34   21.08  158.84   21.81  186.87   21.75  200.88   22.35
  207.89   23.39  228.91   28.45  235.92   30.32  249.93   35.48  256.94   36.81
  263.95   37.34  284.97   37.84  291.98    37.7  298.98   36.75     319   33.05
#Mann= 3 , 0 , 0
       0      .1       0   94.89    .045       0  117.83      .1       0
Bank Sta=94.89,117.83
XS Rating Curve= 0 ,0
Exp/Cntr=0.3,0.1

Type RM Length L Ch R = 1 ,538.3267,89.48,92.32,93.77
XS GIS Cut Line= 4
1601839.38643099703197.2911447291601846.97716998703132.769863367
1601839.38643099703039.7833108161601847.21145803702881.492485911
#Sta/Elev= 30
       0   39.81    7.05   38.69    14.1   38.16   28.19   37.49   35.24   36.41
   42.29   34.24   49.34   31.45   71.99   21.24   79.01   18.54   86.04   16.36
   95.82   14.26  107.11   12.45  114.13   12.53  121.15   13.51  126.16   14.57
  128.18      15   135.2   17.29  142.22   19.94  149.25   22.27  158.26   23.37
  172.28   23.51  207.32   25.53  221.34   25.85  256.38    27.3   270.4   27.11
  284.42   26.13  291.42   26.05  298.43   27.47  312.45   32.72  316.75   34.04
#Mann= 3 , 0 , 0
       0      .1       0   95.82    .045       0  126.16      .1       0
Bank Sta=95.82,126.16
XS Rating Curve= 0 ,0
Exp/Cntr=0.3,0.1

Type RM Length L Ch R = 1 ,446.0119,114.62,111.15,108.82
XS GIS Cut Line= 4
1601931.91297854 703190.795791031601938.57489589703130.838534951
1601919.54084633703053.7506342981601913.83063146702877.685676023
#Sta/Elev= 30
       0   35.21    7.04    35.3   28.17    32.3   35.22   30.39   42.26   28.14
    49.3   26.48   56.34   25.48   67.54   23.38   74.75   21.41   81.96   18.54
   89.17      15   91.47    14.3   96.38    12.8  103.59   12.86  117.19   14.35
  125.22   15.83  139.73   19.86  146.73   21.22  153.74   22.19  160.74   22.81
  202.76   23.41  216.77   22.94  237.78   22.47  251.79   21.77  258.79   21.65
   265.8   22.41   272.8   23.94  300.81   31.32  307.82   32.71  315.89   33.88
#Mann= 3 , 0 , 0
       0      .1       0   91.47    .045       0  117.19      .1       0
Bank Sta=91.47,117.19
XS Rating Curve= 0 ,0
Exp/Cntr=0.3,0.1

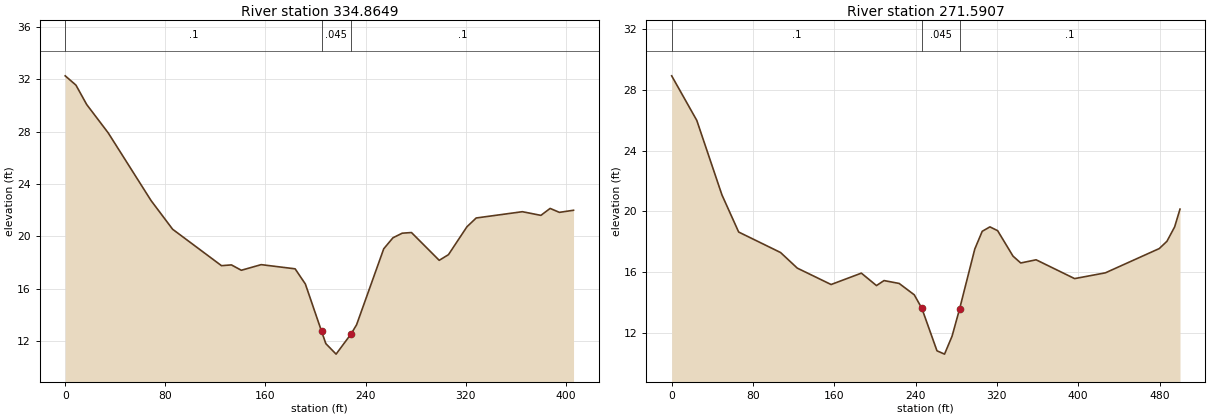
Type RM Length L Ch R = 1 ,334.8649,59.14,63.27,63.45
XS GIS Cut Line= 5
1601967.12597018703187.9406836181602068.95813526703115.611295328
 1602045.1655733703070.8812789021602004.24236679703003.310403004
1601955.70554045702859.603328943
#Sta/Elev= 30
       0   32.26    8.59   31.55   17.17   30.07   34.34   27.91   68.69   22.73
   85.86   20.55  124.91   17.77  132.83   17.83  140.76   17.42  156.62   17.85
  183.75   17.53  191.94   16.37  204.85   12.77   208.3   11.82  216.49   11.02
   228.6   12.58  232.86   13.26  254.57   19.06  261.95    19.9  269.34   20.25
  276.73    20.3   298.9   18.18  306.29   18.61  321.06   20.74  328.45   21.41
  365.39   21.89  380.17   21.61  387.56   22.14  394.95   21.84  406.25      22
#Mann= 3 , 0 , 0
       0      .1       0  204.85    .045       0   228.6      .1       0
Bank Sta=204.85,228.6
XS Rating Curve= 0 ,0
Exp/Cntr=0.3,0.1

Type RM Length L Ch R = 1 ,271.5907,251.72,271.59,287.83
XS GIS Cut Line= 4
1601983.30491231703200.3128157851602116.54325911703117.514700279
1602066.10302782702977.6144361351601991.87023456702797.742667928
#Sta/Elev= 30
       0   28.94   24.72      26   49.45   21.09   65.93   18.64  107.14   17.29
  123.62   16.26  156.87   15.18  186.63   15.93  201.52   15.11  208.96   15.44
  223.84   15.25  238.72    14.5  246.16   13.61  261.04   10.81  268.49   10.59
  275.93   11.78  283.37   13.59  298.25   17.52  305.58   18.69  313.16   18.98
  320.73   18.73  335.88   17.05  343.45    16.6  358.59   16.81  396.46   15.57
  426.75   15.95  479.76   17.55  487.33   18.03   494.9   18.98  500.17   20.15
#Mann= 3 , 0 , 0
       0      .1       0  246.16    .045       0  283.37      .1       0
Bank Sta=246.16,283.37
XS Rating Curve= 0 ,0
Exp/Cntr=0.3,0.1

Chan Stop Cuts=-1
Use User Specified Reach Order=0