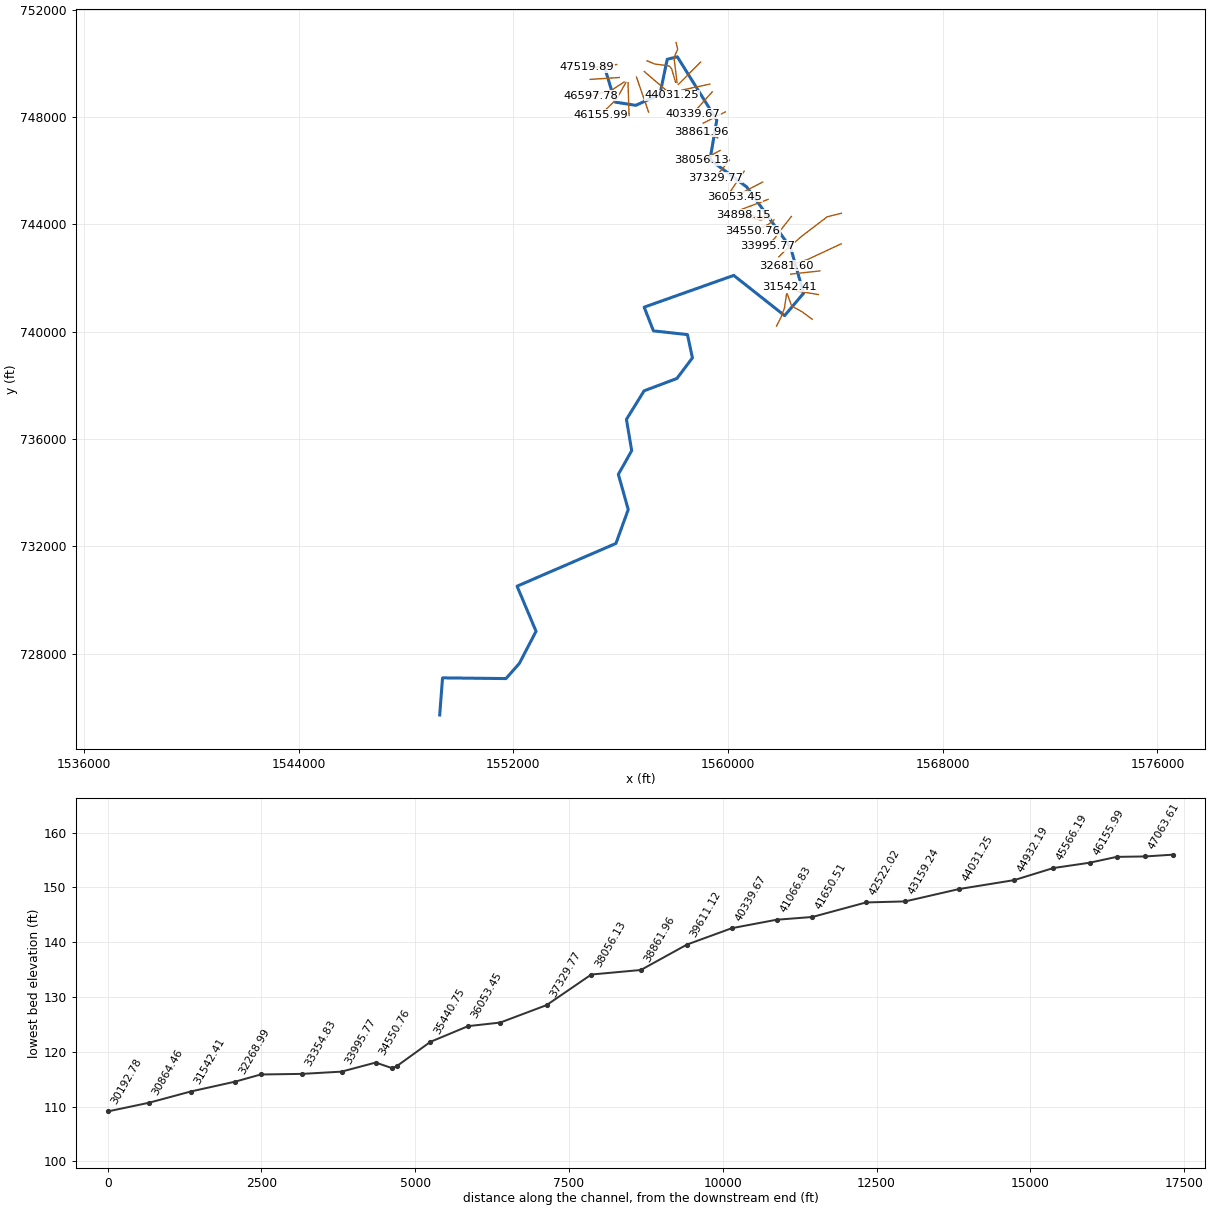
--- OctoraroCreek.prj (project) ---

Proj Title=OctoraroCreek
Current Plan=p01
Default Exp/Contr=0.3,0.1
English Units
Geom File=g01
Flow File=f01
Plan File=p01
Y Axis Title=Elevation
X Axis Title(PF)=Main Channel Distance
X Axis Title(XS)=Station
BEGIN DESCRIPTION:
Octoraro Creek - Georeferenced HEC-RAS model.  This was formerly an approximate method stream.  Projection:  MD Stateplane.  Horizontal datum:  NAD83.  Vertrial datum: NAVD88.  Units:Feet.  Created by: Aaron W. Buesing, USACE- St Paul District as part of FEMA Map Modernization study for Cecil County, MD.
END DESCRIPTION:
DSS Export Rating Curves= 0
DSS Export Rating Curve Sorted= 0
DSS Export Volume Flow Curves= 0
DXF OffsetX= 0
DXF OffsetY= 0
DXF ScaleX= 1
DXF ScaleY= 10

--- OctoraroCreek.p01 (plan) ---

Plan Title=OctoraroCreek_100yr
Program Version=4.00
Short Identifier=Octoraro100
Geom File=g01
Flow File=f01
Subcritical Flow
K Sum by GR= 0
Std Step Tol= 0.01
Critical Tol= 0.01
Num of Std Step Trials= 20
Max Error Tol= 0.3
Flow Tol Ratio= 0.001
Split Flow NTrial= 30
Split Flow Tol= 0.02
Split Flow Ratio= 0.02
Log Output Level= 0
Friction Slope Method= 1
Unsteady Friction Slope Method= 2
Unsteady Bridges Friction Slope Method= 1
Secant Critical Depth
Global Vel Dist= 0 , 0 , 0
Global Log Level= 0
CheckData=True
Encroach Param=-1 ,0,0, 0
Computation Interval=1HOUR
Output Interval=1HOUR
Run HTab= 0
Run UNet= 0
Run PostProcess= 0
Run WQNet= 0
UNET Theta= 1
UNET Theta Warmup= 1
UNET ZTol= 0.02
UNET ZSATol= 0.05
UNET MxIter= 20
UNET MaxInSteps= 0
UNET DtIC= 0
UNET DtMin= 0
UNET MaxCRTS= 20
UNET WFStab= 2
UNET SFStab= 1
UNET WFX= 1
UNET SFX= 1
UNET DSS MLevel= 4
UNET DZMax Abort= 100
UNET Convert EG Bridges= 0
UNET Use Existing IB Tables=-1
UNET Froude Reduction=False
UNET Froude Limit= 1
UNET Froude Power= 10
UNET Time Slicing=0,0, 5
Instantaneous Interval=1HOUR
Write IC File= 0
Echo Input=False
Echo Output=False
Write Detailed= 0
Detailed Automatic Start=False, 10
WQ ULTIMATE=-1
WQ Max Comp Step=1HOUR
WQ Output Interval=15MIN
WQ Output Selected Increments= 0
WQ Output face flow=0
WQ Output face velocity=0
WQ Output face area=0
WQ Output face dispersion=0
WQ Output cell volume=0
WQ Output cell surface area=0
WQ Output cell continuity=0
WQ Output face conc=0
WQ Output face dconc_dx=0
WQ Output face courant=0
WQ Output face peclet=0
WQ Output face adv mass=0
WQ Output face disp mass=0
WQ Output cell mass=0
WQ Output cell source sink temp=0
WQ Output cell source sink nsm=0
WQ Output MaxMinRange=-1
WQ Create Restart=0
WQ Fixed Restart=0
Sorting and Armoring Iterations= 10
XS Update Threshold= 0.02
Hydraulics Update Threshold= 0.02
Energy Slope Method= 1
Volume Change Method= 0
XS Weighting Method= 0
Number of US Weighted Cross Sections= 1
Number of DS Weighted Cross Sections= 1
Upstream XS Weight=0.25
Main XS Weight=0.5
Downstream XS Weight=0.25
Number of DS XS's Weighted with US Boundary= 1
Upstream Boundary Weight= 1
Weight of XSs Associated with US Boundary= 0
Number of US XS's Weighted with DS Boundary= 1
Downstream Boundary Weight= 0.5
Weight of XSs Associated with DS Boundary= 0.5
Sediment Output Level= 4
Mass or Volume Output= 0
Output Increment Type= 1
Profile and TS Output Increment= 10
XS Output Flag= 0
XS Output Increment= 10
Disregard all LS=0
Disregard all Conn=0
Disregard all Breaches=0
Disregard all Pumps=0

--- OctoraroCreek.f01 (steady flow) ---

Flow Title=OctoraroCreek_100yr
Program Version=4.00
Number of Profiles= 2
Profile Names=100CUR,100ULT
River Rch & RM=OctoraroCreek,Reach1          ,47519.89
   34300   34300
River Rch & RM=OctoraroCreek,Reach1          ,46155.99
   34400   34400
River Rch & RM=OctoraroCreek,Reach1          ,32268.99
   35500   35700
River Rch & RM=OctoraroCreek,Reach1          ,19254.74
   35800   36100
River Rch & RM=OctoraroCreek,Reach1          ,15209.53
   36200   36500
River Rch & RM=OctoraroCreek,Reach1          ,12551.48
   36300   36600
River Rch & RM=OctoraroCreek,Reach1          ,4845.989
   37300   37800
Boundary for River Rch & Prof#=OctoraroCreek,Reach1          , 1
Up Type= 0
Dn Type= 3
Dn Slope=0.0009
Boundary for River Rch & Prof#=OctoraroCreek,Reach1          , 2
Up Type= 0
Dn Type= 3
Dn Slope=0.0009
DSS Import GetInterval= 0
DSS Import GetPeak= 0
DSS Import FillOption= 0

--- OctoraroCreek.g01 (geometry) ---

Geom Title=OctoraroCreek
Program Version=4.00

River Reach=OctoraroCreek   ,Reach1
Reach XY= 30
 1555382.4434244749919.9854889511555795.31362419748553.104536206
 1556564.9357442    748432.851081557462.82821751748837.704382703
1557735.40271853750148.4670557681558112.19688122750240.661372319
1559582.49580625747882.0902504771559328.76266178 746409.20968695
1560696.84450094745392.0420163271562334.69657493743125.665210962
1562816.38134022741434.0839742121562110.22345661740597.937560573
1560214.22729652742097.0973151621556875.88513105740912.811478838
 1557224.0803147740029.9323680251558489.79273395739890.446393028
 1558674.1813668739024.6215081661558096.96477686738257.003612399
1556874.38797155737796.0320301061556216.28893466736732.115040869
1556411.81300989735566.1321063341555914.85133481734685.038800955
1556283.54265678733372.7090643791555824.86711024732110.721894041
 1552141.2119339730517.4911682611552848.73604351728838.499078467
1552225.38935307727638.6234256481551727.54004455727075.837250412
1549364.97374807727102.0895167591549258.92916016725720.644497618

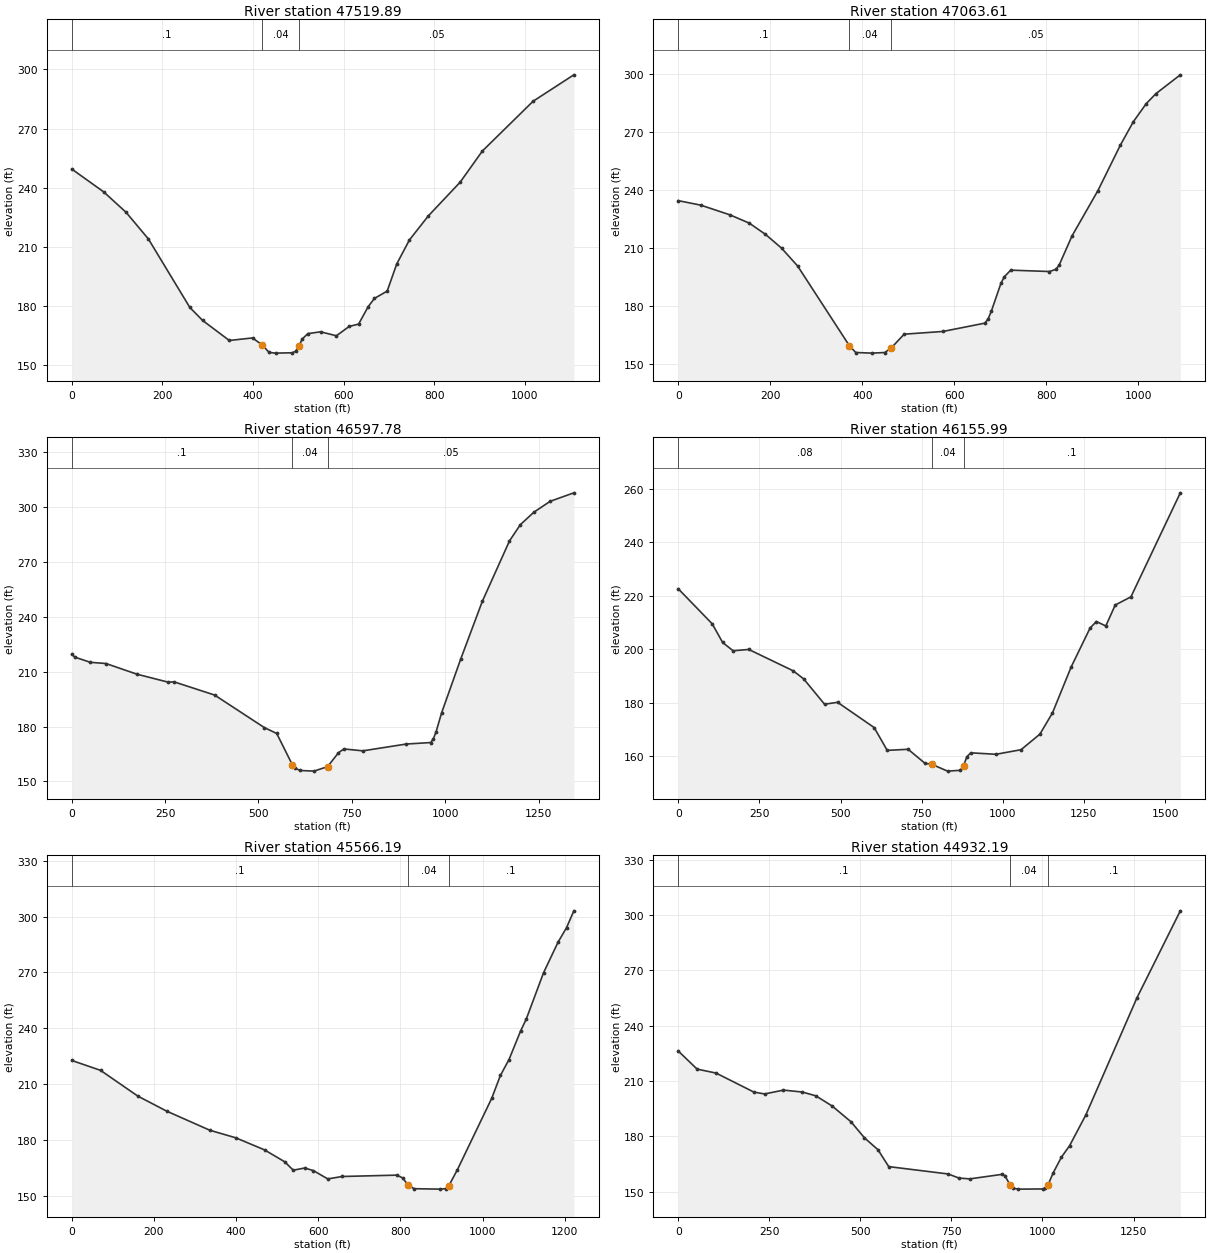
Type RM Length L Ch R = 1 ,47519.89,475.42,456.28,438.59
XS GIS Cut Line= 4
1555853.18436798749953.2507718951555522.19277491  749916.1302194
1555348.96352997749863.5427700131554755.03469001 749851.16925253
#Sta/Elev= 30
       0  249.44   70.44  237.85  119.75   227.5  169.05  213.97  260.62  179.17
   288.8  172.58   347.7  162.41  398.91   163.7  420.85  160.07  435.48  156.34
  450.11  155.99  486.69  156.17  494.01  156.95  501.32  159.65  508.64  163.15
   521.1  165.89  549.11  166.81  584.12   164.8  612.12  169.52  633.13  170.74
  654.13  179.55  668.14  183.79  696.14  187.47  717.15  201.21  745.15  213.42
  787.16   225.7  857.18  242.76  906.19  258.57 1018.21  283.86 1108.16  297.27
#Mann= 3 , 0 , 0
       0      .1       0  420.85     .04       0  501.32     .05       0
Bank Sta=420.85,501.32
XS Rating Curve= 0 ,0
Exp/Cntr=0.3,0.1

Type RM Length L Ch R = 1 ,47063.61,452.34,465.83,499.58
XS GIS Cut Line= 2
  1555952.172508749470.6835894441554863.30296816749399.535863817
#Sta/Elev= 30
       0  234.47    49.1  232.14  112.24  227.14  154.33  222.86   189.4  217.08
  224.48  209.95  259.55  200.67  371.79  159.55  385.82  155.98   420.9  155.66
  448.96  155.98  462.99  158.35  491.04  165.46  575.22  166.86  666.42  171.16
  673.43  173.31  680.45  177.31  701.49  191.83  708.51  195.07  722.54  198.55
  806.72  197.84  820.75  198.96  827.76  201.12  855.82  216.23  911.94  239.58
  961.05  263.23  989.11  275.27 1017.17  284.62 1038.21  289.78 1091.19   299.5
#Mann= 3 , 0 , 0
       0      .1       0  371.79     .04       0  462.99     .05       0
Bank Sta=371.79,462.99
XS Rating Curve= 0 ,0
Exp/Cntr=0.3,0.1

Type RM Length L Ch R = 1 ,46597.78,387.8,441.79,518.11
XS GIS Cut Line= 3
1556134.03809454749302.7359292511555667.58160551749003.583303884
1554906.61027938748790.140127018
#Sta/Elev= 30
       0  219.57    8.32  217.95    49.9  215.13   91.47  214.48  174.63  208.63
  257.79  204.29  274.42  204.41  382.53  197.22  515.58  179.42  548.85  176.19
  590.49  159.13  597.76  157.16   612.3  155.93  648.65  155.58  685.01  158.04
  714.09  165.61  728.63  167.72  779.52  166.68  895.84  170.41  961.27  171.22
  968.54   173.4  975.81  177.25  990.35  187.47 1041.24  216.75  1099.4  248.51
  1172.1  281.57 1201.19  290.46 1237.54  297.32 1281.16  303.26 1344.48   307.9
#Mann= 3 , 0 , 0
       0      .1       0  590.49     .04       0  685.01     .05       0
Bank Sta=590.49,685.01
XS Rating Curve= 0 ,0
Exp/Cntr=0.3,0.1

Type RM Length L Ch R = 1 ,46155.99,464.81,589.8,665.18
XS GIS Cut Line= 4
1556198.46009851749289.6182573291555837.71747114748654.031434536
1555717.07567552 748533.389638961555249.97538996748087.943009004
#Sta/Elev= 30
       0  222.62  104.64  209.54  136.83  202.56  169.03  199.46  217.32  199.96
  354.15  191.98  386.35  188.98  450.74  179.51  490.98  180.21  603.67  170.78
  643.91  162.26   708.3  162.67  760.52   157.4  780.32  157.11  829.82  154.51
  869.42  154.82  879.32  156.61  889.22  159.88  901.44  161.35  978.82   160.8
  1056.2  162.51 1114.24  168.32 1152.93  176.24 1210.97  193.52    1269  207.99
 1288.35  210.38 1317.37  208.73 1346.38  216.56 1394.75  219.61 1546.89  258.46
#Mann= 3 , 0 , 0
       0     .08       0  780.32     .04       0  879.32      .1       0
Bank Sta=780.32,879.32
XS Rating Curve= 0 ,0
Exp/Cntr=0.3,0.1

Type RM Length L Ch R = 1 ,45566.19,583.06,634,654.56
XS GIS Cut Line= 2
1556274.79001409749275.6682524381556314.09789483748053.915835872
#Sta/Elev= 30
       0  222.69   70.04  217.37  161.08   203.5  231.12  195.45  336.17  185.18
  399.21  181.13  469.24  174.64  518.27  168.26  539.28  163.71  567.29   164.9
   588.3  163.48  623.32  159.03  658.34  160.33  791.41  161.06  805.42  159.57
  819.42  155.64  833.43  153.77  896.46  153.54  910.47  153.82  917.47  155.13
  938.48  163.81 1022.53   202.4 1043.54  214.62 1064.55  223.18 1092.56  238.43
 1106.57  244.95 1148.59   269.8 1183.61  286.12 1204.62  294.06 1222.38   303.1
#Mann= 3 , 0 , 0
       0      .1       0  819.42     .04       0  917.47      .1       0
Bank Sta=819.42,917.47
XS Rating Curve= 0 ,0
Exp/Cntr=0.3,0.1

Type RM Length L Ch R = 1 ,44932.19,788.24,900.94,926.8
XS GIS Cut Line= 2
1556589.40865913749486.1504863051557041.04204784748183.837769598
#Sta/Elev= 30
       0  226.27   51.86  216.43  103.73   214.3  207.45     204  237.09  202.96
  288.95  205.05  340.81     204  377.86  201.94  422.31  196.46  474.18  187.89
  511.22  179.17  548.27  172.72   577.9  163.55   740.9  159.57  770.54  157.36
  800.17  156.89  889.08  159.36  896.49  158.71  911.31  153.53  918.72  151.86
  933.53  151.34 1000.21  151.43 1007.62  151.76 1015.19  153.67 1029.85  160.35
 1052.08  168.69  1074.3  174.85 1118.76  191.47 1259.53  255.19  1378.4  302.29
#Mann= 3 , 0 , 0
       0      .1       0  911.31     .04       0 1015.19      .1       0
Bank Sta=911.31,1015.19
XS Rating Curve= 0 ,0
Exp/Cntr=0.3,0.1

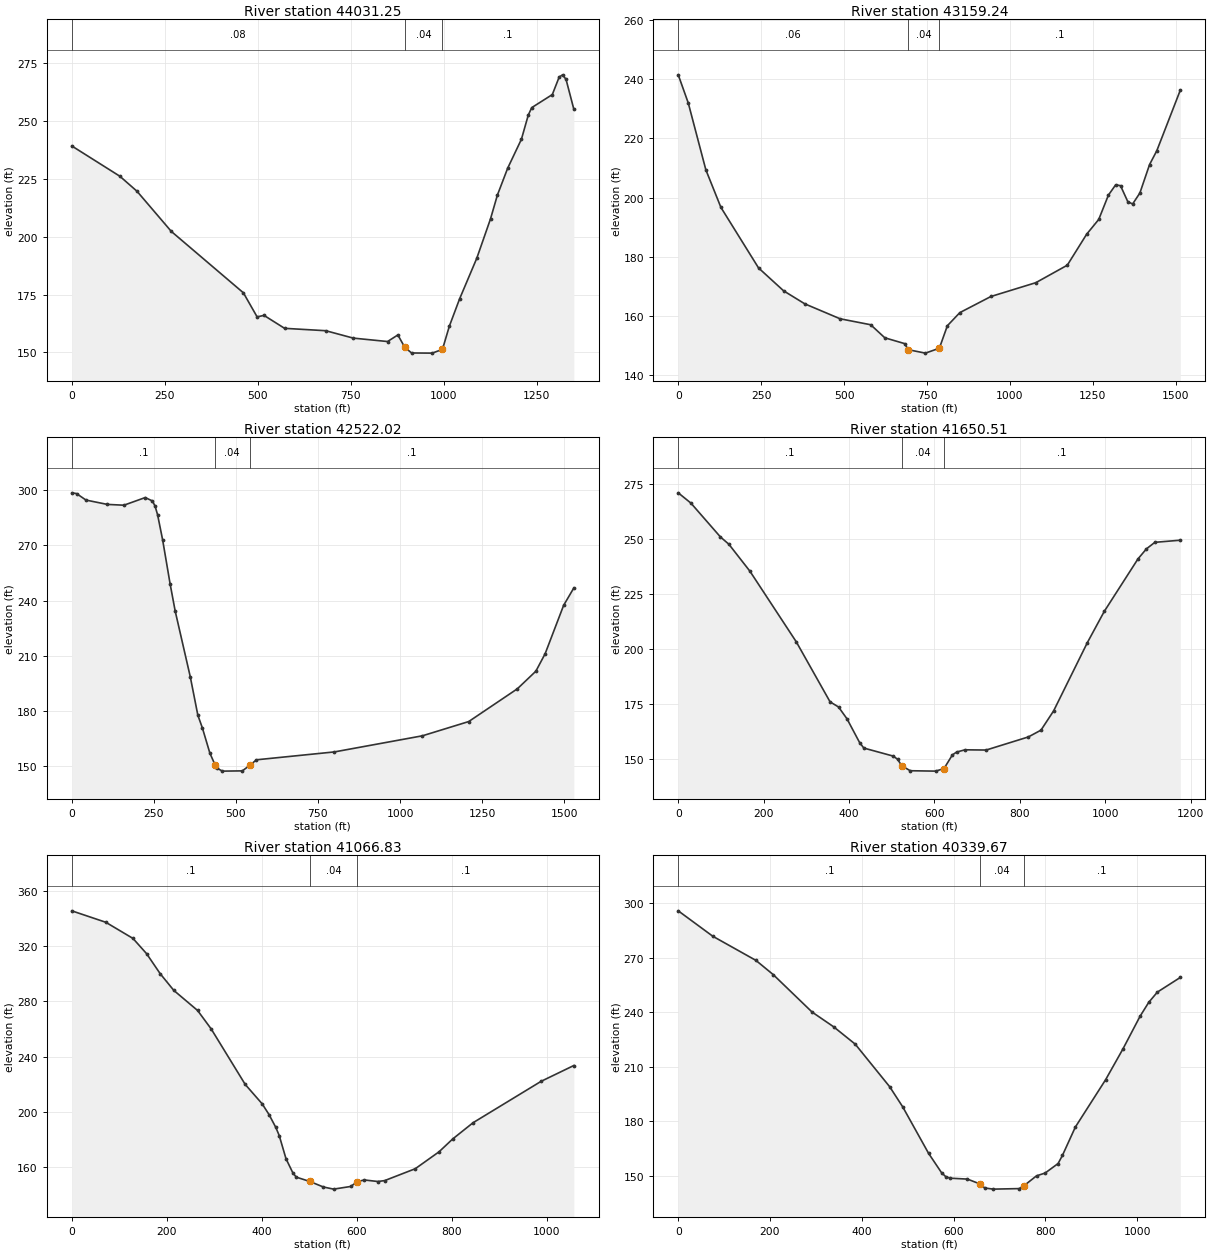
Type RM Length L Ch R = 1 ,44031.25,753.01,872.01,903.96
XS GIS Cut Line= 2
1556880.18632035749693.4069044141557904.09489334748814.887162015
#Sta/Elev= 30
       0  239.19  129.13  226.11  175.25  219.62  267.48  202.27  461.17  175.75
  498.07  165.35  516.51  166.01  571.86  160.41  682.54  159.38  756.32  156.19
  848.56  154.71  876.23  157.55  894.68  152.25  913.12  149.76  968.46   149.7
  996.13  151.32 1014.58  161.33 1042.25  173.18 1088.37   190.7 1125.26  207.71
 1143.71  217.96 1171.38  229.59 1208.27  242.08 1226.72  252.52 1235.95  255.73
 1291.29  261.37 1309.73  268.95 1318.96   269.9 1328.18  267.93 1349.14  255.03
#Mann= 3 , 0 , 0
       0     .08       0  894.68     .04       0  996.13      .1       0
Bank Sta=894.68,996.13
XS Rating Curve= 0 ,0
Exp/Cntr=0.3,0.1

Type RM Length L Ch R = 1 ,43159.24,840.52,637.22,274.1
XS GIS Cut Line= 6
1556982.26783971750092.4528437261557276.13888033 749971.81104812
1557764.89282151 749906.850081251557829.85378836749882.103046268
1557901.00151399749789.3016650381558046.39034459749294.360965088
#Sta/Elev= 30
       0  241.51   30.27  231.98   83.24  209.41  128.64  196.71  242.14  176.24
  317.67  168.51  381.54  164.11  487.99  159.06  580.24  157.04  622.82  152.63
  682.19  150.68  693.74   148.6  745.25  147.45   787.3  149.11  811.43  156.71
  848.88  161.13  942.69  166.59 1078.13  171.26 1172.98  177.17 1231.35  187.64
 1267.82  192.64 1297.01  200.86 1318.89  204.34 1333.49  204.04 1355.37  198.65
 1369.96  197.85 1391.85  201.57 1421.04  211.18 1442.92  215.87 1513.73  236.33
#Mann= 3 , 0 , 0
       0     .06       0  693.74     .04       0   787.3      .1       0
Bank Sta=693.74,787.3
XS Rating Curve= 0 ,0
Exp/Cntr=0.3,0.1

Type RM Length L Ch R = 1 ,42522.02,892.21,871.52,673.03
XS GIS Cut Line= 6
1558064.31688464750772.5959312171558126.76393449750526.592401534
1558071.13737956  750401.79078121558012.36317147 750262.58870934
1557996.89627458750138.8535343711558102.07117336749281.987447605
#Sta/Elev= 30
       0   298.6   14.44   298.2   43.33  294.66  108.33   292.3  158.88  291.87
  223.88  296.03  245.55  294.18  253.81  291.36  261.47  286.66   276.8  273.02
  299.79  248.89  315.12  234.25   361.1  198.51  384.09  177.67  398.04  170.67
  420.84  156.99  436.03  150.86  443.63  148.75  458.83  147.26  519.62   147.4
  541.76  150.35  562.71  153.42  800.24  157.71 1068.24  166.47 1209.29  174.22
 1357.39  192.02 1413.81   201.6 1442.02  211.08 1498.44  237.42 1529.54  246.89
#Mann= 3 , 0 , 0
       0      .1       0  436.03     .04       0  541.76      .1       0
Bank Sta=436.03,541.76
XS Rating Curve= 0 ,0
Exp/Cntr=0.3,0.1

Type RM Length L Ch R = 1 ,41650.51,648.83,583.68,493.9
XS GIS Cut Line= 2
1558981.09517701750044.0895968971558151.56524332749210.839721978
#Sta/Elev= 30
       0  270.81   29.63  266.16   98.77  250.81  118.53  247.51  167.92  235.26
  276.57   203.2  355.59  176.02  375.34  173.71   395.1  168.36  424.73  157.57
  434.61  155.07  503.75  151.41  513.63  149.98   523.5  147.03  543.26  144.79
  602.52  144.61  622.28  145.74  642.03  151.97  651.91  153.26  671.66  154.28
  721.05  154.17  819.83  160.11  849.46  163.19  879.09  171.93  958.11  202.89
  997.62  217.02 1076.64  240.85 1096.39   245.4 1116.15  248.36 1175.77  249.33
#Mann= 3 , 0 , 0
       0      .1       0   523.5     .04       0  622.28      .1       0
Bank Sta=523.5,622.28
XS Rating Curve= 0 ,0
Exp/Cntr=0.3,0.1

Type RM Length L Ch R = 1 ,41066.83,666.02,727.16,788.01
XS GIS Cut Line= 2
1559321.09289032749223.4054612371558287.67393585749003.583303884
#Sta/Elev= 30
       0  345.59   71.57  337.31  128.82   325.6  157.45  314.57  186.07  300.07
   214.7  287.99  264.79  273.44  293.42  260.06  364.99   219.9  400.77  205.81
  415.08  198.09   429.4  188.76  436.55  182.89  450.87  166.06  465.18  155.93
  472.34  152.79  500.96  149.64  529.59  145.63  551.06   144.1  586.84  146.02
  601.16  149.53  615.47  150.74   644.1  149.62  658.41  150.27  722.82  158.87
  772.91  171.13  801.54   180.4  844.48  192.18  987.61  222.14 1056.54   233.6
#Mann= 3 , 0 , 0
       0      .1       0  500.96     .04       0  601.16      .1       0
Bank Sta=500.96,601.16
XS Rating Curve= 0 ,0
Exp/Cntr=0.3,0.1

Type RM Length L Ch R = 1 ,40339.67,761.99,728.55,687.44
XS GIS Cut Line= 2
1559414.88536297748936.1660137621558683.62649578748121.970182106
#Sta/Elev= 30
       0  295.93   75.27  281.93  169.36  268.61  206.99  260.79  291.67  240.16
  338.72  232.02  385.76  222.46  461.03  198.94  489.26  187.91  545.71  162.27
  573.94  151.61  583.35  149.37  592.76  148.59  630.39  148.09  658.62  145.31
  668.03  143.18  686.84  142.56   743.3  142.85  752.71  144.26  780.93  149.88
  799.75  151.43  827.98  156.67  837.38  161.11  865.61  176.77  931.47  202.82
  969.11  219.72 1006.74  237.87 1025.56  245.49 1044.38  251.14 1094.37  259.22
#Mann= 3 , 0 , 0
       0      .1       0  658.62     .04       0  752.71      .1       0
Bank Sta=658.62,752.71
XS Rating Curve= 0 ,0
Exp/Cntr=0.3,0.1

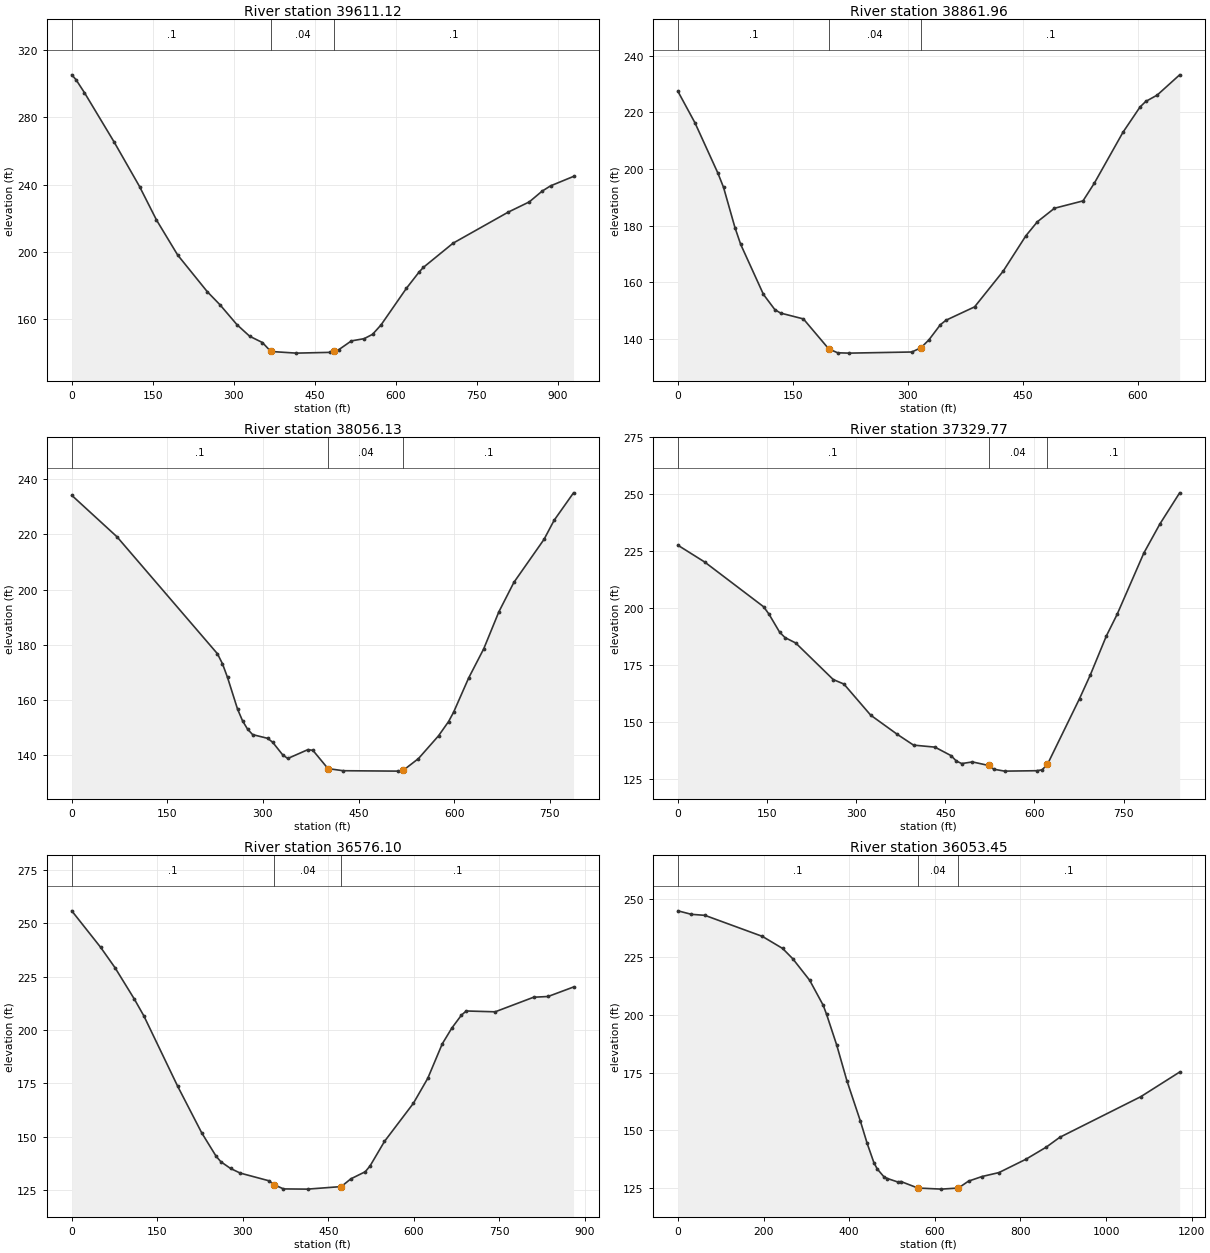
Type RM Length L Ch R = 1 ,39611.12,812.73,749.16,649.02
XS GIS Cut Line= 2
1559902.41796938748186.931148976  1559073.392297747766.231554046
#Sta/Elev= 30
       0  305.42    7.85  302.55   23.55  294.78    78.5  265.39   125.6  238.86
  156.99  218.92  196.24  198.03  251.19  176.15  274.74  168.35  306.14  156.51
  329.69  149.62  353.24  145.88  368.94  140.55  416.04  139.57  478.83  140.03
  486.68  140.76  494.53  141.58  518.08  146.86  541.63  148.18  557.33  150.78
  573.03  156.38  620.13  178.24  643.68  187.95  651.53  190.68  706.48  205.09
  808.52  223.57  847.77  229.71  871.32  236.07  887.02  239.24  929.66  244.88
#Mann= 3 , 0 , 0
       0      .1       0  368.94     .04       0  486.68      .1       0
Bank Sta=368.94,486.68
XS Rating Curve= 0 ,0
Exp/Cntr=0.3,0.1

Type RM Length L Ch R = 1 ,38861.96,728.68,805.83,871.33
XS GIS Cut Line= 2
1559614.73368753747221.7967841181558999.15119195747444.520099089
#Sta/Elev= 30
       0  227.48   22.33  216.31   52.11  198.61   59.55  193.53   74.44  179.33
   81.88   173.4  111.66  155.67  126.55  150.29  133.99  149.09  163.77  147.02
  196.85  136.42  208.43  135.05  223.32  134.93  305.21  135.33  317.11  136.83
  327.54  139.63  342.43  144.97  349.87  146.57  387.09  151.28  424.31  163.87
  454.09  176.44  468.98  181.36  491.31  186.14  528.53  188.74  543.42  195.05
  580.64  212.98  602.97  221.94  610.42   223.9   625.3  226.13  654.64   233.3
#Mann= 3 , 0 , 0
       0      .1       0  196.85     .04       0  317.11      .1       0
Bank Sta=196.85,317.11
XS Rating Curve= 0 ,0
Exp/Cntr=0.3,0.1

Type RM Length L Ch R = 1 ,38056.13,678.56,726.36,752.13
XS GIS Cut Line= 2
1559704.44168942746748.5097397861559005.33795072 746386.58435297
#Sta/Elev= 30
       0  234.22   70.94  219.17  228.59   176.7  236.47  173.07  244.36  168.12
  260.12  156.61     268  152.34  275.88  149.33  283.77  147.36  307.41     146
   315.3  144.56  331.06  139.97  338.94  138.69  370.47   141.9  378.36  141.64
     402  135.02  425.65  134.25  512.36   134.1  520.24  134.43  543.89  138.64
  575.42  146.92  591.18  152.09  599.06  155.48  622.71  167.92  646.36  178.51
  670.01  191.89  693.65  202.61  740.95  218.23  756.71  225.12  787.23  235.12
#Mann= 3 , 0 , 0
       0      .1       0     402     .04       0  520.24      .1       0
Bank Sta=402,520.24
XS Rating Curve= 0 ,0
Exp/Cntr=0.3,0.1

Type RM Length L Ch R = 1 ,37329.77,739.92,753.66,753.99
XS GIS Cut Line= 2
1560050.90017934746389.6777323481559518.83892693 745733.88130492
#Sta/Elev= 30
       0  227.69   45.07  220.32  144.23  200.69  153.24  197.46  171.27   189.5
  180.28  187.15  198.31  184.77  261.41  168.73  279.44  166.74  324.51  153.08
  369.58  144.61  396.62  139.94  432.68  139.05  459.72  135.33  468.73  132.92
  477.75  131.85  495.78  132.56  522.82  131.01  531.83  129.35  549.86  128.52
  603.94   128.7  612.96  129.09  621.97   131.5  676.06   160.4  694.09  170.73
  721.13  187.86  739.16   197.3  784.23  224.27  811.27  237.04  844.49  250.69
#Mann= 3 , 0 , 0
       0      .1       0  522.82     .04       0  621.97      .1       0
Bank Sta=522.82,621.97
XS Rating Curve= 0 ,0
Exp/Cntr=0.3,0.1

Type RM Length L Ch R = 1 ,36576.10,571.45,522.66,467.49
XS GIS Cut Line= 2
1560601.52170801745981.3516549021560109.67438747745251.314122498
#Sta/Elev= 30
       0  255.79   50.64  238.69   75.96   229.1  109.73  214.45  126.61  206.48
  185.69  173.62  227.89  151.76  253.21  140.76  261.65  138.15  278.54  135.03
  295.42  132.86  346.06  129.23   354.5  127.48  371.38  125.43  413.58  125.33
  472.79  126.52  489.55  130.14  514.87  133.48  523.31   136.2  548.63   147.7
  599.27  165.55  624.59  177.29  649.92   193.4   666.8  200.85  683.68  206.92
  692.12  208.84  742.76  208.45  810.29  215.29  835.61  215.63  880.27  220.08
#Mann= 3 , 0 , 0
       0      .1       0   354.5     .04       0  472.79      .1       0
Bank Sta=354.5,472.79
XS Rating Curve= 0 ,0
Exp/Cntr=0.3,0.1

Type RM Length L Ch R = 1 ,36053.45,625.05,612.7,592.19
XS GIS Cut Line= 2
1561294.43868792745576.1189568041560255.06321807745034.777566269
#Sta/Elev= 30
       0  244.79   31.57  243.28   63.14  242.84  197.31  233.76  244.67  228.54
  268.35   224.1  307.81  214.81  339.38  204.03  347.27  200.11  370.95  186.85
  394.63  171.53   426.2  154.06  441.98  144.46  457.77  136.12  465.66  133.36
  481.44  129.96  489.34  129.26  513.02   127.8  520.91  127.97  560.37  125.16
  615.62  124.68  655.08  125.16  678.76  128.13  710.33  130.12  749.79  131.82
  812.93  137.59  860.29   142.8  891.86  147.04 1081.28   164.6  1171.9  175.21
#Mann= 3 , 0 , 0
       0      .1       0  560.37     .04       0  655.08      .1       0
Bank Sta=560.37,655.08
XS Rating Curve= 0 ,0
Exp/Cntr=0.3,0.1

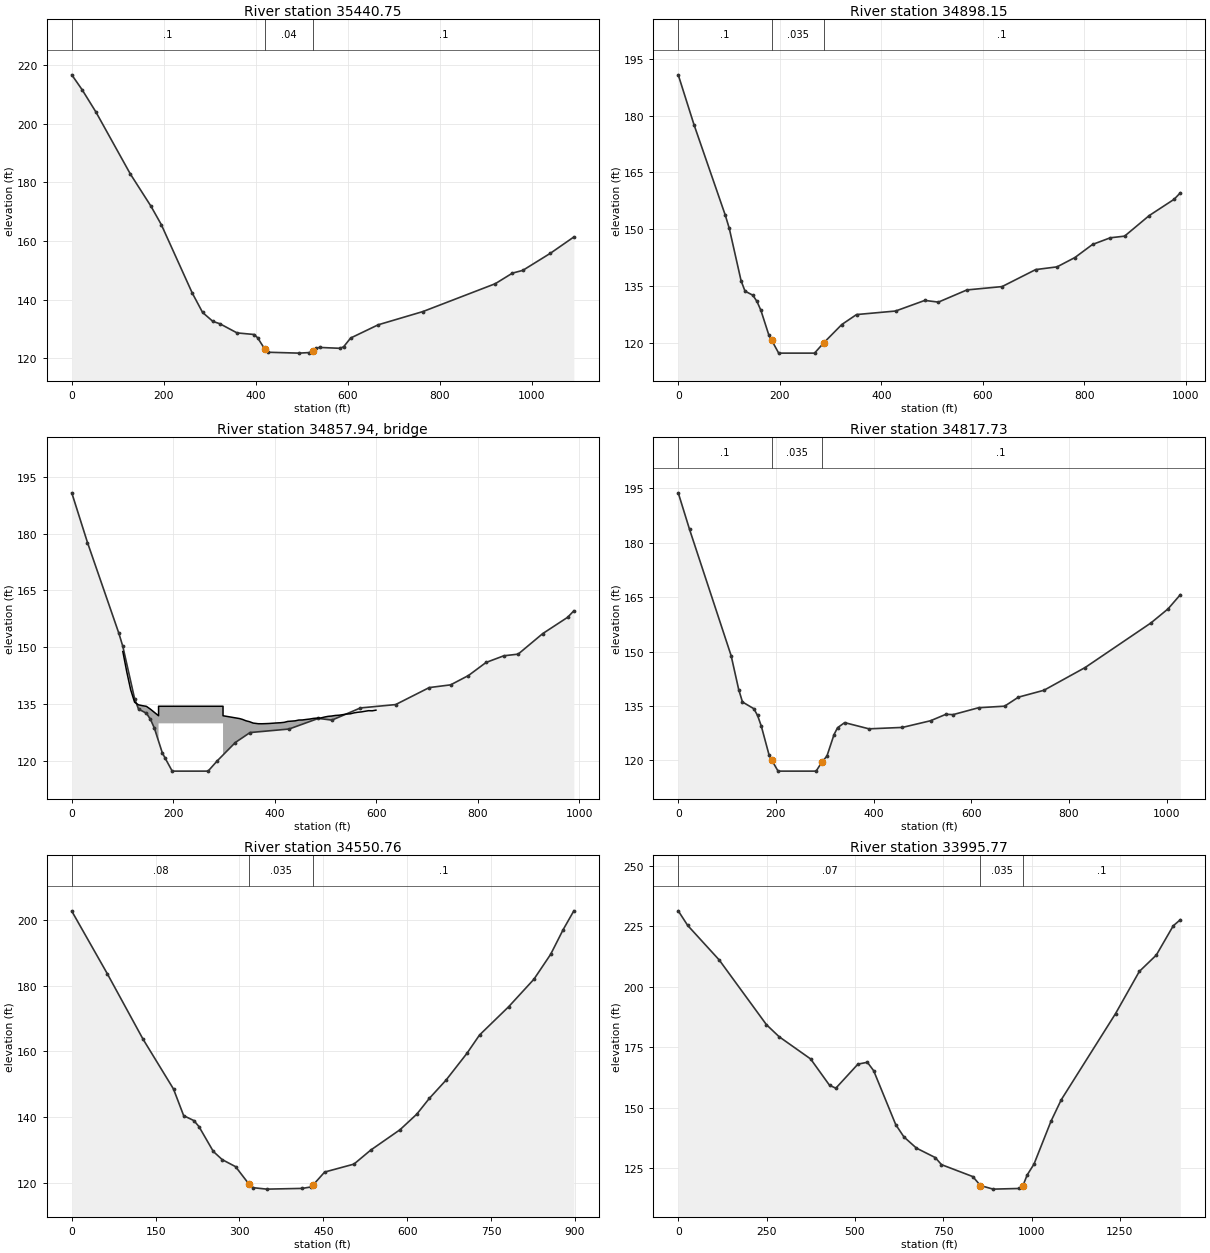
Type RM Length L Ch R = 1 ,35440.75,535.47,542.6,454.91
XS GIS Cut Line= 2
1561492.41496789 744929.60266754 1560471.5997743744542.930245712
#Sta/Elev= 30
       0  216.72   22.46  211.65    52.4  204.07  127.25  182.93  172.16  171.92
  194.62  165.65  261.99  142.29  284.44  135.68   306.9  132.62  321.87  131.84
   359.3  128.71  396.72  128.16  404.21  127.01  419.18   123.3  426.67  122.11
  494.03  121.81  516.49     122  523.97  122.57  531.46  123.55  538.95  123.75
  583.86  123.45  591.34  124.03  606.31  126.96   666.2  131.47  763.51  135.99
   920.7  145.48  958.13   149.1  980.58  150.03 1040.46  155.85 1091.59  161.42
#Mann= 3 , 0 , 0
       0      .1       0  419.18     .04       0  523.97      .1       0
Bank Sta=419.18,523.97
XS Rating Curve= 0 ,0
Exp/Cntr=0.5,0.3

Type RM Length L Ch R = 1 ,34898.15,80.52,80.41,99.62
BEGIN DESCRIPTION:
Under water portion adjusted -2' as indicated by flow depth in bridge inspection report.
END DESCRIPTION:
XS GIS Cut Line= 6
1561509.85545664744378.8117450481561240.63929629744250.881082013
1561217.32875887744244.3541315651561052.89367679744278.748792619
1560906.08952512744325.2812607441560562.80118044 744354.29809697
#Sta/Elev= 30
       0  190.73   30.95  177.64   92.86  153.69  100.59  150.26  123.81  136.48
  131.55  133.75  147.02  132.66  155.01  131.05  162.77  128.72   178.3  122.26
  184.28  120.75   197.9  117.41  268.54  117.41  286.99  120.17  322.28  124.95
  351.25  127.57  428.17   128.5  485.81   131.3  512.58  130.85  568.77  134.06
  638.01  134.94  704.25  139.42  746.42  140.14  781.57   142.6  816.21  146.04
   851.3   147.8  879.38  148.23  927.91  153.65  976.96  157.94  989.17  159.64
#Mann= 3 , 0 , 0
       0      .1       0  184.28    .035       0  286.99      .1       0
Bank Sta=184.28,286.99
XS Rating Curve= 0 ,0
Exp/Cntr=0.5,0.3

Type RM Length L Ch R = 3 ,34857.94,,,
BEGIN DESCRIPTION:
New Bridge Road - CE042407PF-1
Top of road obtained from DEM.
Opening from MDE2 bridge/culvert surveys.
END DESCRIPTION:
Bridge Culvert--1,0,-1,-1, 0
Deck Dist Width WeirC Skew NumUp NumDn MinLoCord MaxHiCord MaxSubmerge Is_Ogee
30,20,2.6,0, 50, 50, , , 0.95, 0, 2,2,,
  100.59  108.33  116.07  123.81  131.55  139.28  147.02  154.87     171     171
     298     298  330.36  336.26  343.28  350.31  357.34  367.36  374.48   381.6
  388.72  395.85  402.97  411.22  418.42  425.63  432.83  440.04  447.24  454.45
  461.65  468.86  476.06  483.26  490.47  497.67  504.88  512.08  519.36  526.73
  534.09  541.45  548.82  556.18  563.54   570.9  578.27  584.54  591.92   599.3
  148.92  143.58  138.83  135.56  134.87  134.65  134.48  133.74     132   134.5
   134.5     132  131.26  131.04  130.67  130.43  130.07   129.9  129.89  129.92
  129.96  130.03   130.1  130.16  130.26  130.51  130.58  130.66  130.87  130.89
  131.02  131.13   131.3  131.38  131.41  131.65  131.84  131.93  132.08  132.14
  132.29  132.45  132.51  132.76  132.92  133.02  133.19  133.33   133.3  133.47
                                                                             130
     130
                                                                                
                                                                                
                                                                                
  100.59  108.33  116.07  123.81  131.55  139.28  147.02  154.87     183     183
     310     310  330.36  336.26  343.28  350.31  357.34  367.36  374.48   381.6
  388.72  395.85  402.97  411.22  418.42  425.63  432.83  440.04  447.24  454.45
  461.65  468.86  476.06  483.26  490.47  497.67  504.88  512.08  519.36  526.73
  534.09  541.45  548.82  556.18  563.54   570.9  578.27  584.54  591.92   599.3
  148.92  143.58  138.83  135.56  134.87  134.65  134.48  133.74     132   134.5
   134.5     132  131.26  131.04  130.67  130.43  130.07   129.9  129.89  129.92
  129.96  130.03   130.1  130.16  130.26  130.51  130.58  130.66  130.87  130.89
  131.02  131.13   131.3  131.38  131.41  131.65  131.84  131.93  132.08  132.14
  132.29  132.45  132.51  132.76  132.92  133.02  133.19  133.33   133.3  133.47
                                                                             130
     130
                                                                                
                                                                                
                                                                                
BR Coef=-1 , 0 , 0 ,, 0 ,,,0.8,0,,0,
WSPro=,,,, 1 ,,,, 0 ,,,, 0 ,,,,-1 ,-1 ,-1 , 0 , 0 , 0 , 0 , 0
BC Design=,, 0 ,, 0 ,,,,,,
BC Use User HTab Curves=0
BC User HTab FreeFlow(D)= 0

Type RM Length L Ch R = 1 ,34817.73,261.02,266.98,354.83
BEGIN DESCRIPTION:
Under water portion adjusted -2' as indicated by flow depth in bridge inspection report.
END DESCRIPTION:
XS GIS Cut Line= 6
1561543.95272766744306.4420268831561268.93584719744175.727284372
1561224.89081016744163.3946740331561030.99423675744201.744033277
1560889.51653013744246.8151462821560559.24913129744274.376992449
#Sta/Elev= 30
       0  193.78   23.21  183.67  108.33  148.86  123.81  139.52  131.55  136.08
  154.73  134.23   162.5  132.35  170.26  129.36  185.79  121.57  191.88  119.95
  204.44     117  282.41     117  294.47  119.55   304.5  121.14  319.04  127.07
  326.31  128.98  340.85  130.38  390.59  128.67  459.11  129.06  516.75   130.9
  548.24  132.68  562.96  132.59  615.08  134.49  668.48  134.92  696.74  137.41
     749  139.31  833.35  145.58  968.18  157.89 1003.21  161.77 1028.28  165.67
#Mann= 3 , 0 , 0
       0      .1       0  191.88    .035       0  294.47      .1       0
Bank Sta=191.88,294.47
XS Rating Curve= 0 ,0
Exp/Cntr=0.5,0.3

Type RM Length L Ch R = 1 ,34550.76,498.65,554.99,614.86
XS GIS Cut Line= 4
1561712.04490353744165.537962005 1561529.5355204744013.962372631
1561347.02613728743914.9742326441560923.23316297743754.118505195
#Sta/Elev= 30
       0  202.72    63.7  183.61  127.39  163.74  181.99  148.53  200.18  140.41
  218.38  138.92  227.48   137.1  253.17  129.52   269.1  127.02  292.99  124.88
  316.88  119.59  324.84  118.46  348.73  118.03  412.44  118.25  428.36  118.71
  432.38  119.43  452.36  123.23  504.77  125.65  534.72  129.91  587.13  136.12
  617.08  140.85  639.54  145.65  669.49  151.23  706.93   159.4  729.39  164.97
   781.8  173.64  826.72  181.97  856.67  189.56  879.13  197.11  898.16  202.81
#Mann= 3 , 0 , 0
       0     .08       0  316.88    .035       0  432.38      .1       0
Bank Sta=316.88,432.38
XS Rating Curve= 0 ,0
Exp/Cntr=0.3,0.1

Type RM Length L Ch R = 1 ,33995.77,674.38,640.95,610.12
XS GIS Cut Line= 5
1562361.65457214744292.3665163521561965.70201221 743791.23905766
1561835.78007846 743624.196571441561764.63235289743506.648155198
1561467.66793291743191.123458996
#Sta/Elev= 30
       0  231.39   26.76  225.35  115.98  211.08   249.8  184.31  285.48  179.37
   374.7  170.17  428.22  159.29  446.07  158.09  508.52  168.02  535.28   168.8
  553.12  165.32  615.57  143.03  638.68  137.96  674.15  133.32  727.36  129.42
  745.09  126.49  833.77  121.55   855.3  117.85  891.21  116.37  964.85  116.64
  975.37  117.74   987.7  122.25 1006.92  126.72 1054.99  144.43 1083.83  153.26
 1237.63   188.9 1304.92  206.33 1352.99  213.09 1401.05  225.21    1421  227.71
#Mann= 3 , 0 , 0
       0     .07       0   855.3    .035       0  975.37      .1       0
Bank Sta=855.3,975.37
XS Rating Curve= 0 ,0
Exp/Cntr=0.3,0.1

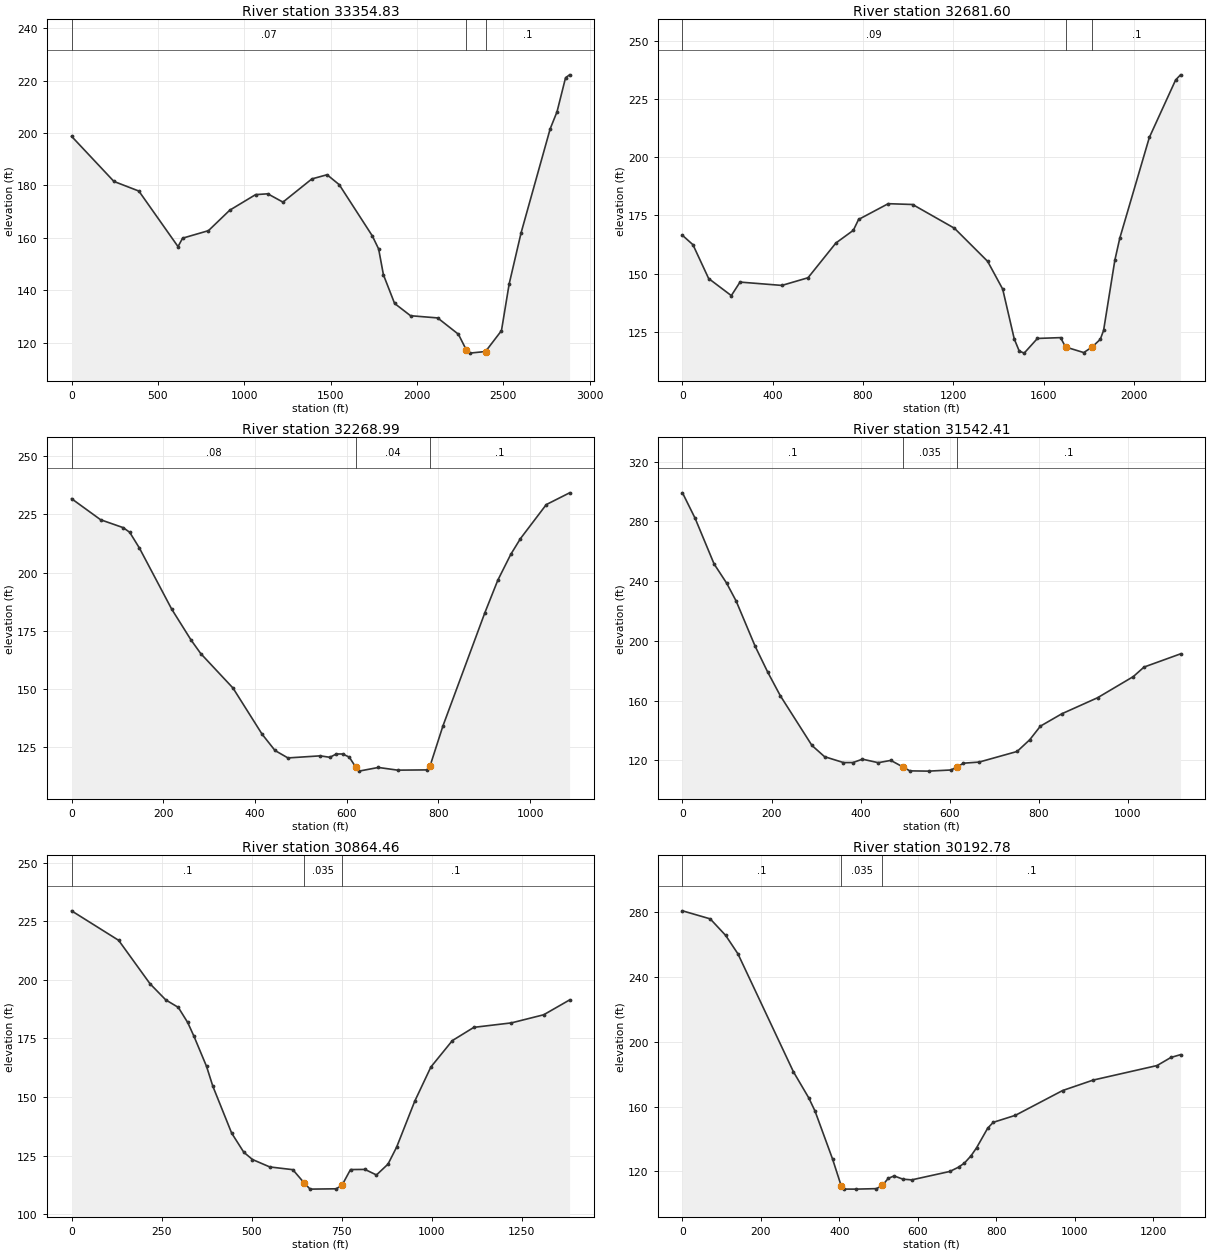
Type RM Length L Ch R = 1 ,33354.83,746.53,673.23,630.02
XS GIS Cut Line= 5
1564224.49757922744412.8132749651563694.90108261744279.992998868
1562766.88727021743571.6091220831562145.11801593743036.454490259
1561897.64766595742788.984140307
#Sta/Elev= 30
       0  198.73  245.37   181.5  389.71  177.83  616.45  156.62  642.87  159.84
  792.58  162.71  915.86  170.52 1065.57  176.47 1136.02  176.78 1224.08  173.61
  1391.4  182.46 1479.47  184.06 1549.92  180.27 1741.19  160.75 1778.13  155.72
 1805.84  145.86 1870.49  134.93 1962.84  130.24 2119.85   129.4 2239.92  123.18
  2286.1  117.15 2304.57  115.96 2396.93  116.57 2489.29  124.53 2533.84  142.35
 2603.14  161.93 2771.43  201.59 2811.02  208.09 2860.52  221.11 2883.81   222.2
#Mann= 3 , 0 , 0
       0     .07       0  2286.1    .035       0 2396.93      .1       0
Bank Sta=2286.1,2396.93
XS Rating Curve= 0 ,0
Exp/Cntr=0.3,0.1

Type RM Length L Ch R = 1 ,32681.60,441.36,412.61,390.16
XS GIS Cut Line= 4
1564220.77557631743274.6447021071562961.77017082742686.902620941
1562473.01622964742535.3270315981562179.14518909742451.805788457
#Sta/Elev= 30
       0  166.44   46.35  162.42  115.88   147.9  216.31  140.56  254.93  146.37
  440.34  144.94  556.21  148.23  679.82  163.17  757.07  168.62  780.25  173.28
  911.57  180.05 1019.73   179.7 1205.13  169.49 1351.91   155.3 1418.76  143.35
 1470.06  121.92 1492.04  116.75 1514.03  115.85 1572.66  122.16 1675.27  122.51
 1697.25  118.49 1777.87  116.09 1814.51  118.43 1851.16  121.78 1865.82   125.6
 1915.71  155.77 1937.54  165.21 2068.53  208.51 2184.97   233.2 2206.67  235.41
#Mann= 3 , 0 , 0
       0     .09       0 1697.25    .035       0 1814.51      .1       0
Bank Sta=1697.25,1814.51
XS Rating Curve= 0 ,0
Exp/Cntr=0.3,0.1

Type RM Length L Ch R = 1 ,32268.99,757.22,726.58,686.15
XS GIS Cut Line= 2
1563419.59031825742263.1096466181562340.00091654742145.561230376
#Sta/Elev= 30
       0   231.8   63.37  222.73  112.66  219.33  126.74  217.34  147.87  210.58
  218.28  184.29  260.53  170.98  281.65  165.15  352.07  150.29  415.44  130.45
  443.61  123.43  471.77  120.23  542.19  121.13  563.31   120.5  577.39  121.94
  591.48  121.92  605.56  120.56  619.64   116.3  626.68  114.55  668.93  116.13
  711.18  114.97  774.55  115.08  781.59   116.7  809.76  133.98   901.3  182.76
  929.46  196.72  957.63  207.81  978.75   214.6 1035.08  229.25 1085.97  234.32
#Mann= 3 , 0 , 0
       0     .08       0  619.64     .04       0  781.59      .1       0
Bank Sta=619.64,781.59
XS Rating Curve= 0 ,0
Exp/Cntr=0.3,0.1

Type RM Length L Ch R = 1 ,31542.41,720.73,677.95,633.59
XS GIS Cut Line= 3
1563367.00286894741384.589904234 1562581.2845078741511.418458596
1562299.78698465741669.180806696
#Sta/Elev= 30
       0  299.21   28.36  282.14   70.91  251.59   99.27  238.64  120.54  226.69
  163.08  196.48  191.45  179.06  219.81  163.21  290.71  129.96  319.08  122.42
  361.62  118.47  382.89  118.49  404.16  120.75  439.62   118.4  467.98  119.93
  496.34  115.32  510.52  112.92  553.07  112.74   602.7   113.5  615.44  115.28
  631.06  118.05  666.52  118.82  751.61  125.92  779.97  133.78  803.91  142.89
  852.06  151.17   932.3  161.92 1012.55  176.09 1036.62  182.46 1118.58  191.31
#Mann= 3 , 0 , 0
       0      .1       0  496.34    .035       0  615.44      .1       0
Bank Sta=496.34,615.44
XS Rating Curve= 0 ,0
Exp/Cntr=0.3,0.1

Type RM Length L Ch R = 1 ,30864.46,813.25,671.67,458.4
XS GIS Cut Line= 4
1563134.99941581740462.7628505981562763.79389086 740738.07361494
1562374.02808969740954.6101711541562210.07898283741400.056801096
#Sta/Elev= 30
       0  229.44  130.73  216.85  217.88  198.31  261.45  191.44  296.31  188.24
  322.46  181.79  339.89  175.89  374.75  163.06  392.18  154.61  444.47  134.59
  478.17  126.43   502.2  123.33  550.24  120.16   614.3  118.99  646.33  113.24
  662.35  110.69  734.42  110.83  750.43  112.25  774.46  119.04   814.5   119.1
  846.53  116.73  878.56  121.36  902.58  128.64  952.79  148.21  997.54  162.79
 1057.21  174.07 1116.89  179.72 1221.31  181.63 1310.82  185.09 1382.69  191.42
#Mann= 3 , 0 , 0
       0      .1       0  646.33    .035       0  750.43      .1       0
Bank Sta=646.33,750.43
XS Rating Curve= 0 ,0
Exp/Cntr=0.3,0.1

Type RM Length L Ch R = 1 ,30192.78,1268.43,1238.48,1179.43
XS GIS Cut Line= 4
1561807.93966413740209.1057418881561978.07552971740543.190714329
1562101.81070469740874.1823074071562182.23856844741409.336939231
#Sta/Elev= 30
       0  280.85    70.7  275.88  109.98   265.7   141.4  254.28   282.8   181.5
  322.07  165.32  337.78  157.29  382.39  127.76  405.08  110.73  412.28  109.13
  442.17   109.1  494.48   109.4  509.43  111.39  524.37  115.72  539.32  117.25
  561.74  115.26  584.16  114.81  681.31     120  703.73  122.66  718.68  125.19
  735.35  129.62  749.51  134.57  777.83  146.67  791.98  150.31  848.61  154.66
  968.95  169.95 1046.81   176.4 1209.62  185.36 1245.01  190.36 1269.44  192.08
#Mann= 3 , 0 , 0
       0      .1       0  405.08    .035       0  509.43      .1       0
Bank Sta=405.08,509.43
XS Rating Curve= 0 ,0
Exp/Cntr=0.3,0.1