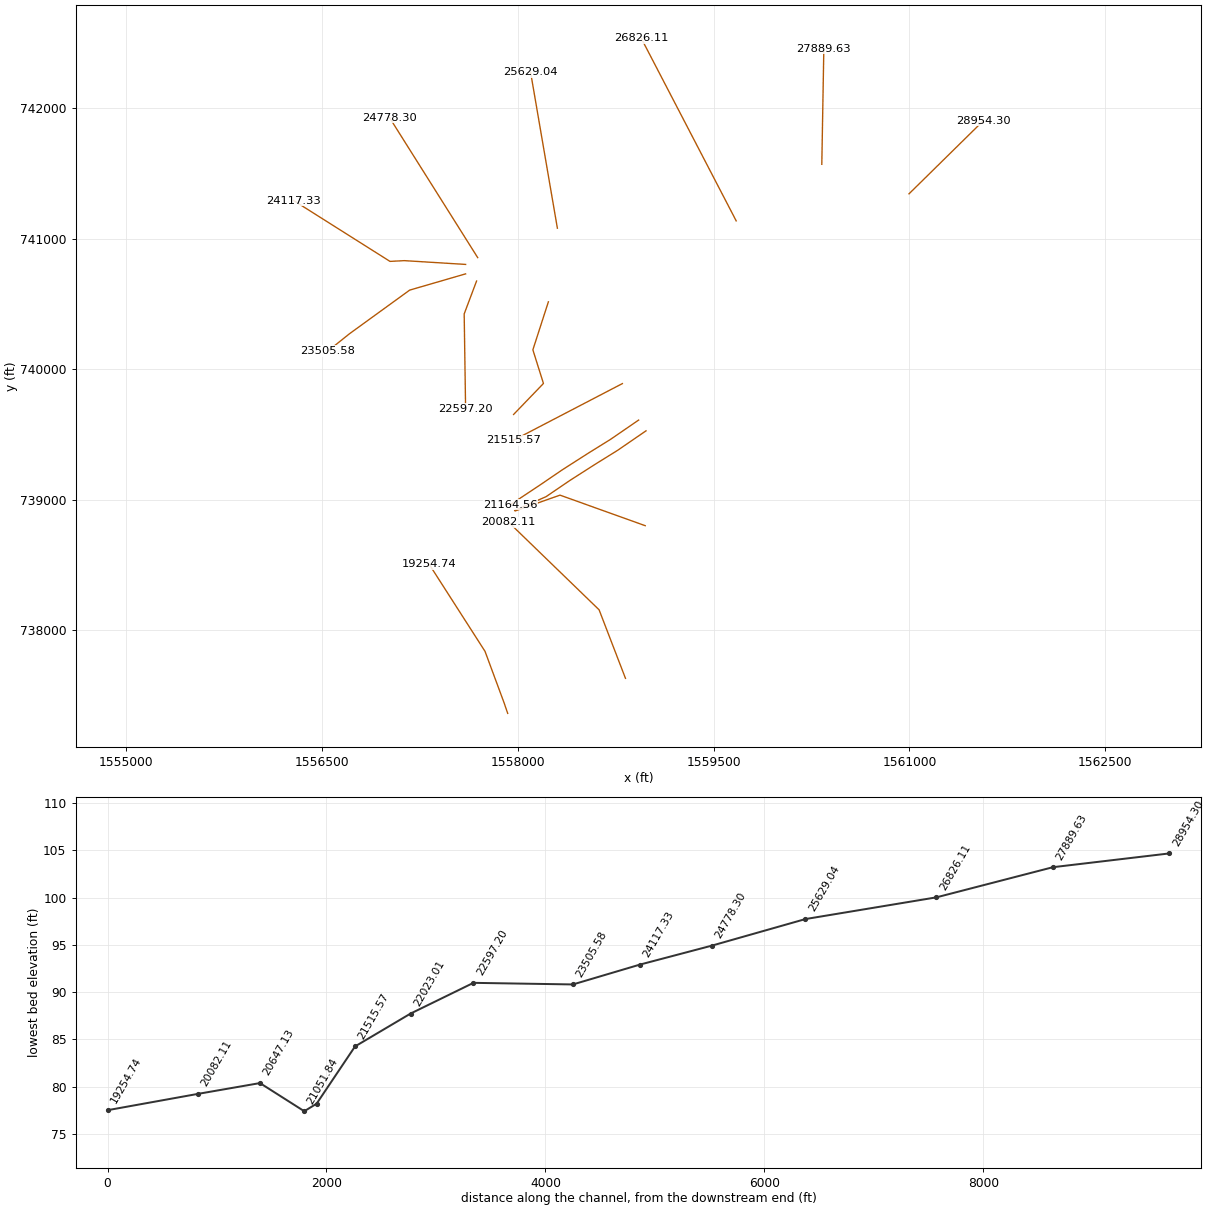
HEC-RAS study OctoraroCreek.prj: OctoraroCreek

--- OctoraroCreek.g01 (geometry) --- (continued)

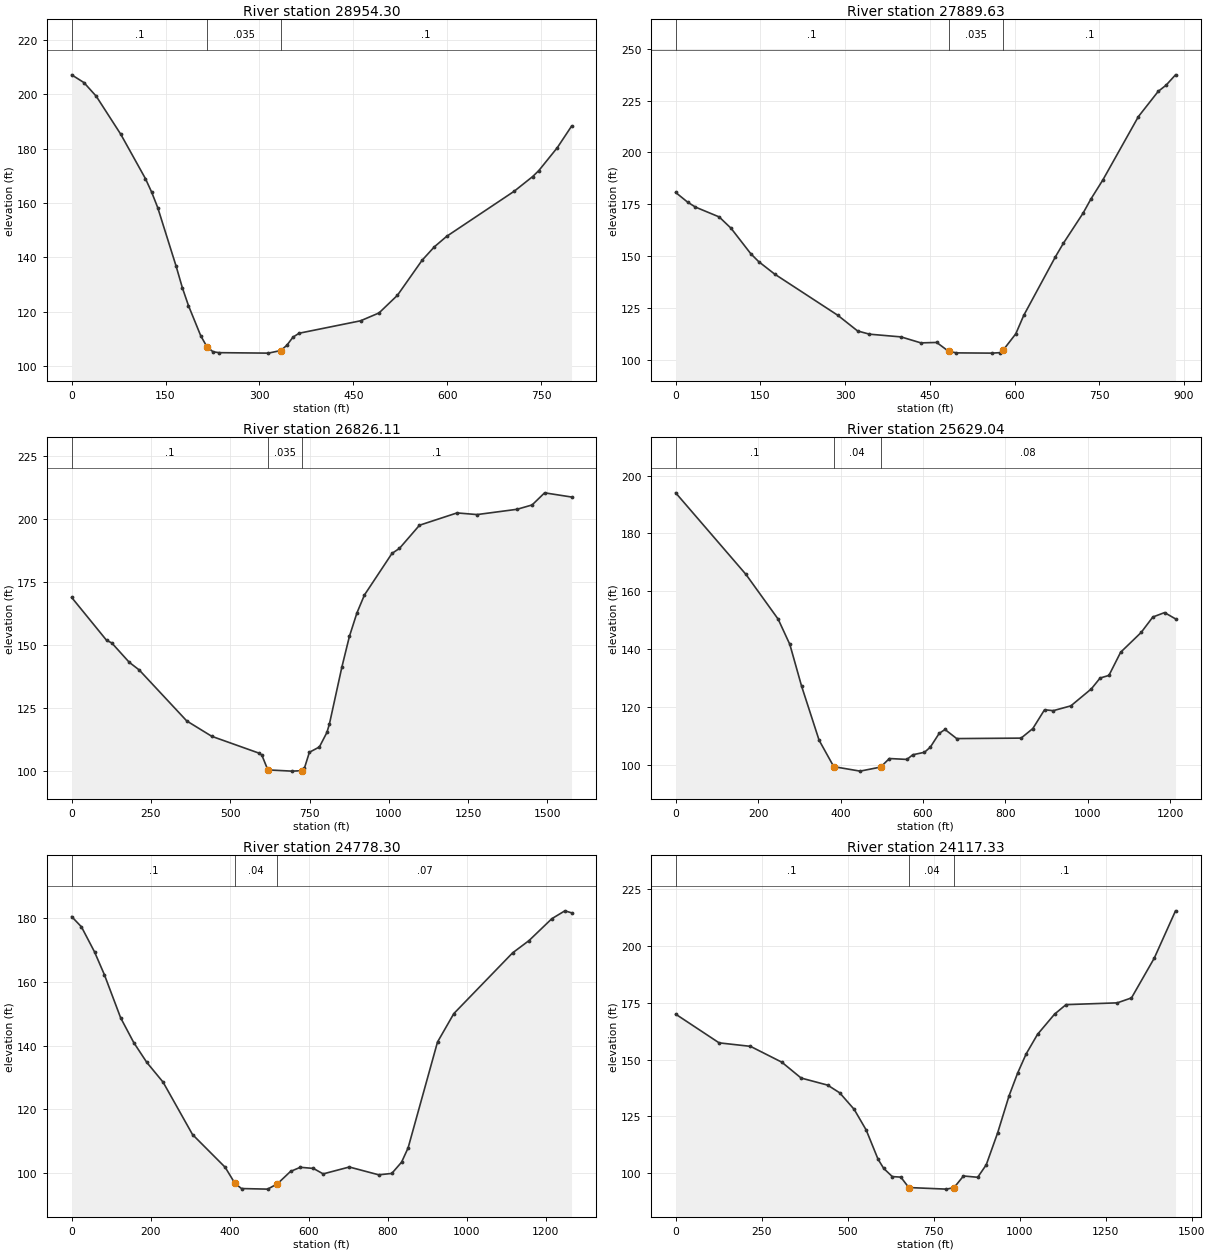
Type RM Length L Ch R = 1 ,28954.30,973.54,1064.67,1139.32
XS GIS Cut Line= 2
  1560997.474268741344.3759723751561566.65607293741904.277639151
#Sta/Elev= 30
       0  207.12   19.64  204.26   39.28  199.24   78.55   185.2  117.83  168.92
  127.65  164.01  137.47  158.25  166.93  136.63  176.74  128.81  186.56  122.19
   206.2  111.07  216.02  107.06  225.84  105.18  235.66  104.86  314.21  104.69
  333.85  105.64  343.67  107.56  353.49  110.56  363.31  112.01   461.5  116.59
  490.96  119.48  520.41  125.99  559.69  138.85  579.33  143.81  598.97  147.67
  706.98  164.29  736.43  169.69  746.25  171.89  775.71  180.31  798.41   188.2
#Mann= 3 , 0 , 0
       0      .1       0  216.02    .035       0  333.85      .1       0
Bank Sta=216.02,333.85
XS Rating Curve= 0 ,0
Exp/Cntr=0.3,0.1

Type RM Length L Ch R = 1 ,27889.63,997.76,1063.52,1100.93
XS GIS Cut Line= 2
1560329.30432306741570.1926667091560344.77121991742454.899167866
#Sta/Elev= 30
       0  180.71      21  176.07   35.01  173.65   77.01  168.91   98.01  163.45
  133.02  151.14  147.02  147.34  175.03  141.38  287.04  121.47  322.05  113.92
  343.05  112.37  399.06  111.05  434.07  108.17  462.07  108.38  483.07  104.12
  497.08  103.35  560.09  103.23  574.09  103.46  579.57  104.62  602.09  112.55
  616.09  121.39   672.1  149.62  686.11  156.11  721.11  170.69  735.11  177.56
  756.12   186.7  819.13  217.29  854.13  229.43  868.13  232.43  884.84  237.43
#Mann= 3 , 0 , 0
       0      .1       0  483.07    .035       0  579.57      .1       0
Bank Sta=483.07,579.57
XS Rating Curve= 0 ,0
Exp/Cntr=0.3,0.1

Type RM Length L Ch R = 1 ,26826.11,1240.04,1197.07,1168.22
XS GIS Cut Line= 2
 1559673.5078956741137.1195542511558946.56374259742535.327031598
#Sta/Elev= 30
       0  168.87  110.45  151.82  126.23  150.87  181.46  143.18  213.02  140.12
  362.92  119.92  441.82  113.83  591.72  107.12  599.61  106.38  618.54  100.52
  694.28  100.04  725.84  100.21  733.73  101.17  749.51  107.51  781.07  109.62
  804.73  115.37  812.62   118.7  852.07  141.35  875.74  153.46  899.41  162.74
  923.08  169.84 1009.86   186.3 1033.53  188.31 1096.65  197.48 1214.99  202.36
 1278.11   201.7 1404.34   203.8 1451.67  205.52 1491.12  210.32 1575.89  208.66
#Mann= 3 , 0 , 0
       0      .1       0  618.54    .035       0  725.84      .1       0
Bank Sta=618.54,725.84
XS Rating Curve= 0 ,0
Exp/Cntr=0.3,0.1

Type RM Length L Ch R = 1 ,25629.04,810.23,850.74,919.96
XS GIS Cut Line= 2
1558303.75083555 741080.785357551558098.46030337742276.032455772
#Sta/Elev= 30
       0  194.01  170.46   165.8  248.59  150.33     277  141.57  305.41  127.18
  348.02  108.42  383.54   99.29  447.46   97.74  497.18   99.14  518.48   102.1
   561.1  101.79   575.3   103.4  603.71  104.26  617.92  106.05  639.22  110.77
  653.43  112.15  681.84     109  838.09  109.16   866.5  112.46  894.91  118.96
  916.22  118.66  958.84  120.32 1008.55   126.2 1029.86  129.95 1051.17  130.85
 1079.58  138.86  1129.3   145.7 1157.71  151.05 1186.12  152.58 1212.75  150.41
#Mann= 3 , 0 , 0
       0      .1       0  383.54     .04       0  497.18     .08       0
Bank Sta=383.54,497.18
XS Rating Curve= 0 ,0
Exp/Cntr=0.3,0.1

Type RM Length L Ch R = 1 ,24778.30,621.06,660.97,721.73
XS GIS Cut Line= 2
1557693.33954714740855.5831489271557018.79783528741926.743807226
#Sta/Elev= 30
       0  180.45   24.82  177.23   57.91  169.38   82.72  162.27  124.08  148.69
  157.17  140.94  190.26  134.71  231.63  128.49  306.08  112.07   388.8  101.79
  413.62   96.72  430.16   95.12  496.34   94.94  521.16   96.62  554.25  100.49
  579.06  101.79  612.15  101.44  636.97   99.72  703.15  101.88   777.6   99.43
  810.69   99.86  835.51   103.4  852.05  107.88   926.5  141.09  967.86  150.02
 1116.77  169.08 1158.13  172.91 1216.03  179.79 1249.12  182.26 1265.86  181.64
#Mann= 3 , 0 , 0
       0      .1       0  413.62     .04       0  521.16     .07       0
Bank Sta=413.62,521.16
XS Rating Curve= 0 ,0
Exp/Cntr=0.3,0.1

Type RM Length L Ch R = 1 ,24117.33,432.58,611.75,742.99
XS GIS Cut Line= 4
1557600.69862533740803.4726304411557131.70395873740832.422918499
1557021.69286408740826.6328608691556283.46051852 741292.73249869
#Sta/Elev= 30
       0  170.04  126.24  157.39  217.41  155.85  308.59  148.87  364.69  141.88
  441.84  138.76   476.9  135.36  518.96  128.07     554  118.93  588.33   106.1
  604.89  102.03  629.72   98.45  654.56   98.21  677.68   93.62  787.01   92.92
  809.24   93.58  836.68   98.72  878.07   98.14  902.91  103.66  936.02  117.73
  969.14  134.03  993.97  144.01 1018.81   152.5 1051.92  161.14 1101.59  170.06
 1134.71  174.23 1283.72  175.02 1325.11   177.2 1391.34  194.74 1453.11  215.58
#Mann= 3 , 0 , 0
       0      .1       0  677.68     .04       0  809.24      .1       0
Bank Sta=677.68,809.24
XS Rating Curve= 0 ,0
Exp/Cntr=0.3,0.1

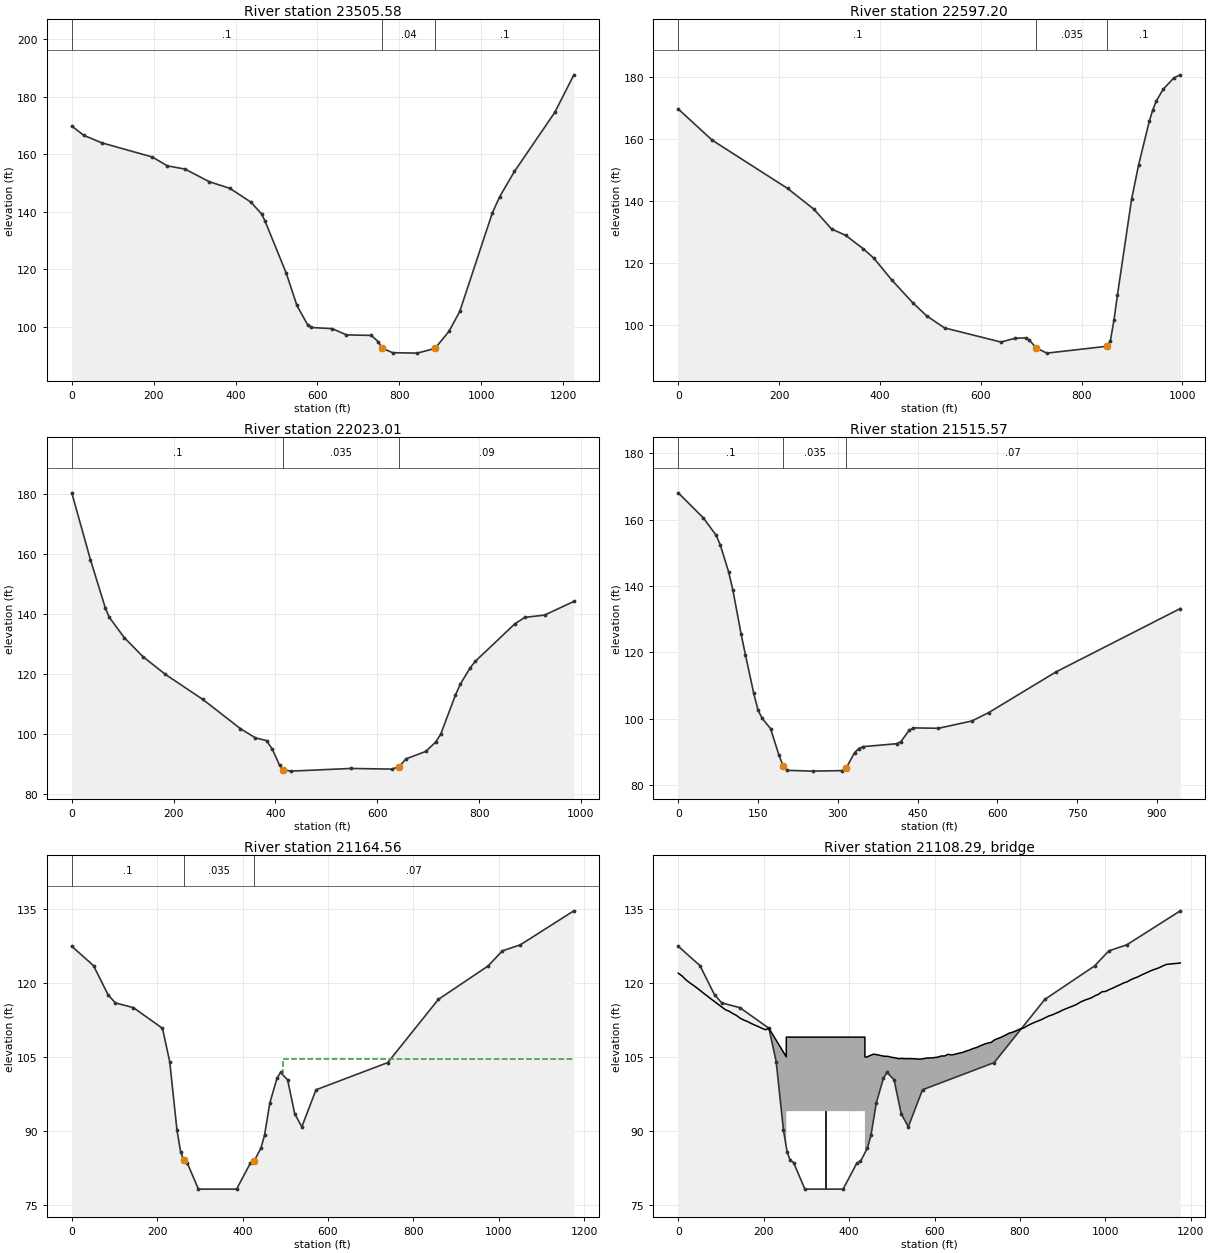
Type RM Length L Ch R = 1 ,23505.58,775.02,908.38,983.17
XS GIS Cut Line= 4
1557600.69862533740731.0969102831557172.23436202740606.610671625
1556709.02975306740270.7873300911556546.90813993740140.511033818
#Sta/Elev= 30
       0  169.83   29.16  166.61   72.89  164.01  196.82  159.05  233.26  155.99
     277  154.84  335.32  150.49  386.34  148.14  437.37  143.37  463.47  139.28
  472.12  136.74     524  118.59  549.94   107.4  575.87  100.73  584.52   99.74
   636.4   99.34  670.98   97.16   731.5   96.99   748.8   94.77  757.44   92.61
  783.38   90.98   843.9   90.82  887.13   92.45  921.72   98.47  947.66  105.35
 1027.29  139.64 1045.25  145.27 1081.17  154.03 1179.95  174.62 1226.29  187.65
#Mann= 3 , 0 , 0
       0      .1       0  757.44     .04       0  887.13      .1       0
Bank Sta=757.44,887.13
XS Rating Curve= 0 ,0
Exp/Cntr=0.3,0.1

Type RM Length L Ch R = 1 ,22597.20,533.73,574.19,608.6
XS GIS Cut Line= 3
 1557684.6544607740676.0913629831557589.81229392 740424.23425059
1557600.69862533739697.571626484
#Sta/Elev= 30
       0  169.72   67.32  159.67  216.92   144.1  269.12   137.4  304.13  131.03
  332.13  128.98  367.13  124.62  388.14  121.59  423.14  114.66  465.14  107.24
  493.15  102.95  528.15   99.13  640.16   94.56  668.17   95.79  689.17   95.92
  696.17   95.25  710.17   92.65  731.18   90.99  850.19    93.2  857.19   95.01
  864.19  101.55  871.19  109.78  899.19  140.58   913.2  151.71   934.2   165.7
   941.2  169.41   948.2   172.3   962.2  176.15   983.2  179.77  995.87  180.74
#Mann= 3 , 0 , 0
       0      .1       0  710.17    .035       0  850.19      .1       0
Bank Sta=710.17,850.19
XS Rating Curve= 0 ,0
Exp/Cntr=0.3,0.1

Type RM Length L Ch R = 1 ,22023.01,657.26,507.45,323.97
XS GIS Cut Line= 4
1558234.70993386740516.8647786081558116.01375282740149.196120232
1558197.07455939739891.5385564861557968.36728369739654.146194384
#Sta/Elev= 30
       0  180.45   36.78  158.12    66.2  141.95   73.56  139.01  102.98  132.24
  139.76  125.88  183.89  119.97  257.45  111.62  331.01  101.92  360.43   98.85
   382.5    97.9  393.69   95.09  408.37   89.62  415.71   88.17  430.38   87.74
   547.8   88.63  628.52   88.42  643.19   89.26  656.46   91.83  695.34   94.31
  714.78   97.43   724.5     100  753.66  113.13  763.38  116.81  782.82  122.21
  792.54  124.33   870.3  136.82  889.74  138.96  928.62  139.72   986.1  144.27
#Mann= 3 , 0 , 0
       0      .1       0  415.71    .035       0  643.19     .09       0
Bank Sta=415.71,643.19
XS Rating Curve= 0 ,0
Exp/Cntr=0.3,0.1

Type RM Length L Ch R = 1 ,21515.57,346.66,351,352.9
XS GIS Cut Line= 2
1558801.59572203739890.5847011511557964.32437034739454.711085692
#Sta/Elev= 30
       0  168.06   47.35  160.48   71.03  155.34   78.92  152.45    94.7  144.26
  102.59  138.88  118.38  125.41  126.27  119.31  142.05  107.64  149.94  102.62
  157.83  100.14  173.62   97.06   189.4   89.04  197.29   85.81  205.19    84.5
  252.54   84.26  307.78   84.41  315.67   85.15  331.45    89.8  339.34   91.06
  347.24   91.63  410.37   92.51  418.26   93.08  434.05   96.51  441.94   97.28
  489.29   97.16  552.42   99.38  583.99  101.91  710.26  114.14  943.93  133.22
#Mann= 3 , 0 , 0
       0      .1       0  197.29    .035       0  315.67     .07       0
Bank Sta=197.29,315.67
XS Rating Curve= 0 ,0
Exp/Cntr=0.5,0.3

Type RM Length L Ch R = 1 ,21164.56,119.38,112.72,112.53
BEGIN DESCRIPTION:
Modified below water portion - Bridge Inspection report indicated a flow depth of 5'.  Assumed this was an "average condition" and was applied to xsections upstream and downstream of  the bridge.
END DESCRIPTION:
XS GIS Cut Line= 6
1558926.14798166739611.1854616251558710.37553263739463.004382104
1558538.73459297739356.3789499251558342.01799802739230.480329126
1558161.52566613739107.5362769961557945.07277864 738964.10364072
#Sta/Elev= 30
       0  127.41   50.95  123.48   84.92  117.59   101.9  115.94  144.36  114.97
  212.29  110.79  229.28  104.04  246.26   90.19  254.75   85.81  261.75    84.1
     270   83.58  296.47    78.2  385.89    78.2  418.33    83.5  426.57   83.81
  443.05   86.55  451.29   89.13  463.82   95.71  480.44  100.66  488.75  101.85
  505.37  100.33  521.99   93.45  538.62   90.83  571.86   98.33  739.72  103.84
   858.3  116.65  974.54  123.41 1008.13  126.48 1050.12   127.7 1175.42  134.59
#Mann= 3 , 0 , 0
       0      .1       0  261.75    .035       0  426.57     .07       0
#XS Ineff= 2 , 0
       0                  494.79       0  104.52
Permanent Ineff=
       F       F
Bank Sta=261.75,426.57
XS Rating Curve= 0 ,0
Exp/Cntr=0.5,0.3

Type RM Length L Ch R = 3 ,21108.29,,,
BEGIN DESCRIPTION:
Conowingo Rd.  CE042407PF-3
Top of road obtained from DEM.
Opening from MDE2 bridge/culvert surveys.
END DESCRIPTION:
Bridge Culvert--1,0,-1,-1, 0
Deck Dist Width WeirC Skew NumUp NumDn MinLoCord MaxHiCord MaxSubmerge Is_Ogee
30,53,2.6,0, 116, 120, , , 0.95, 0, 2,2,,
       0    8.97   17.46   25.95   34.44   42.93   51.43   59.92   68.41    76.9
   85.39   93.88  102.38  110.87  119.36  127.85  136.34  144.83  153.33  161.82
  170.31   178.8  187.29  195.78  204.28  212.29     253     253     437     437
  440.78  449.09   457.4  465.71  474.02  482.33  490.64  498.95  507.26  515.58
  523.89   532.2  540.51  548.82  557.13  565.44  573.75  582.06  590.37  598.68
  606.99  615.31  623.62  631.93  640.24  648.55  656.86  665.17  673.28  681.75
  690.22  698.69  707.16  715.63   724.1  732.57  741.04  749.51  757.98  766.45
  774.92  783.39  791.86  800.32  808.79  817.26  825.73   834.2  842.67  851.14
  859.61  868.08  876.55  885.02  891.27  899.67  908.06  916.46  924.86  933.26
  941.65  950.05  958.45  966.85  975.24  983.64  992.04 1000.44 1008.83 1017.23
 1025.63 1034.02 1042.42 1050.82 1059.22 1067.61 1076.01 1084.41 1092.81  1101.2
  1109.6    1118  1126.4 1134.79 1143.19 1175.42
  121.95  121.39  120.65  120.07  119.55  119.02  118.44  117.86   117.3  116.73
  116.18  115.62  115.07  114.53  114.23  113.78  113.39  112.83  112.46  112.17
  111.79  111.45  111.15   110.8  110.49  110.79     105     109     109     105
  104.94  105.27  105.55  105.43  105.27  105.12  105.11  104.92  104.81  104.64
  104.69  104.63  104.65  104.62  104.59  104.52  104.63  104.76  104.78  104.84
  104.94  105.16  105.19  105.52  105.39  105.55  105.74  105.88  106.15  106.38
  106.69   106.9  107.24  107.55  107.78  107.93  108.48  108.75  109.06  109.42
   109.8  110.01  110.31  110.66  110.85   111.3  111.66  111.99  112.29  112.58
  112.95   113.3  113.53  113.87  114.09  114.47  114.76  115.06  115.33  115.66
   116.1  116.43  116.69  116.95  117.35  117.67  118.19  118.26  118.62  118.93
  119.29   119.6  119.96   120.2  120.62  120.93   121.2  121.58  121.91  122.23
  122.57  122.81  123.08  123.44  123.74  124.01
                                                                                
                                                                                
                                                              94      94
                                                                                
                                                                                
                                                                                
                                                                                
                                                                                
                                                                                
                                                                                
                                                                                
                                                
       0   43.49   51.98   60.48   68.97   77.46   85.95   94.44  102.93  111.43
  119.92  128.41   136.9  145.39  153.88  162.38  170.87  179.36  187.85  196.34
  204.83  213.33  221.82  230.31   238.8  247.29  255.78  264.28  272.77  281.26
     313     313     497     497  500.78  509.09   517.4  525.71  534.02  542.33
  550.64  558.95  567.26  575.58  583.89   592.2  600.51  608.82  617.13  625.44
  633.75  642.06  650.37  658.68  666.99  675.31  683.62  691.93  700.24  708.55
  716.86  725.17  733.28  741.75  750.22  758.69  767.16  775.63   784.1  792.57
  801.04  809.51  817.98  826.45  834.92  843.39  851.86  860.32  868.79  877.26
  885.73   894.2  902.67  911.14  919.61  928.08  936.55  945.02  951.27  959.67
  968.06  976.46  984.86  993.26 1001.65 1010.05 1018.45 1026.85 1035.24 1043.64
 1052.04 1060.44 1068.83 1077.23 1085.63 1094.02 1102.42 1110.82 1119.22 1127.61
 1136.01 1144.41 1152.81  1161.2  1169.6    1178  1186.4 1194.79 1203.19 1211.25
     124  123.33  122.58  121.95  121.39  120.65  120.07  119.55  119.02  118.44
  117.86   117.3  116.73  116.18  115.62  115.07  114.53  114.23  113.78  113.39
  112.83  112.46  112.17  111.79  111.45  111.15   110.8  110.49  110.33  110.22
     105     109     109     105  104.94  105.27  105.55  105.43  105.27  105.12
  105.11  104.92  104.81  104.64  104.69  104.63  104.65  104.62  104.59  104.52
  104.63  104.76  104.78  104.84  104.94  105.16  105.19  105.52  105.39  105.55
  105.74  105.88  106.15  106.38  106.69   106.9  107.24  107.55  107.78  107.93
  108.48  108.75  109.06  109.42   109.8  110.01  110.31  110.66  110.85   111.3
  111.66  111.99  112.29  112.58  112.95   113.3  113.53  113.87  114.09  114.47
  114.76  115.06  115.33  115.66   116.1  116.43  116.69  116.95  117.35  117.67
  118.19  118.26  118.62  118.93  119.29   119.6  119.96   120.2  120.62  120.93
   121.2  121.58  121.91  122.23  122.57  122.81  123.08  123.44  123.74  124.01
                                                                                
                                                                                
                                                                                
              94      94
                                                                                
                                                                                
                                                                                
                                                                                
                                                                                
                                                                                
                                                                                
                                                                                
Pier Skew, UpSta & Num, DnSta & Num=  ,345, 2 ,405, 2 , 0 , 0 , 0 ,,
       3       3
       0     100
       3       3
       0     100
BR Coef=-1 , 1 , 0 ,, 0 ,,,0.8,0,0.5,0,
WSPro=,,,, 1 ,,,, 0 ,,,, 0 ,,,,-1 ,-1 ,-1 , 0 , 0 , 0 , 0 , 0
BC Design=,, 0 ,, 0 ,,,,,,
BC Use User HTab Curves=0
BC User HTab FreeFlow(D)= 0

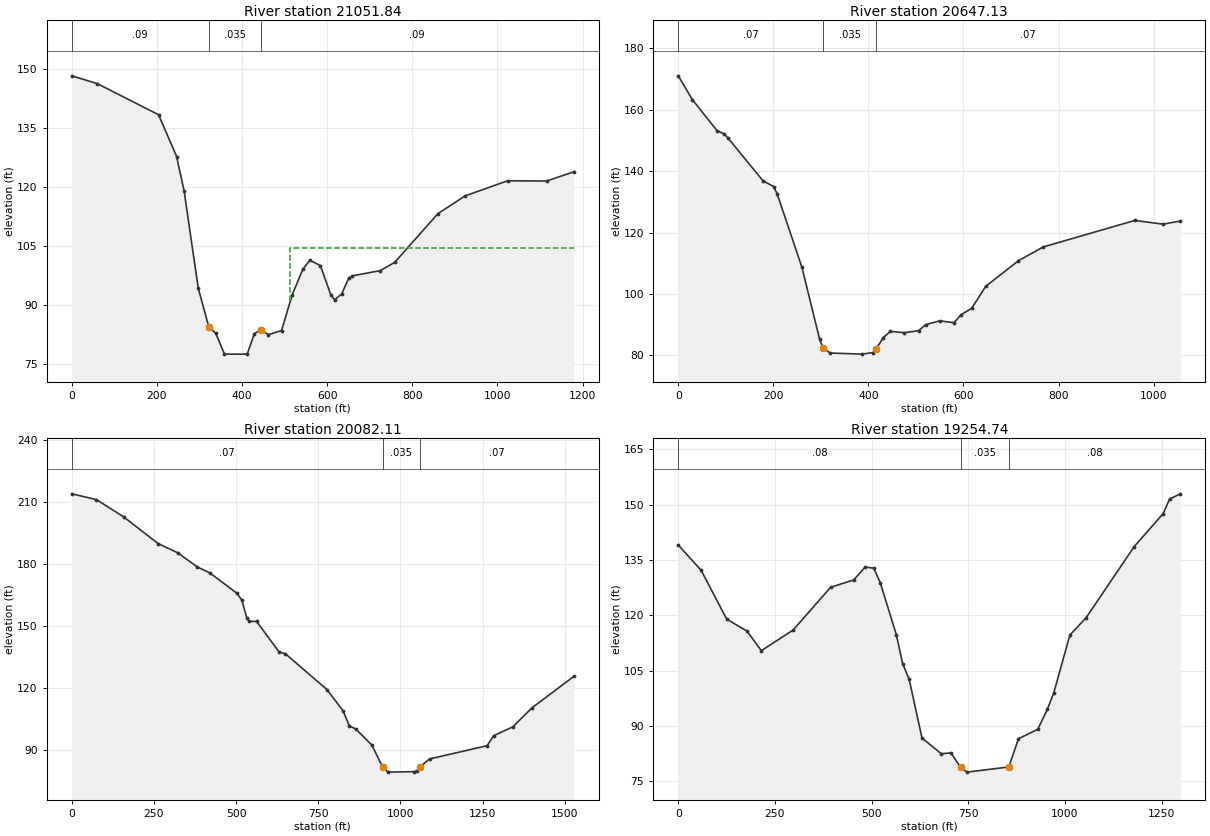
Type RM Length L Ch R = 1 ,21051.84,470.65,404.71,310.69
BEGIN DESCRIPTION:
Modified below water portion - Bridge Inspection report indicated a flow depth of 5'.  Assumed this was an "average condition" and was applied to xsections upstream and downstream of  the bridge.
END DESCRIPTION:
XS GIS Cut Line= 6
1558982.75870606739528.7523015741558765.09387644739379.271635368
 1558592.0738474739271.789496109 1558397.1302508739147.025594279
1558217.29520626739024.5292596221557976.85939012738918.987345621
#Sta/Elev= 30
       0  148.36   59.44  146.39   203.8  138.45  246.26  127.79  264.05  118.92
  297.01   94.25  321.74   84.38  338.22   82.69   358.7    77.4  412.01    77.4
  428.86   82.59  443.56   83.61  461.83   82.37  492.67   83.39   517.6   92.47
  542.53   98.99  559.16  101.34  584.09   99.96  609.02   92.36  617.33   91.26
  633.95   92.74  650.58   96.77  658.89   97.36   724.6   98.69  758.47  100.79
  860.11  113.23  924.42  117.77  1023.8   121.6 1115.54  121.54 1179.36  123.89
#Mann= 3 , 0 , 0
       0     .09       0  321.74    .035       0  443.56     .09       0
#XS Ineff= 2 , 0
       0                  513.21       0  104.52
Permanent Ineff=
       F       F
Bank Sta=321.74,443.56
XS Rating Curve= 0 ,0
Exp/Cntr=0.5,0.3

Type RM Length L Ch R = 1 ,20647.13,597.89,565.02,507.03
XS GIS Cut Line= 3
1558976.43768077738802.1319439111558323.85853899739036.075409845
1557981.56230992738915.409832701
#Sta/Elev= 30
       0  171.05   29.74  163.29    81.8  153.15   96.67  152.13  104.11   150.9
  178.47  136.81  200.78  134.99  208.21  132.53  260.27  108.65  297.45   85.18
  304.88   82.35  319.76   80.74  386.68   80.38  408.99   80.88  416.43   82.04
   431.3   85.76  446.17   87.79  475.92   87.38  505.66   88.01  520.54   89.98
  550.28   91.24  580.02   90.61   594.9    93.2  617.21    95.3  646.95  102.48
  715.51  110.79  767.47  115.28  960.44  123.93 1019.82  122.72 1056.19  123.74
#Mann= 3 , 0 , 0
       0     .07       0  304.88    .035       0  416.43     .07       0
Bank Sta=304.88,416.43
XS Rating Curve= 0 ,0
Exp/Cntr=0.3,0.1

Type RM Length L Ch R = 1 ,20082.11,857.58,827.38,779.68
XS GIS Cut Line= 3
1558825.32953885737632.7641372981558623.34105262738157.627338335
1557929.84849116738829.220134705
#Sta/Elev= 30
       0  213.97      75  211.18  157.51  202.86  262.52  189.91  322.52  185.42
  382.52  178.52  420.03  175.71  502.53  165.83  517.53  162.49  532.53  153.99
  540.03  152.23  562.39  152.18   630.6  137.49  650.09  136.54  776.77  119.17
  825.49  108.93  844.98  101.59  864.47   100.1  913.19   92.32     946   81.68
  961.91   79.24 1039.87   79.47 1049.61   79.74 1059.35   81.76 1088.59   85.62
 1263.99   92.04 1283.48   96.84 1341.94  101.14 1400.41  110.36 1527.77  125.59
#Mann= 3 , 0 , 0
       0     .07       0     946    .035       0 1059.35     .07       0
Bank Sta=946,1059.35
XS Rating Curve= 0 ,0
Exp/Cntr=0.3,0.1

Type RM Length L Ch R = 1 ,19254.74,805.51,862.39,898.96
XS GIS Cut Line= 4
1557923.21225736737364.3656072771557894.56568278737447.668614924
1557749.53648978737839.3265619281557321.59547977738506.624408022
#Sta/Elev= 30
       0  139.09   59.22  132.23  125.41  118.98  177.67  115.77  214.99  110.44
   297.1  116.03  394.14  127.63  453.85  129.61  483.71  133.13  505.74  132.78
  522.37   128.9  563.95   114.8  580.58  106.86  597.21  102.67  630.48   86.74
  680.37    82.5  705.32   82.72  730.27   78.81   746.9   77.51     855   78.91
  879.95   86.56  929.84   89.12  954.79   94.57  971.42   99.09    1013   114.7
 1054.58  119.33 1179.32  138.67 1254.16   147.6 1270.79  151.54 1298.47  152.96
#Mann= 3 , 0 , 0
       0     .08       0  730.27    .035       0     855     .08       0
Bank Sta=730.27,855
XS Rating Curve= 0 ,0
Exp/Cntr=0.3,0.1