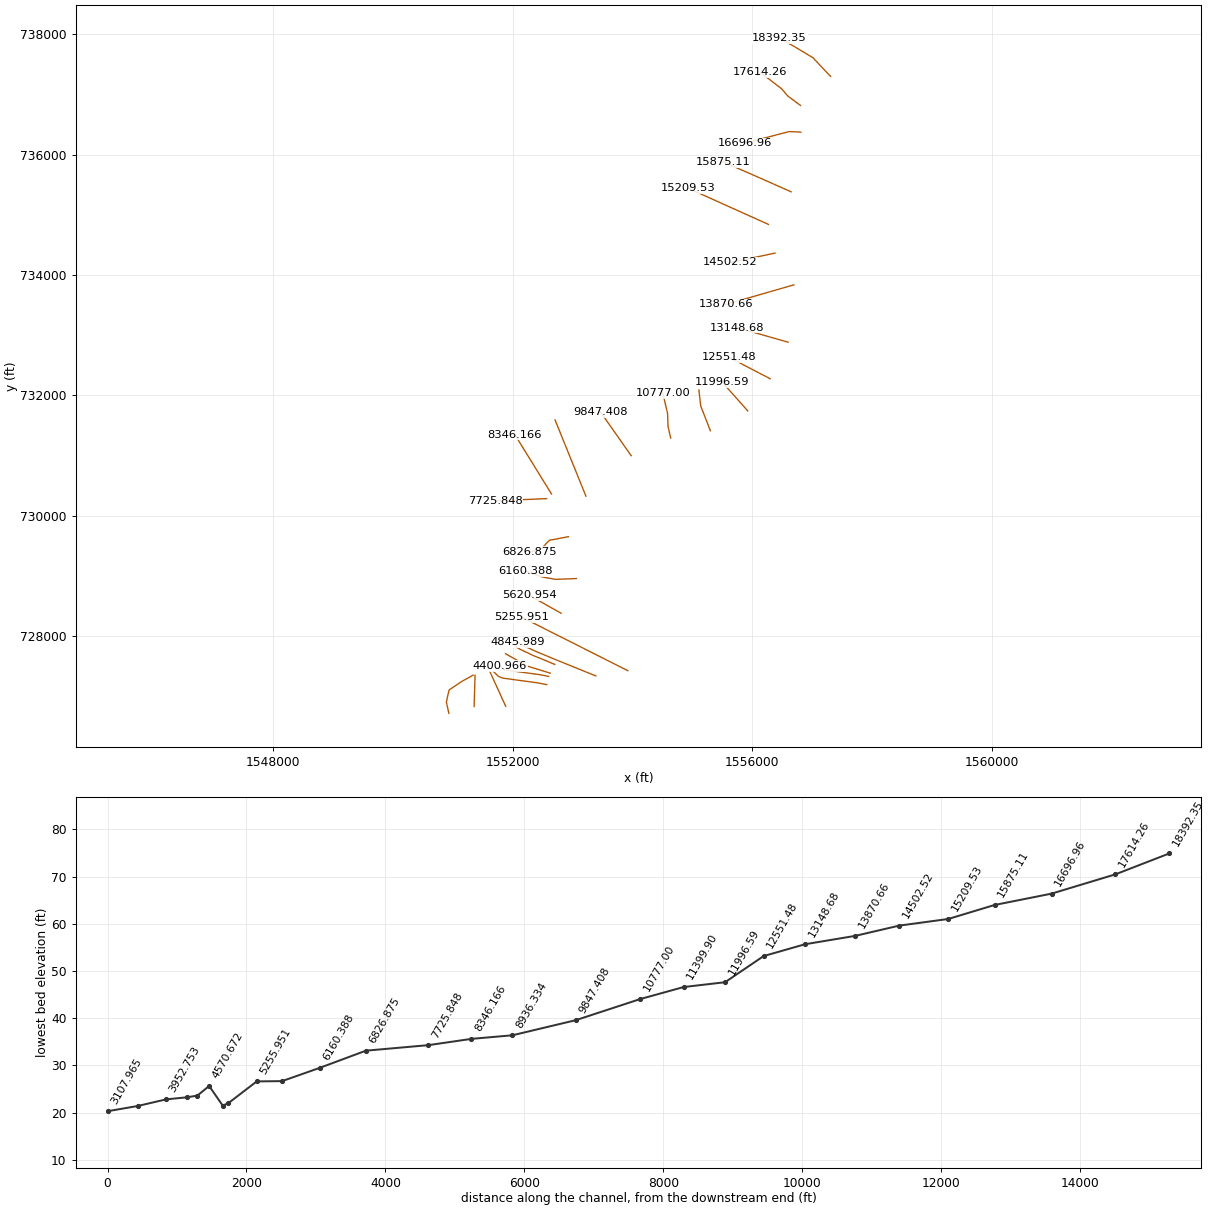
HEC-RAS study OctoraroCreek.prj: OctoraroCreek

--- OctoraroCreek.g01 (geometry) --- (continued)

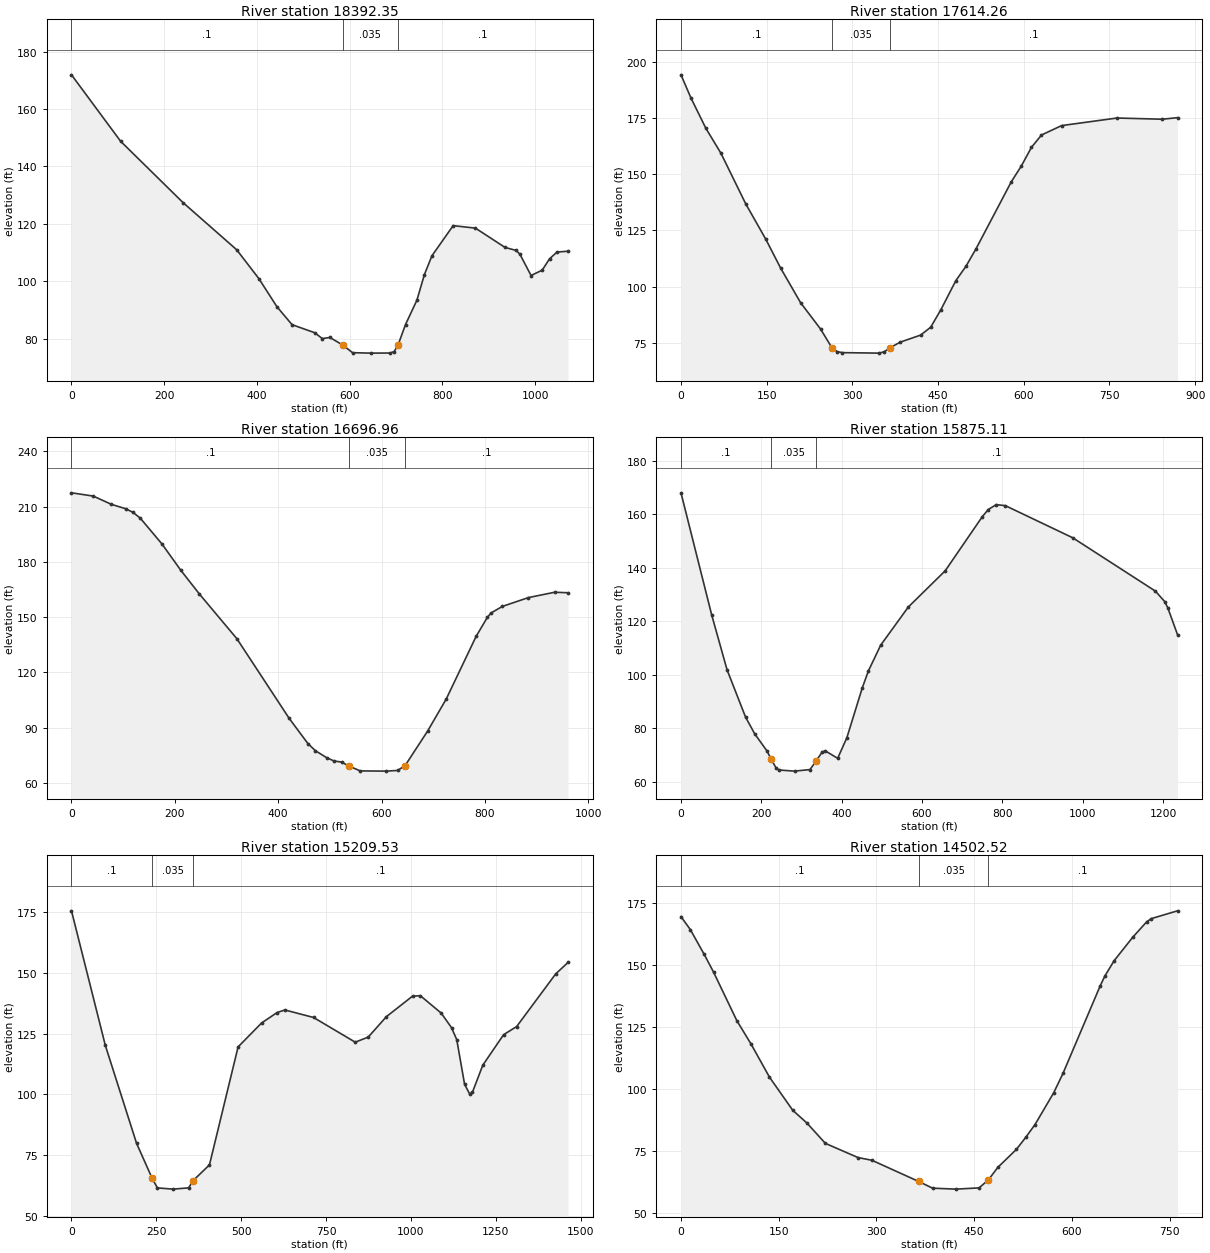
Type RM Length L Ch R = 1 ,18392.35,798.05,778.09,738.7
XS GIS Cut Line= 4
1557307.80512811737302.4311992381557014.76015498737612.714111924
1556702.01467952737799.8688846681556457.23593728737935.309838608
#Sta/Elev= 30
       0  171.94  105.91  148.79  240.71  127.38  356.25  110.97  404.39  100.85
  443.11    91.1  475.74   84.84  524.68   82.03     541   79.99  557.31   80.38
  584.66   77.79  606.26   75.07  647.05   74.92  687.84   74.96  695.99   75.48
  704.15   77.64  720.47   84.89  744.94   93.32  761.26   102.3  777.57  108.88
  823.26  119.36  871.26   118.5  935.26  111.76  959.26  110.72  967.26   109.4
  991.26  101.98 1015.26  103.84 1031.26  107.82 1047.26  110.16 1071.01  110.44
#Mann= 3 , 0 , 0
       0      .1       0  584.66    .035       0  704.15      .1       0
Bank Sta=584.66,704.15
XS Rating Curve= 0 ,0
Exp/Cntr=0.3,0.1

Type RM Length L Ch R = 1 ,17614.26,801.03,917.3,993.68
XS GIS Cut Line= 4
1556805.44231707736819.7688905891556593.66191636 736977.37290974
1556492.69684155737095.5759240981556135.62523571737368.920394838
#Sta/Elev= 30
       0  194.11   17.45  183.82   43.63  170.31   69.81  159.33  113.43  136.75
  148.34  121.13  174.51  108.22  209.42   92.86  244.32   81.19  263.99   72.94
  273.19   71.15   282.4    70.7  346.84   70.48  356.05   71.12  365.25   72.76
  383.67   75.35  419.44   78.49  437.07   81.98   454.7   89.66  481.15   102.7
  498.78  109.04  516.41  116.82  578.12  146.56  595.75  153.61  613.39  161.86
  631.02  167.38  666.28  171.56  763.25  174.92  842.59  174.39  869.13  175.08
#Mann= 3 , 0 , 0
       0      .1       0  263.99    .035       0  365.25      .1       0
Bank Sta=263.99,365.25
XS Rating Curve= 0 ,0
Exp/Cntr=0.3,0.1

Type RM Length L Ch R = 1 ,16696.96,890.9,821.85,752.33
XS GIS Cut Line= 3
1556812.83000548736376.5075867621556616.06993702736385.422824785
1555877.05614179736191.815376833
#Sta/Elev= 30
       0  217.45   42.04  215.69   77.08  211.22  105.11  208.79  119.12  206.83
  133.14  203.69  175.18  189.66  211.43  175.46  247.62   162.5  319.98  138.31
  421.29   95.03  457.47   81.39  471.94    77.5  493.65   73.72  508.12    71.9
  522.59   71.32  537.25   69.12  558.77   66.52  609.43    66.4  631.14   66.77
  645.61   69.39  689.03   88.07  725.21  105.53   783.1  139.55   804.8  149.87
  812.04  152.25  833.75  155.79   884.4   160.6  935.06  163.49  960.91  163.21
#Mann= 3 , 0 , 0
       0      .1       0  537.25    .035       0  645.61      .1       0
Bank Sta=537.25,645.61
XS Rating Curve= 0 ,0
Exp/Cntr=0.3,0.1

Type RM Length L Ch R = 1 ,15875.11,664.96,665.58,664.33
XS GIS Cut Line= 3
1556650.30086072735384.0947786871555946.00790018735694.377691403
1555517.52197309735879.069901317
#Sta/Elev= 30
       0  168.08   76.49  122.38  114.74  101.87  160.63   84.25  183.58   77.93
  214.18   71.52  224.74   68.42  237.13   65.06  244.77    64.4  283.02   63.99
  321.27   64.58  336.57   67.83  351.86    71.2  359.51   71.54  390.11   68.79
  413.06   76.51   451.3   95.09   466.6  101.47   497.2   111.1  566.04  125.38
  657.83  138.92  749.62  159.04  764.92  161.82  784.86  163.66  807.73  163.28
  975.42  151.26 1181.23  131.31  1204.1  127.43 1211.72  125.19 1236.21  115.05
#Mann= 3 , 0 , 0
       0      .1       0  224.74    .035       0  336.57      .1       0
Bank Sta=224.74,336.57
XS Rating Curve= 0 ,0
Exp/Cntr=0.3,0.1

Type RM Length L Ch R = 1 ,15209.53,651.44,707.01,762.56
XS GIS Cut Line= 2
 1556271.5587022734842.3309628811554936.35715249735440.733723074
#Sta/Elev= 30
       0  175.57   99.72  120.18  191.77   79.87  237.76   65.46  253.14   61.53
  299.16   61.03  345.19   61.55  358.62   64.58  406.56   71.01  490.94  119.56
  559.97  129.39     606  133.72  629.01  134.76  713.39  131.67  836.12  121.51
  874.48  123.61  928.17  132.04 1004.88  140.44 1027.89  140.65 1089.26  133.51
 1119.94  127.47 1135.29  122.54  1158.3  104.24 1173.64  100.08 1181.31  100.83
    1212  112.04 1273.36   124.6 1311.72  127.93 1426.78   149.6 1463.16  154.33
#Mann= 3 , 0 , 0
       0      .1       0  237.76    .035       0  358.62      .1       0
Bank Sta=237.76,358.62
XS Rating Curve= 0 ,0
Exp/Cntr=0.3,0.1

Type RM Length L Ch R = 1 ,14502.52,621.63,631.86,636.82
XS GIS Cut Line= 2
1556379.91146536734364.5937798621555633.75493725734209.452323511
#Sta/Elev= 30
       0  169.47    14.3  164.24   35.75  154.19   50.05  147.06    85.8  127.49
  107.25  118.23  135.84  104.75  171.59   91.38  193.04   86.33  221.64   78.06
  271.69   72.35  293.14   71.24  364.75   62.72  386.08   60.01  421.83   59.62
  457.58   60.12  471.88   63.36  486.18   68.35  514.78   75.63  529.08   80.46
  543.38   85.64  571.98   98.41  586.28  106.23  643.47  141.56  650.62  145.51
  664.92  151.72  693.52  161.18  714.97  167.41  722.12  168.67  762.12  171.79
#Mann= 3 , 0 , 0
       0      .1       0  364.75    .035       0  471.88      .1       0
Bank Sta=364.75,471.88
XS Rating Curve= 0 ,0
Exp/Cntr=0.3,0.1

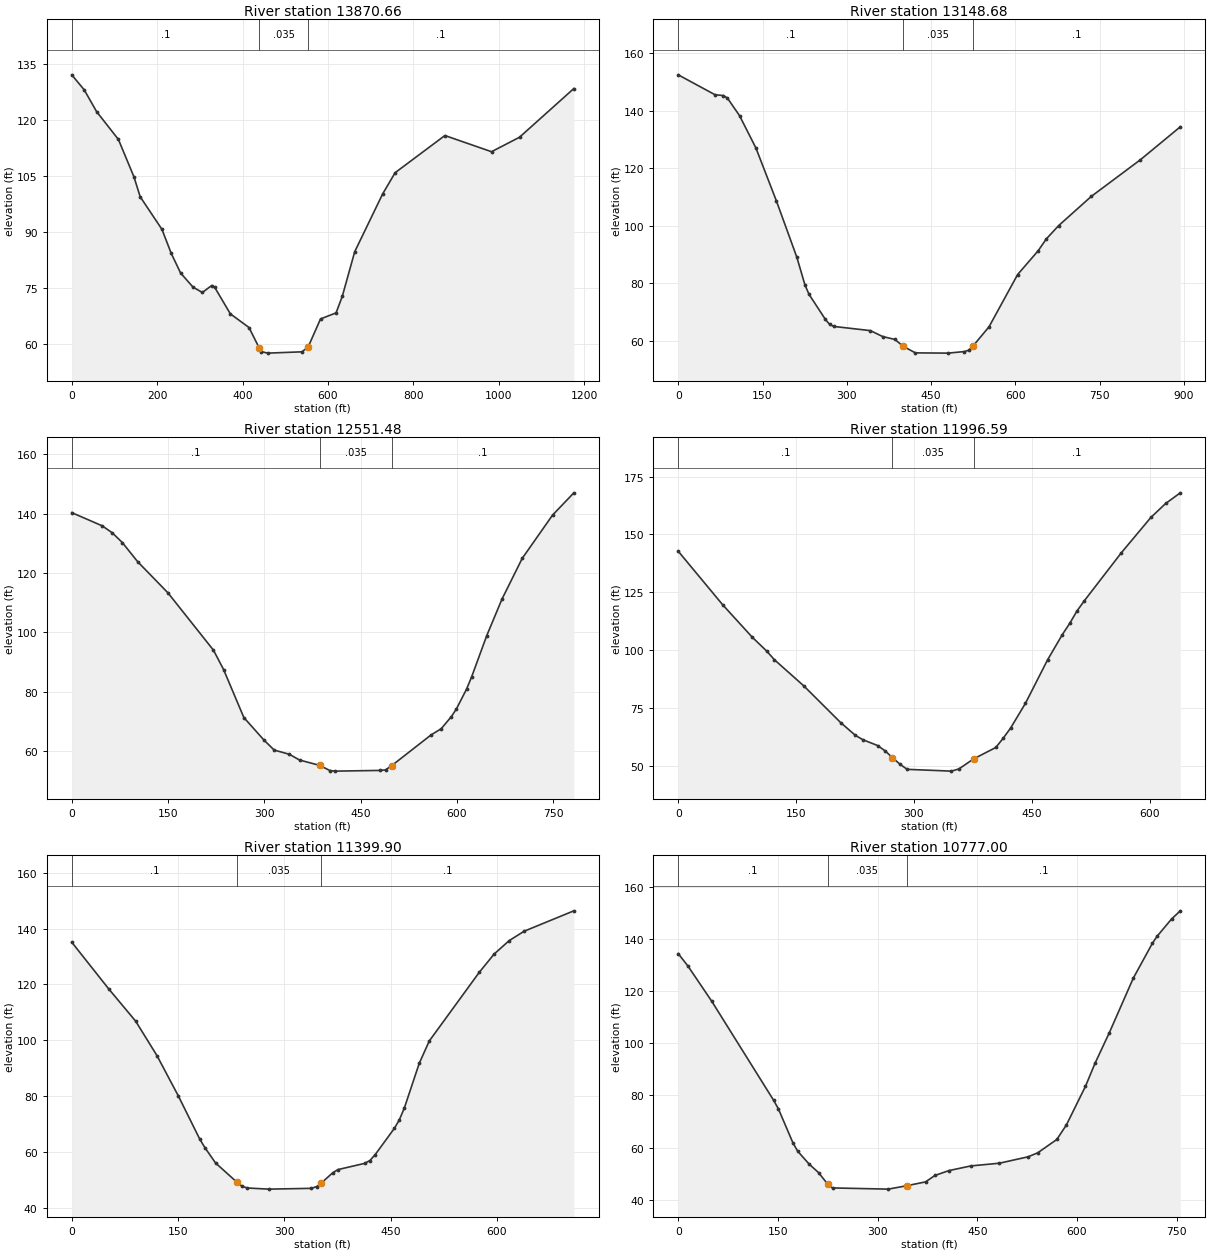
Type RM Length L Ch R = 1 ,13870.66,769.94,721.98,647.61
XS GIS Cut Line= 2
1556695.11950368733837.6053408241555564.80317886 733512.54705134
#Sta/Elev= 30
       0  132.19   29.13  128.16   58.27  122.29  109.26  114.84  145.67  104.79
  160.24   99.45  211.23   90.69  233.08   84.22  254.93   78.97  284.06   75.17
  305.92   73.74  327.77   75.61  335.05   75.08  371.47      68  415.17   64.33
   438.7   58.93  444.31   57.86  458.87   57.45  538.99    57.8  553.56   59.06
   582.7   66.63  619.12   68.26  633.68   72.69  662.82   84.69  728.37  100.23
  757.51  105.91  874.04  115.89   983.3  111.54 1048.85  115.43 1176.13  128.51
#Mann= 3 , 0 , 0
       0      .1       0   438.7    .035       0  553.56      .1       0
Bank Sta=438.7,553.56
XS Rating Curve= 0 ,0
Exp/Cntr=0.3,0.1

Type RM Length L Ch R = 1 ,13148.68,616.49,597.2,579.01
XS GIS Cut Line= 2
 1556599.0795545732884.5935375541555739.64513761733128.387254685
#Sta/Elev= 30
       0  152.49   65.49  145.56   80.04  145.29   87.31  144.46  109.14  138.27
  138.25  127.02  174.63  108.65  211.01   89.05  225.56   79.35  232.84   76.09
  261.94   67.38  269.22   65.71   276.5   64.97  341.98   63.51  363.81   61.44
  385.64   60.44  400.19   58.05  422.02   55.77  480.23   55.68  509.33   56.23
  516.61   56.66  523.89   58.01  552.99   64.84  603.92   83.03   640.3   91.26
  654.86   95.39  676.69  100.01  734.89  110.19  822.21  122.93  893.34  134.41
#Mann= 3 , 0 , 0
       0      .1       0  400.19    .035       0  523.89      .1       0
Bank Sta=400.19,523.89
XS Rating Curve= 0 ,0
Exp/Cntr=0.3,0.1

Type RM Length L Ch R = 1 ,12551.48,578,554.89,521.64
XS GIS Cut Line= 2
1556301.10945581732276.3405261641555606.66674644732635.874694839
#Sta/Elev= 30
       0  140.36    47.3  135.92   63.06  133.56   78.83  130.26  102.47  123.85
  149.77  113.31  220.71   93.96  236.48   87.43  268.01   71.25  299.54    63.6
   315.3   60.27  338.95   58.85  354.71   56.92  386.24    55.1  402.01   53.36
  409.89   53.17  480.83   53.41  488.72   53.59  498.52   55.06  559.66   65.39
  575.42   67.48  591.19   71.55  599.07   74.15  614.84   80.81  622.72   84.92
  646.37    98.9  670.01  111.17  701.54  124.92  748.84  139.53  781.99  147.04
#Mann= 3 , 0 , 0
       0      .1       0  386.24    .035       0  498.52      .1       0
Bank Sta=386.24,498.52
XS Rating Curve= 0 ,0
Exp/Cntr=0.3,0.1

Type RM Length L Ch R = 1 ,11996.59,626.65,596.68,566.71
XS GIS Cut Line= 2
1555925.32634355731743.4479458631555498.89721404732219.318133846
#Sta/Elev= 30
       0  142.73    56.4  119.64   93.99  105.62  112.79   99.48  122.19   95.87
  159.79    84.5  206.78    68.6  225.58   63.07  234.98   61.23  253.78   58.69
  263.18   56.41  272.58   53.49  281.98   50.66  291.38    48.4  347.77   47.63
  357.17   48.57  375.97   52.94  404.17   57.85  413.57   61.86  422.97   66.25
  441.77   76.89  469.97    95.7  488.76  106.64  498.16   111.5  507.56  116.93
  516.96  121.37  563.96  142.08  601.56  157.36  620.35  163.39  638.98  167.99
#Mann= 3 , 0 , 0
       0      .1       0  272.58    .035       0  375.97      .1       0
Bank Sta=272.58,375.97
XS Rating Curve= 0 ,0
Exp/Cntr=0.3,0.1

Type RM Length L Ch R = 1 ,11399.90,646.68,622.91,581.75
XS GIS Cut Line= 3
1555301.13298009731412.8108672051555140.44953997731823.789665923
1555109.54887845  732089.5353553
#Sta/Elev= 30
       0  135.16   52.61  118.28   90.19  106.85  120.26    94.5  150.32    80.1
  180.38    64.7   187.9   61.51  202.93   56.01     233   49.13  240.51   47.61
  248.03   47.01  278.09   46.61  338.22   46.89  345.74   47.51  352.42   48.83
  368.28   52.45   375.8   53.62  413.38   55.84   420.9   56.87  428.41      59
  455.37   68.39  462.42   71.45  469.46   75.66   490.6   91.75   504.7   99.74
  575.17  124.33  596.31  130.93  617.45  135.72  638.59   139.1  708.81  146.42
#Mann= 3 , 0 , 0
       0      .1       0     233    .035       0  352.42      .1       0
Bank Sta=233,352.42
XS Rating Curve= 0 ,0
Exp/Cntr=0.3,0.1

Type RM Length L Ch R = 1 ,10777.00,848.59,929.59,977.88
XS GIS Cut Line= 4
 1554638.8795664731291.3154065011554594.55343595731483.395304829
 1554587.1657476731697.6382683961554508.36373805732032.546809062
#Sta/Elev= 30
       0  134.43   14.37  129.75   50.29  116.21  143.68    78.1  150.86    74.8
  172.42   61.93   179.6   58.67  197.13   53.63  211.14   50.41  225.14   45.92
  232.15   44.53   316.2   44.07  344.22   45.39  372.23   46.85  386.24   49.31
  407.25   51.18  440.26   52.97  483.41   54.02  526.56   56.48  540.94      58
   569.7   63.12  584.09   68.68  612.85   83.53  627.23   92.37  648.81  104.13
  684.76     125  713.53   138.4  720.72  141.12  742.29  147.69  755.55  150.85
#Mann= 3 , 0 , 0
       0      .1       0  225.14    .035       0  344.22      .1       0
Bank Sta=225.14,344.22
XS Rating Curve= 0 ,0
Exp/Cntr=0.3,0.1

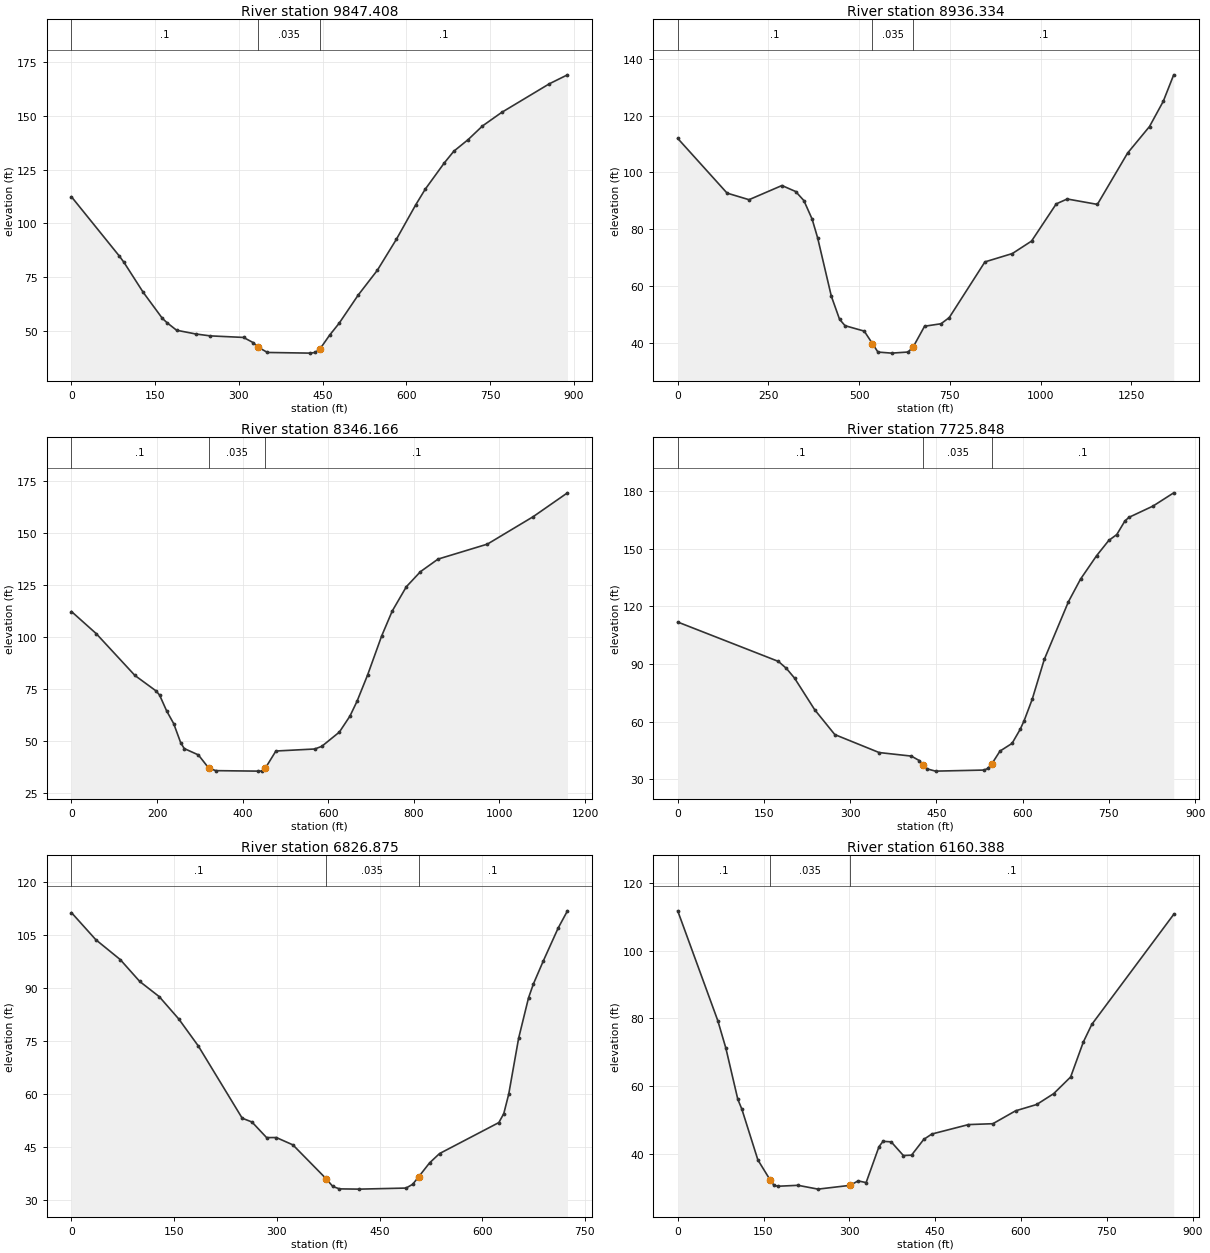
Type RM Length L Ch R = 1 ,9847.408,923.7,911.07,884.56
XS GIS Cut Line= 2
1553978.91273619730998.270433396  1553466.699674731724.726459146
#Sta/Elev= 30
       0  112.41   85.65   84.84   94.22   81.82  128.48   67.94  162.74   55.83
   171.3   53.74  188.43   50.25  222.69   48.51  248.39   47.63  308.34    46.9
  325.47   44.51  334.04   42.45  351.17    39.9  428.25   39.59  436.82   39.91
  445.38   41.54  462.51   47.92  479.64   53.49   513.9   66.65  548.16   78.18
  582.42   92.67  616.68  108.54  633.81  115.87  668.07  128.15   685.2  133.62
   710.9  139.04   736.6  145.39  770.86  151.68  856.51  165.04  888.88   169.2
#Mann= 3 , 0 , 0
       0      .1       0  334.04    .035       0  445.38      .1       0
Bank Sta=334.04,445.38
XS Rating Curve= 0 ,0
Exp/Cntr=0.3,0.1

Type RM Length L Ch R = 1 ,8936.334,573.47,590.17,612.4
XS GIS Cut Line= 2
1553222.90595686730325.9907892351552708.23033185 731591.74806799
#Sta/Elev= 30
       0  111.97  136.02   92.71  196.47   90.39  287.15   95.38  324.93   93.27
   347.6   90.08  370.27   83.57  385.38   77.02  423.17   56.45  445.84   48.31
  460.95   46.05  513.85   44.14  536.52   39.73  551.63   36.76  589.41   36.39
  634.75   36.78  649.17   38.68  680.09   45.86  725.43   46.73   748.1   48.91
  846.33    68.5   921.9   71.44   974.8   75.83 1042.81   88.92 1073.03   90.64
 1156.15   88.74 1239.28  106.79 1299.73  116.15 1337.51  124.99 1366.39  134.34
#Mann= 3 , 0 , 0
       0      .1       0  536.52    .035       0  649.17      .1       0
Bank Sta=536.52,649.17
XS Rating Curve= 0 ,0
Exp/Cntr=0.3,0.1

Type RM Length L Ch R = 1 ,8346.166,485.95,620.32,745.9
XS GIS Cut Line= 2
1552649.12882464730360.4666684271552038.41325049731345.491788074
#Sta/Elev= 30
       0  112.37   57.65  101.78  148.25   81.63  197.67   74.19  205.91   72.19
  222.38   64.59  238.85   58.48  255.32   49.24  263.56   46.48   296.5   43.43
  321.21   36.98  337.69   35.86  436.52   35.63  444.76   35.66  452.99   37.05
   477.7    45.3   568.3   46.27  584.77   47.53  625.95   54.39  650.66   62.07
  667.14   69.16  691.84   81.78  724.79   100.6   749.5  112.59  782.44  124.26
  815.39  131.52  856.57  137.57  971.88  144.77 1078.95  157.97 1158.99  169.43
#Mann= 3 , 0 , 0
       0      .1       0  321.21    .035       0  452.99      .1       0
Bank Sta=321.21,452.99
XS Rating Curve= 0 ,0
Exp/Cntr=0.3,0.1

Type RM Length L Ch R = 1 ,7725.848,819.35,898.97,950.18
XS GIS Cut Line= 2
1552567.86425227730284.1272216441551705.96727258730247.188779652
#Sta/Elev= 30
       0  111.87  175.16   91.38  189.17    87.7  203.19   82.71  238.22   66.26
  273.25   53.31  350.32   43.97  406.37   42.12  420.39   39.76  427.39   37.23
   434.4   35.41  448.41    34.3  532.49   34.85   539.5   35.68   546.5   38.16
  560.51   44.72  581.53   48.73  595.55   55.99  602.55   60.55  616.57   71.67
  637.58   92.42  679.62  122.45  700.64   134.2  728.67  146.42  749.69   154.3
   763.7  157.39  777.71  164.41  784.72  166.32  826.76  172.21  862.69  179.09
#Mann= 3 , 0 , 0
       0      .1       0  427.39    .035       0   546.5      .1       0
Bank Sta=427.39,546.5
XS Rating Curve= 0 ,0
Exp/Cntr=0.3,0.1

Type RM Length L Ch R = 1 ,6826.875,741.26,666.49,585.85
XS GIS Cut Line= 4
1552931.04851407729651.5289695861552613.31541136729591.177430511
1552474.73889135729447.3747094571552279.60690126729397.697496489
#Sta/Elev= 30
       0   111.4   35.63  103.72   71.25   98.11   99.75   91.91  128.25   87.61
  156.75   81.29  185.25   73.66  249.38   53.21  263.63   52.13  285.01   47.72
  299.26   47.73  323.41   45.66  372.02   36.07  381.74   33.88  391.46    33.2
  420.63   33.13  488.68   33.43   498.4    34.5  506.99   36.59  523.12   40.57
  537.57   43.19  624.25   51.97  631.47   54.52  638.69   60.04  653.14   75.84
  667.59   87.27  674.81   91.26  689.26   97.76  710.93  107.05  724.48  111.91
#Mann= 3 , 0 , 0
       0      .1       0  372.02    .035       0  506.99      .1       0
Bank Sta=372.02,506.99
XS Rating Curve= 0 ,0
Exp/Cntr=0.3,0.1

Type RM Length L Ch R = 1 ,6160.388,578.86,539.43,458.11
XS GIS Cut Line= 4
  1553064.176909728955.7112251521552719.81812733728941.510863006
 1552499.7125143728980.5618588921552217.48031697729078.189348519
#Sta/Elev= 30
       0  111.84   70.06   79.34   84.07   71.26  105.09   56.04   112.1   53.16
  140.12   38.12  161.14   32.32  168.14   30.62  175.15   30.33  210.18   30.61
  245.21   29.48  301.26    30.6  315.27   31.92  329.28   31.41  351.76   42.04
  358.87   43.63  373.09   43.47  394.42   39.42  408.64   39.53  429.96   44.19
  444.18   45.79  508.17   48.58  550.82   48.84  590.42   52.65  627.45   54.53
  657.08   57.74  686.71   62.67  708.93   73.03  723.74   78.24  866.84  110.79
#Mann= 3 , 0 , 0
       0      .1       0  161.14    .035       0  301.26      .1       0
Bank Sta=161.14,301.26
XS Rating Curve= 0 ,0
Exp/Cntr=0.3,0.1

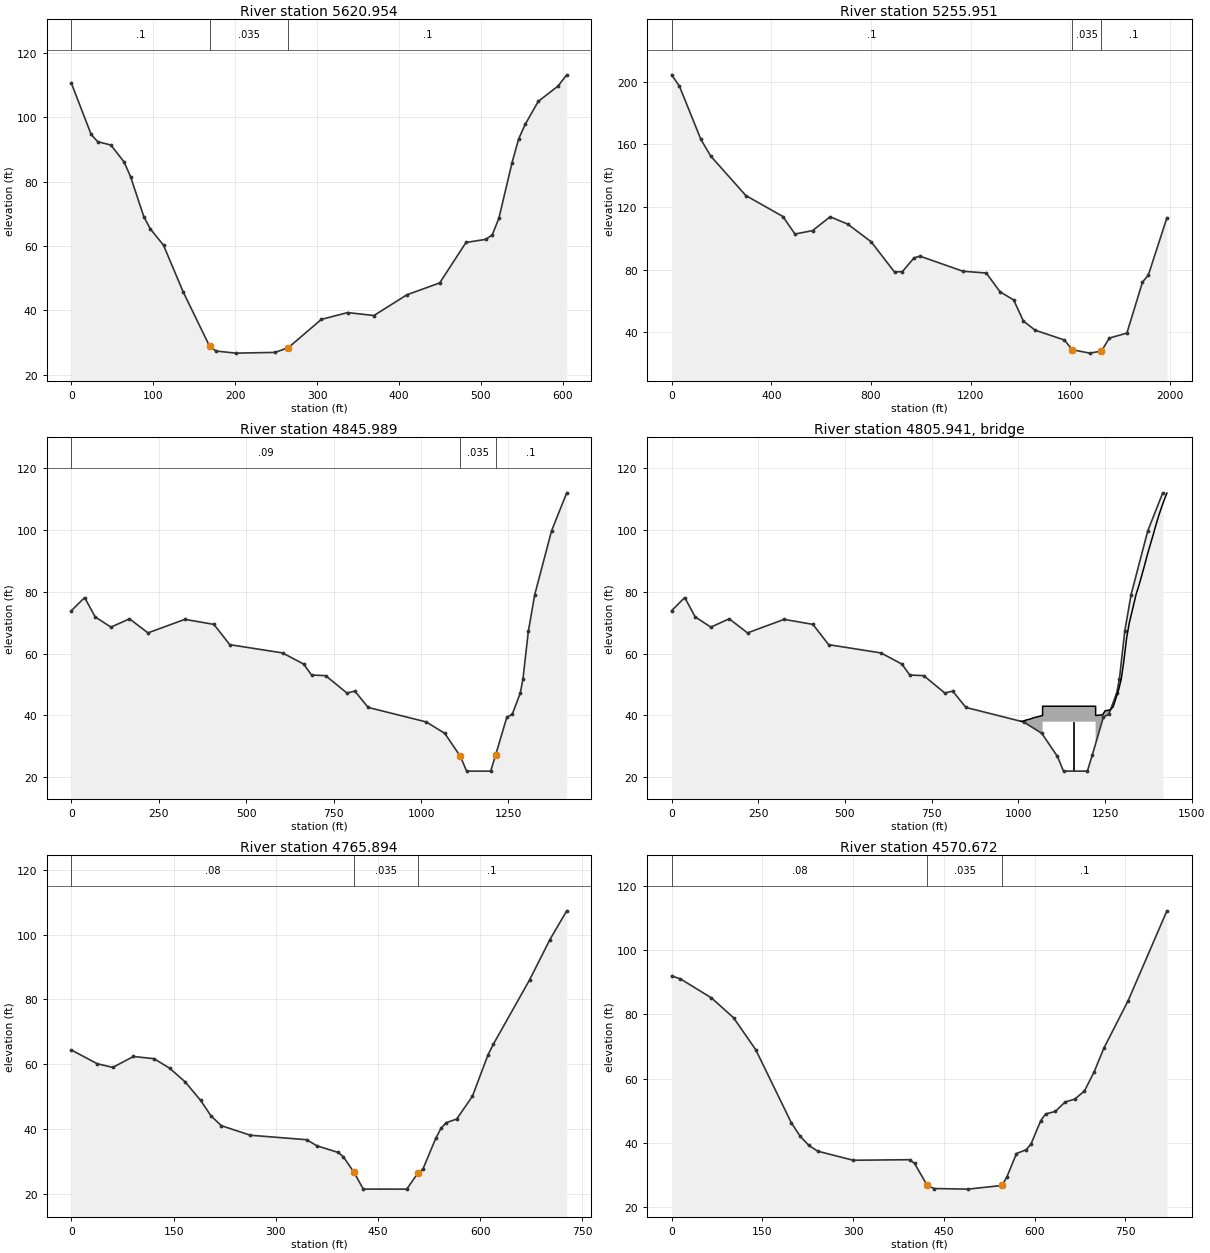
Type RM Length L Ch R = 1 ,5620.954,365.4,365,371.02
XS GIS Cut Line= 2
1552808.57039064728378.8215135631552281.38194653728675.254073069
#Sta/Elev= 30
       0  110.59   24.09   94.68   32.12   92.44   48.18   91.39   64.25   86.15
   72.28   81.51   88.34   69.15   96.37    65.3  112.43   60.25  136.52   45.69
  168.64   28.87  176.68   27.32  200.77   26.68  248.95   26.91  265.01   28.42
  305.17   37.17  337.29   39.29  369.41   38.38  409.57   44.81  449.72   48.52
  481.84    61.1  505.93   62.06  513.97   63.49     522   68.65  538.06   85.91
  546.09   93.28  554.12   97.85  570.18  104.99  594.27  109.74  604.81  113.23
#Mann= 3 , 0 , 0
       0      .1       0  168.64    .035       0  265.01      .1       0
Bank Sta=168.64,265.01
XS Rating Curve= 0 ,0
Exp/Cntr=0.3,0.1

Type RM Length L Ch R = 1 ,5255.951,407.07,409.96,415.81
XS GIS Cut Line= 3
1553924.09589538727423.7061612161553516.81345192727627.977365896
1552148.25355154728314.919883981
#Sta/Elev= 30
       0  204.37   31.32  197.12  117.47  163.08  156.62  152.51  297.58  127.28
  446.37  113.88   494.8  102.69  565.29  104.87  635.78   113.7  706.27  109.03
  800.26   97.76  894.25   78.42  925.58   78.68  972.57   87.47  996.07   88.57
 1168.38   78.94 1262.37   77.77  1317.2   65.83 1372.02    60.6 1411.19   47.12
 1458.18   41.28 1575.67   35.01    1607   28.79 1677.49   26.62 1724.48   27.94
 1755.81   36.23  1826.3   39.41 1888.96   71.99 1912.46   76.47 1986.93  113.08
#Mann= 3 , 0 , 0
       0      .1       0    1607    .035       0 1724.48      .1       0
Bank Sta=1607,1724.48
XS Rating Curve= 0 ,0
Exp/Cntr=0.5,0.3

Type RM Length L Ch R = 1 ,4845.989,80.29,80.1,80.03
BEGIN DESCRIPTION:
Modified below water portion - Bridge Inspection report indicated a flow depth of 4.5'.  Assumed this was an "average condition" and was applied to xsections upstream and downstream of  the bridge.
END DESCRIPTION:
XS GIS Cut Line= 6
1553389.01019274727336.8699421881552728.69335368727603.126732156
1552380.50023158727746.9108419271552166.74376944727848.173247099
1552119.95167086727874.1688574111552088.78101264727895.748543859
#Sta/Elev= 30
       0   73.93   37.74   78.17   67.93    71.9  113.21    68.6  166.05   71.29
  218.88   66.73  324.55   71.11  407.57   69.48  452.86   62.92  603.81   60.25
  664.19   56.64  686.84    53.1  727.18   52.89  787.98   47.28  810.78   47.88
  848.78   42.61 1015.12   37.91 1067.77   34.23 1112.82   26.74 1130.35      22
  1199.2      22 1213.24   27.16 1245.43   39.46  1260.8   40.36 1283.85   47.26
 1291.54   51.79 1306.91   67.21 1325.26    79.1 1373.31   99.73  1416.7  112.05
#Mann= 3 , 0 , 0
       0     .09       0 1112.82    .035       0 1213.24      .1       0
Bank Sta=1112.82,1213.24
XS Rating Curve= 0 ,0
Exp/Cntr=0.5,0.3

Type RM Length L Ch R = 3 ,4805.941,,,
BEGIN DESCRIPTION:
BASIN RUN ROAD - CE033007PF-2
Top of road obtained from DEM.
Opening from MDE2 bridge/culvert surveys.
END DESCRIPTION:
Bridge Culvert--1,0,-1,-1, 0
Deck Dist Width WeirC Skew NumUp NumDn MinLoCord MaxHiCord MaxSubmerge Is_Ogee
24,32,2.6,0, 38, 31, , , 0.95, 0, 1,1,,
 1007.59 1010.67 1018.19 1025.72 1033.24 1040.76 1048.29 1055.81 1063.33    1070
    1070    1223    1223 1242.98 1250.66 1258.35 1266.03 1273.72  1281.4 1289.09
 1296.77 1304.46 1312.14 1319.83 1327.52 1331.59  1339.6 1347.61 1355.62 1363.63
 1371.63 1379.64 1388.73 1397.24 1405.75 1414.27 1422.78 1428.61
   38.14   38.09   38.36   38.64   38.81   39.14   39.39   39.56    39.8      40
      43      43      40   40.22   41.56   41.65   41.89   42.86   45.56    48.2
   51.72   57.71   64.88   69.84   73.47   75.34   79.17   81.99   85.14    88.4
   91.78    94.9   98.38  101.77  104.93  107.75  110.36  111.96
                                                                                
      38      38
                                                                                
                                                                
   197.2  204.78  212.37  219.95  227.54  235.12  242.71  250.29  255.54  263.06
  270.58   278.1  285.63  293.15  300.67  308.19  315.72  323.24  330.76  338.29
  345.81  353.33     370     370     523     523  532.98  540.66  548.35  556.03
  563.72
   42.23   41.82   41.29    40.7   40.23   39.93   39.56   39.26   39.04   38.76
   38.59    38.2   38.12   38.18   38.09   38.36   38.64   38.81   39.14   39.39
   39.56    39.8      40      43      43      40   40.22   41.56   41.65   41.89
   42.86
                                                                                
                                                                                
                              38      38
        
Pier Skew, UpSta & Num, DnSta & Num=  ,1160, 2 ,460, 2 , 0 , 0 , 0 ,,
       3       3
       0      40
       3       3
       0      40
BR Coef=-1 , 1 , 0 ,, 0 ,,,0.8,0,0.5,0,
WSPro=,,,, 1 ,,,, 0 ,,,, 0 ,,,,-1 ,-1 ,-1 , 0 , 0 , 0 , 0 , 0
BC Design=,, 0 ,, 0 ,,,,,,
BC Use User HTab Curves=0
BC User HTab FreeFlow(D)= 0

Type RM Length L Ch R = 1 ,4765.894,204.46,195.22,190.81
BEGIN DESCRIPTION:
Modified below water portion - Bridge Inspection report indicated a flow depth of 4.5'.  Assumed this was an "average condition" and was applied to xsections upstream and downstream of  the bridge.
END DESCRIPTION:
XS GIS Cut Line= 6
1552703.40314211727528.3040517121552467.93410748727626.521082208
1552348.31755894727673.604191735 1552130.7488801727776.653695449
1552077.65515649727806.1502085781552043.24421437727829.973168477
#Sta/Elev= 30
       0   64.39   37.92   60.16   60.68   59.03   91.01    62.4  121.35   61.71
  144.11   58.79  166.86   54.59  189.61   48.87  204.78   44.12  219.95   41.07
  262.65   38.12  345.41   36.73  360.45   34.85  391.46   32.82  399.25   31.46
  414.77   26.68   428.4   21.51  492.23    21.5  508.21   26.35  515.99   27.69
  534.73   37.13  542.41   40.22   550.1      42  565.47    43.1  588.53    50.1
  611.58   62.94  619.27   66.16  672.49      86  702.21   98.38  727.03  107.31
#Mann= 3 , 0 , 0
       0     .08       0  414.77    .035       0  508.21      .1       0
Bank Sta=414.77,508.21
XS Rating Curve= 0 ,0
Exp/Cntr=0.5,0.3

Type RM Length L Ch R = 1 ,4570.672,126.32,169.71,199.88
XS GIS Cut Line= 3
1552627.51577348727383.0211191181552251.20617703727498.399061427
1551880.22171633727706.079357609
#Sta/Elev= 30
       0   91.94   14.64   91.01   65.89    85.1   102.5   78.91  139.11   68.98
  197.68   46.35  212.33   42.13  226.97   39.22  241.61   37.44  300.19   34.63
   393.6    34.8  401.62   33.63  422.54    26.8  433.71   25.84  489.87   25.65
  546.02   26.79  554.04   29.37  570.09   36.72  586.13   37.89  594.16   39.71
   610.2   46.95  618.22   49.02  634.27    49.8  650.31   52.72  666.36   53.63
   682.4   56.15  698.44   62.09  714.49   69.47   754.6   84.22  818.76  112.18
#Mann= 3 , 0 , 0
       0     .08       0  422.54    .035       0  546.02      .1       0
Bank Sta=422.54,546.02
XS Rating Curve= 0 ,0
Exp/Cntr=0.5,0.3

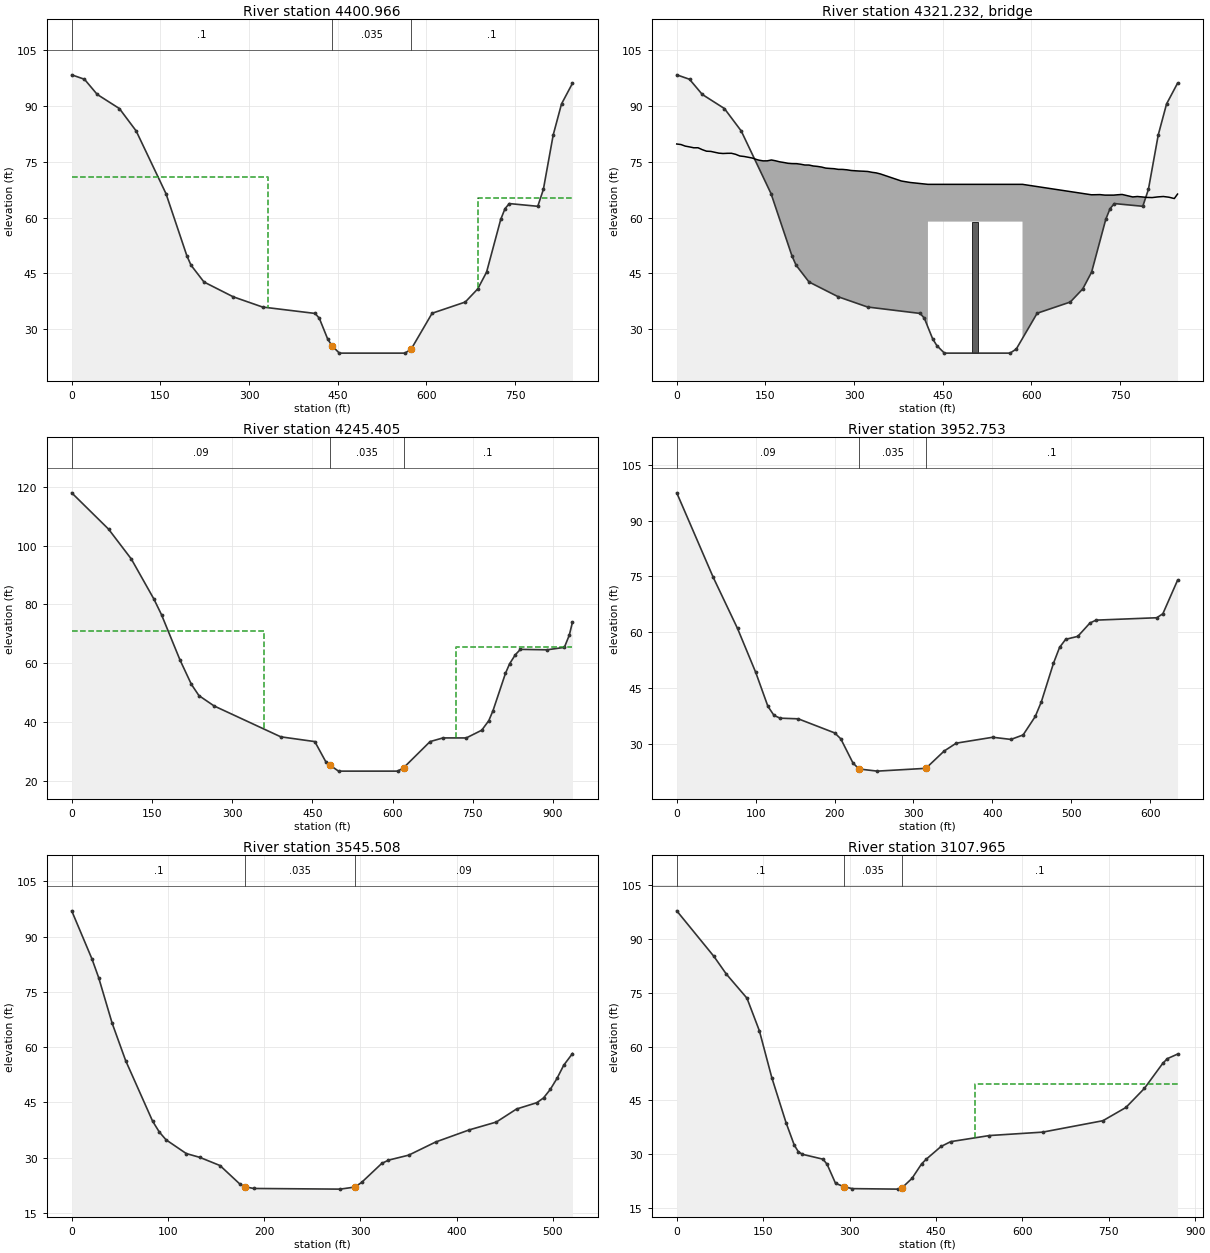
Type RM Length L Ch R = 1 ,4400.966,152.31,155.56,164.49
BEGIN DESCRIPTION:
Modified below water portion - Bridge Inspection report indicated a flow depth of 1.5'.  Assumed this was an "average condition" and was applied to xsections upstream and downstream of  the bridge.
END DESCRIPTION:
XS GIS Cut Line= 6
1552602.57851128727327.9214601811552460.20501496727357.058598936
1551885.01971327727434.4015460311551856.64147344727441.969076648
1551835.18967888727452.325115427 1551787.2536239727500.714179888
#Sta/Elev= 30
       0   98.29   21.59    97.1   43.18   93.03   80.67   89.24  109.07   83.23
  159.51   66.41  194.76   49.77  201.81   47.22  223.77    42.7  273.32   38.72
  322.88   35.98   411.8   34.26  418.87   32.99  433.01   27.43  440.08   25.63
  452.83   23.61  563.85   23.61  574.42    24.7  609.77   34.31  665.87   37.32
  686.95   40.84  701.94   45.35  725.89   59.51  733.13   62.38  740.38   63.74
  788.54   63.01     798   67.53  814.66   82.16  828.72   90.48  847.28   96.03
#Mann= 3 , 0 , 0
       0      .1       0  440.08    .035       0  574.42      .1       0
#XS Ineff= 2 , 0
       0  331.67      71  687.92       0   65.35
Permanent Ineff=
       F       F
Bank Sta=440.08,574.42
XS Rating Curve= 0 ,0
Exp/Cntr=0.5,0.3

Type RM Length L Ch R = 3 ,4321.232,,,
BEGIN DESCRIPTION:
CE033007FS-3  Railroad
Top of road obtained from DEM.
Opening from MDE2 bridge/culvert surveys.
END DESCRIPTION:
Bridge Culvert--1,0,-1,-1, 0
Deck Dist Width WeirC Skew NumUp NumDn MinLoCord MaxHiCord MaxSubmerge Is_Ogee
73,10,2.6,0, 77, 76, , , 0.95, 0, 1,1,,
       0     7.2   14.39   21.59   28.79   35.99   43.18   50.38   57.58   64.78
   71.24   78.34   85.44   92.54   99.64  106.74  113.84  120.94  128.04  135.14
  139.04  146.09  153.14  160.19  167.24  174.29  181.34  188.39  195.44  202.55
  209.63  216.71  223.78  230.86  237.94  245.02  252.09  259.17  266.25  273.33
   280.4  287.99  295.05  302.11  309.17  316.23  323.29  330.35  337.41  344.47
     380     380     395     395     425     425     585     585  701.65  708.75
  715.85  724.55   731.8  739.04  746.29  753.53  763.71  771.49  779.26  787.03
   794.8  804.33  813.79  823.25  832.71  841.82  847.28
   79.73   79.58   79.16   78.95   78.71   78.72   78.21    77.8   77.74   77.49
   77.27   77.18   77.23   77.24   76.96   76.51   76.38   76.17   75.95   75.56
   75.39    75.2   75.21   75.44   75.22   74.94   74.76   74.55   74.46   74.45
    74.3   74.09   74.08   73.83   73.72   73.54   73.26   73.17    73.1   72.92
   72.91    72.8   72.62   72.54   72.47   72.42   72.35   72.13   71.98    71.7
    69.8    69.8    69.4    69.4    68.9    68.9    68.9    68.9    66.1   66.12
   66.15   66.01   66.01   66.01   66.11   66.19   65.81   65.52   65.64   65.53
    65.4   65.35   65.53   65.64   65.45   65.09   66.29
                                                                                
                                                                                
                                                                                
                                                                                
                                                                                
                                            58.9    58.9
                                                                                
                                                        
       0     7.2   14.39   21.59   28.79   35.99   43.18   50.38   57.58   64.78
   71.24   78.34   85.44   92.54   99.64  106.74  113.84  120.94  128.04  135.14
  139.04  146.09  153.14  160.19  167.24  174.29  181.34  188.39  195.44  202.55
  209.63  216.71  223.78  230.86  237.94  245.02  252.09  259.17  266.25  273.33
   280.4  287.99  295.05  302.11  309.17  316.23  323.29  330.35  337.41  344.47
     430     430     445     445     475     475     635     635  701.65  708.75
  715.85  724.55   731.8  739.04  746.29  753.53  763.71  771.49  779.26  787.03
   794.8  804.33  813.79  823.25  832.71  839.03
   79.73   79.58   79.16   78.95   78.71   78.72   78.21    77.8   77.74   77.49
   77.27   77.18   77.23   77.24   76.96   76.51   76.38   76.17   75.95   75.56
   75.39    75.2   75.21   75.44   75.22   74.94   74.76   74.55   74.46   74.45
    74.3   74.09   74.08   73.83   73.72   73.54   73.26   73.17    73.1   72.92
   72.91    72.8   72.62   72.54   72.47   72.42   72.35   72.13   71.98    71.7
    69.8    69.8    69.4    69.4    68.9    68.9    68.9    68.9    66.1   66.12
   66.15   66.01   66.01   66.01   66.11   66.19   65.81   65.52   65.64   65.53
    65.4   65.35   65.53   65.64   65.45   64.67
                                                                                
                                                                                
                                                                                
                                                                                
                                                                                
                                            58.9    58.9
                                                                                
                                                
Pier Skew, UpSta & Num, DnSta & Num=  ,505, 2 ,555, 2 , 0 , 0 , 0 ,,
      10      10
      20      60
      10      10
      20      60
BR Coef=-1 , 1 , 0 ,, 0 ,,,0.8,-1,0.5,0,
WSPro=,,,, 1 ,,,, 0 ,,,, 0 ,,,,-1 ,-1 ,-1 , 0 , 0 , 0 , 0 , 0
BC Design=,, 0 ,, 0 ,,,,,,
BC Use User HTab Curves=0
BC User HTab FreeFlow(D)= 0

Type RM Length L Ch R = 1 ,4245.405,442.23,292.65,199.75
BEGIN DESCRIPTION:
Modified below water portion - Bridge Inspection report indicated a flow depth of 1.5'.  Assumed this was an "average condition" and was applied to xsections upstream and downstream of  the bridge.
END DESCRIPTION:
XS GIS Cut Line= 6
1552570.01706938 727191.760700391552440.13388422 727218.46273753
1551855.02933295727297.5066836331551807.73649551727310.118106946
1551756.03958192727335.0752376621551680.37954389727410.282266185
#Sta/Elev= 30
       0  117.93   68.91  105.58  111.51    95.4  153.82   81.74  167.92   76.46
  202.56   61.03  223.79   52.77  237.95   48.93  266.26   45.42  390.94   34.91
  454.57   33.29  475.78   26.21  482.85   25.27  498.96   23.24   609.6   23.24
   620.9   24.44  670.09   33.29  694.25   34.54  737.71   34.53  766.69   37.16
  779.94   40.43  787.71   43.79  811.03   56.49  818.81   59.77  829.57   62.85
  839.03   64.67  888.79   64.52  921.17   65.34  930.34   69.46  936.39   73.93
#Mann= 3 , 0 , 0
       0     .09       0  482.85    .035       0   620.9      .1       0
#XS Ineff= 2 , 0
       0  360.32      71  717.83       0   65.35
Permanent Ineff=
       F       F
Bank Sta=482.85,620.9
XS Rating Curve= 0 ,0
Exp/Cntr=0.5,0.3

Type RM Length L Ch R = 1 ,3952.753,454.06,407.24,361.93
XS GIS Cut Line= 2
1551883.77180687 726832.757086531551619.29006216727409.646798134
#Sta/Elev= 30
       0   97.43    46.2   74.79   77.01   61.07  100.11   49.28  115.51    40.2
  123.21   37.77  130.91   37.02  154.01   36.84  200.22   33.06  207.92   31.47
  223.32      25  231.02   23.39  254.12   22.82  315.72   23.57  338.83    28.2
  354.23   30.32  400.43    31.9  423.53   31.32  438.93   32.52  454.33   37.47
  462.04    41.4  477.44   51.75  485.14   55.99  492.84   58.15  508.24   58.95
  523.64   62.53  531.34    63.3  608.35   63.94  616.05   65.02  634.63   73.97
#Mann= 3 , 0 , 0
       0     .09       0  231.02    .035       0  315.72      .1       0
Bank Sta=231.02,315.72
XS Rating Curve= 0 ,0
Exp/Cntr=0.3,0.1

Type RM Length L Ch R = 1 ,3545.508,456.95,437.54,389.77
XS GIS Cut Line= 2
1551356.58336276726827.4319507331551372.55877015727347.520213798
#Sta/Elev= 30
       0      97   21.01   83.96   28.01   78.86   42.02   66.48   56.03   56.34
   84.04   39.89   91.04   36.92   98.05   34.81  119.06   31.08  133.06   30.05
  154.07   27.83  175.08   22.71  180.38   22.04  189.09    21.6  278.95   21.42
  294.14   21.98  301.14   23.22  322.15    28.4  329.16   29.29  350.16   30.65
  378.18   34.22  413.19   37.52  441.21   39.64  462.22   43.18  483.23   44.89
  490.23   46.18  497.23   48.49  504.24   51.49  511.24   55.07  520.33   58.25
#Mann= 3 , 0 , 0
       0      .1       0  180.38    .035       0  294.14     .09       0
Bank Sta=180.38,294.14
XS Rating Curve= 0 ,0
Exp/Cntr=0.5,0.3

Type RM Length L Ch R = 1 ,3107.965,180.79,194.18,239.49
XS GIS Cut Line= 6
1550935.04834844 726714.327035711550893.71373019726899.506125435
1550910.24757749726983.8287466321550940.00850263727104.525831908
1551156.60190225727248.3703034071551340.12760724727349.226771921
#Sta/Elev= 30
       0   97.84   64.55   85.14   86.07   80.22  121.93    73.5  143.45   64.42
  164.96    51.4  189.74   38.82     204   32.58  211.14   30.71  218.27      30
  253.94   28.64  261.07   27.21  275.66   21.92  290.08   20.99   304.5   20.44
  383.81    20.3  391.02   20.66  408.38   23.29  425.19   27.36  433.59    28.7
   458.8   32.18   475.6   33.53  542.83   35.23  635.26   36.18  739.86   39.36
  779.79   43.05  811.74   48.34  843.69   55.33  851.68   56.65   869.4   57.92
#Mann= 3 , 0 , 0
       0      .1       0  290.08    .035       0  391.02      .1       0
#XS Ineff= 2 , 0
       0                  516.94       0   49.66
Permanent Ineff=
       F       F
Bank Sta=290.08,391.02
XS Rating Curve= 0 ,0
Exp/Cntr=0.5,0.3