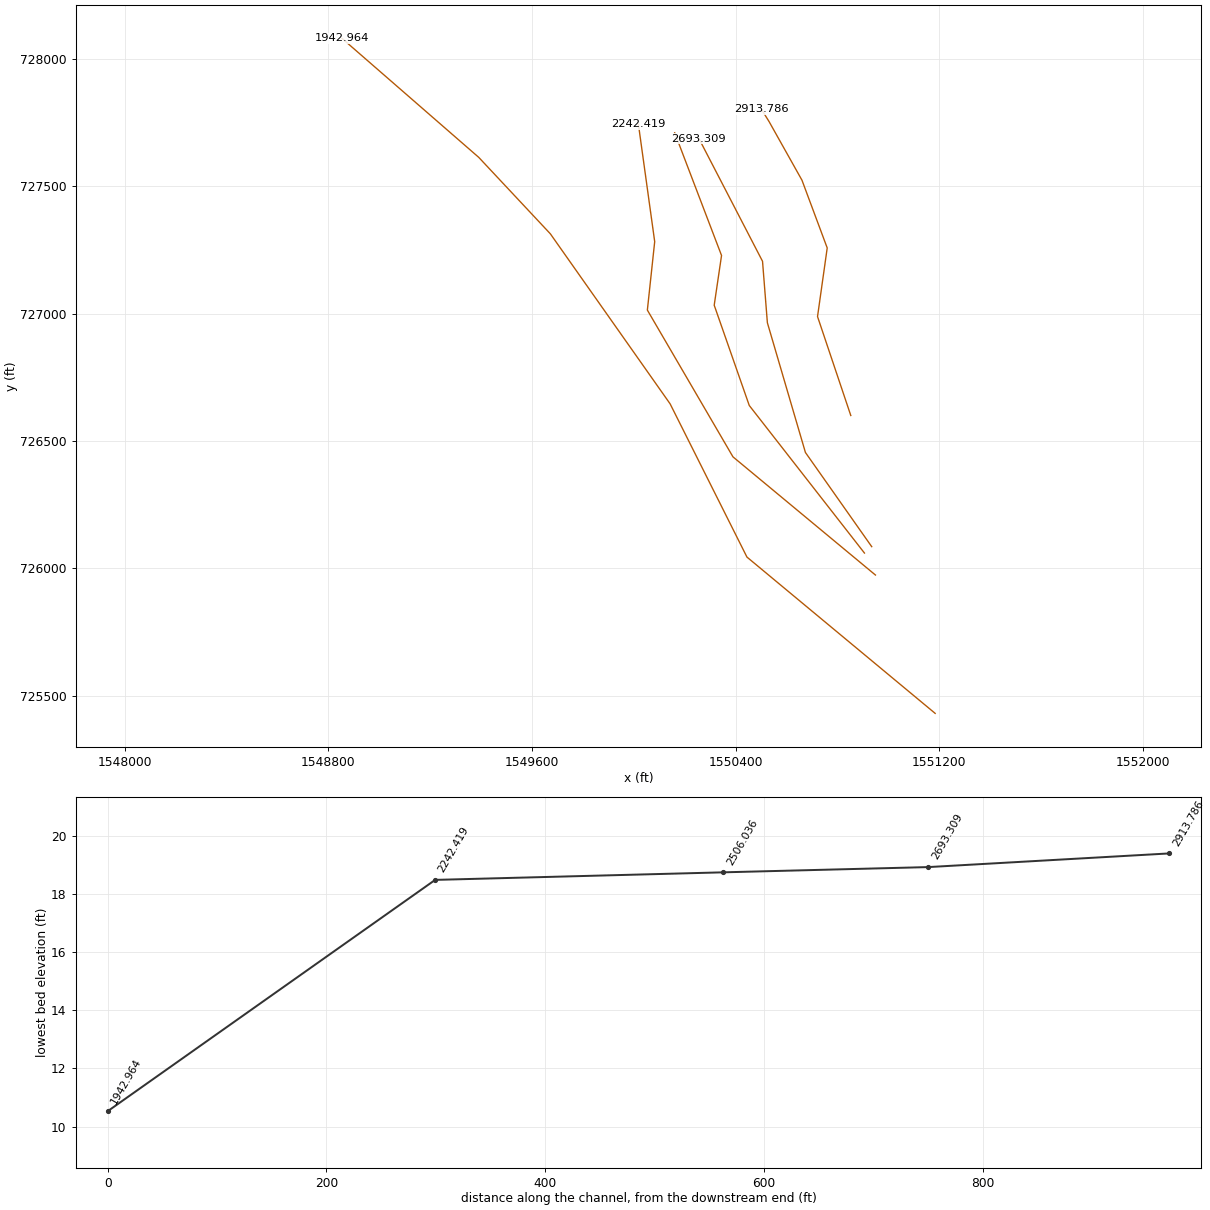
HEC-RAS study OctoraroCreek.prj: OctoraroCreek

--- OctoraroCreek.g01 (geometry) --- (continued)

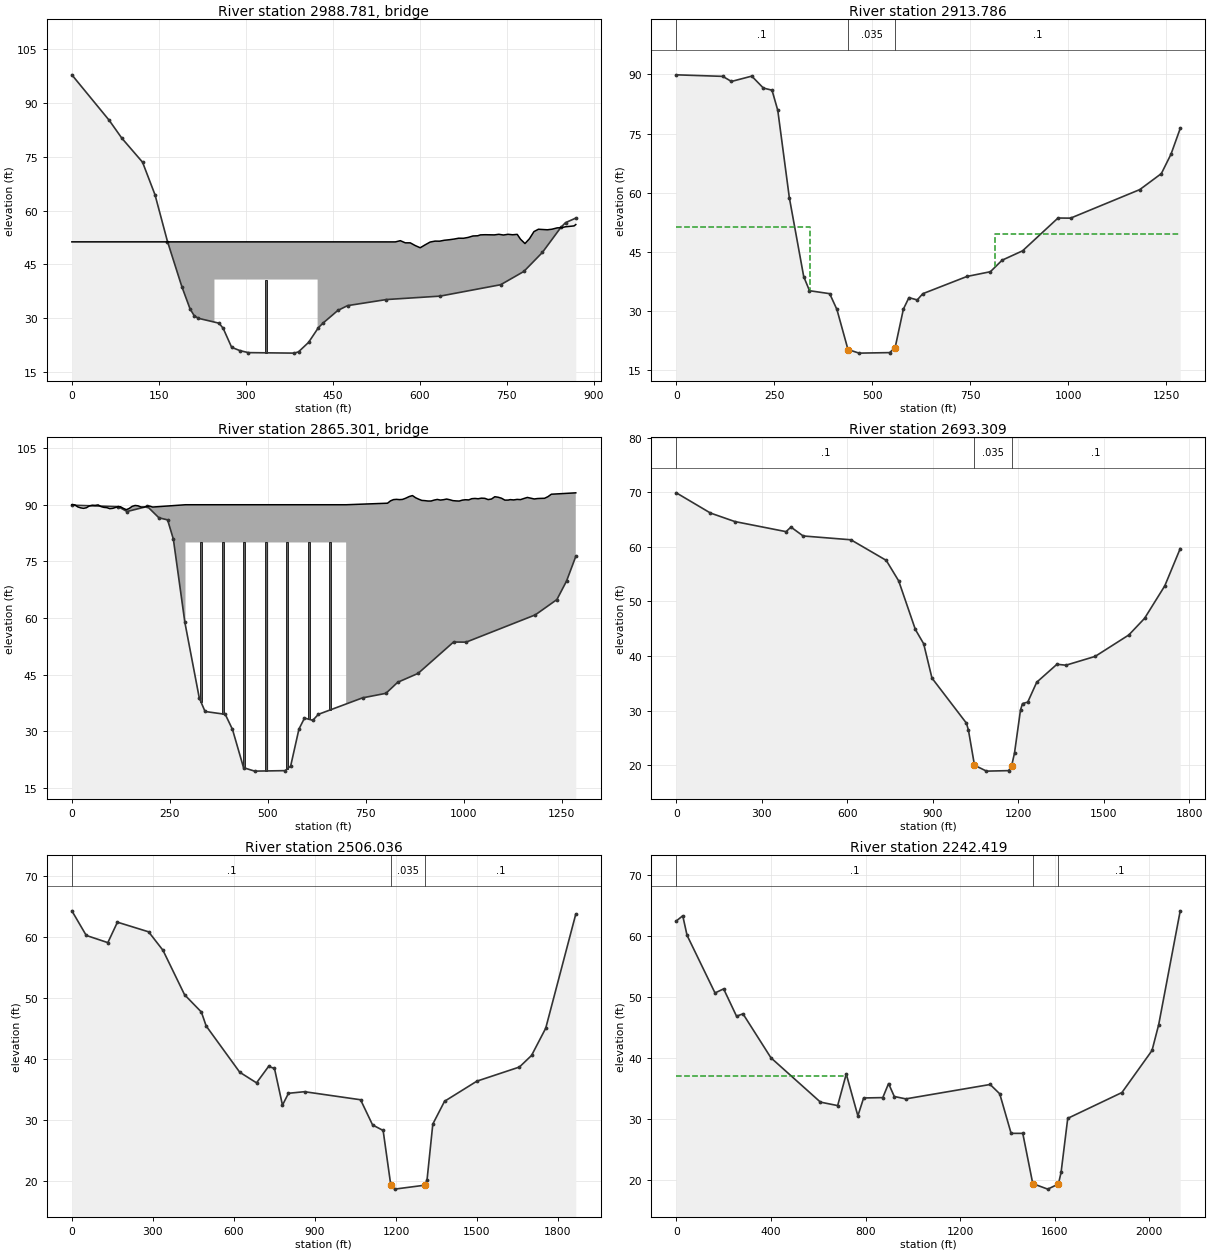
Type RM Length L Ch R = 3 ,2988.781,,,
BEGIN DESCRIPTION:
CE033007FS-1
Top of road obtained from DEM.
Opening from MDE2 bridge/culvert surveys.
END DESCRIPTION:
Bridge Culvert--1,0,-1,-1, 0
Deck Dist Width WeirC Skew NumUp NumDn MinLoCord MaxHiCord MaxSubmerge Is_Ogee
112,10,2.6,0, 46, 58, , , 0.95, 0, 0,0,,
       0     246     246     424     424   558.1  566.67  575.25  583.82  592.39
  600.96  609.53   618.1  626.67  634.42  642.64  650.86  659.08   667.3  675.52
  683.74  691.96  700.17  704.97  712.89  720.82  728.74  736.66  744.59  752.51
  760.43  768.36  774.02  781.75  789.48  797.21  804.93  812.66  820.39  828.12
  837.29  844.59  851.89  859.18  866.48   869.4
    51.3    51.3    51.3    51.3    51.3   51.29   51.63   51.03   51.03   50.27
   49.66   50.48   51.25   51.51   51.49   51.75   51.89   52.07   52.32    52.3
   52.54   52.94      53   53.25   53.29   53.27   53.24   53.41   53.21   53.41
   53.28   53.39   52.04   50.83   52.18   54.16   54.82   54.74   54.67   54.82
    55.2   55.25   55.51   55.62   55.75   56.12
                    40.8    40.8
                                                                                
                                                                                
                                                                                
                                                
       0     406     406     584     584   698.1  706.67  715.25  723.82  732.39
  740.96  749.53   758.1  766.67  774.42  782.64  790.86  799.08   807.3  815.52
  823.74  831.96  840.17  844.97  852.89  860.82  868.74  876.66  884.59  892.51
  900.43  908.36  914.02  921.75  929.48  937.21  944.93  952.66  960.39  968.12
  977.29  984.59  991.89  999.18 1006.48 1013.77 1021.07 1026.43 1033.63 1040.84
 1048.04 1055.25 1062.45 1069.65 1076.86 1084.06 1091.26 1102.64
    51.3    51.3    51.3    51.3    51.3   51.29   51.63   51.03   51.03   50.27
   49.66   50.48   51.25   51.51   51.49   51.75   51.89   52.07   52.32    52.3
   52.54   52.94      53   53.25   53.29   53.27   53.24   53.41   53.21   53.41
   53.28   53.39   52.04   50.83   52.18   54.16   54.82   54.74   54.67   54.82
    55.2   55.25   55.51   55.62   55.75   56.12    56.5   56.48   56.52   56.68
   57.02   57.18   57.21   57.19   57.19   57.43   57.68   57.94
                    40.8    40.8
                                                                                
                                                                                
                                                                                
                                                                                
                                                                
Pier Skew, UpSta & Num, DnSta & Num=  ,335, 2 ,495, 2 , 0 , 0 , 0 ,,
       5       5
       0      46
       5       5
       0      46
BR Coef=-1 , 1 , 0 ,, 0 ,,,0.8,-1,0.5,0,
WSPro=,,,, 1 ,,,, 0 ,,,, 0 ,,,,-1 ,-1 ,-1 , 0 , 0 , 0 , 0 , 0
BC Design=,, 0 ,, 0 ,,,,,,
BC Use User HTab Curves=0
BC User HTab FreeFlow(D)= 0

Type RM Length L Ch R = 1 ,2913.786,204.18,220.48,266.23
XS GIS Cut Line= 6
1550852.37911199726600.243489355 1550721.7617183726988.788900822
 1550759.7895671727258.2906117891550660.58648334727524.485553265
1550531.62247439 727754.306030721550501.86154924727802.254187867
#Sta/Elev= 30
       0   89.88  118.53   89.49  140.76    88.2  192.61   89.55  222.22   86.53
   244.3   85.99  259.02   80.88  288.45    58.8  325.24   38.76  339.96    35.2
  391.47   34.45  409.93   30.45  438.21    20.3  466.49   19.39  544.25   19.52
  558.39   20.72   579.6   30.54  593.74   33.45  614.94   32.86  629.08   34.44
  741.87   38.81  801.63   40.01  831.51   42.93   883.8    45.3  974.21   53.61
 1006.32   53.58 1182.91   60.81 1237.95   64.86 1262.67   69.79 1286.15    76.3
#Mann= 3 , 0 , 0
       0      .1       0  438.21    .035       0  558.39      .1       0
#XS Ineff= 2 , 0
       0  342.51    51.3  812.77       0   49.66
Permanent Ineff=
       F       F
Bank Sta=438.21,558.39
XS Rating Curve= 0 ,0
Exp/Cntr=0.5,0.3

Type RM Length L Ch R = 3 ,2865.301,,,
BEGIN DESCRIPTION:
Top of road taken from approach elevation on DEM.  No bridge inspection notes were available.  Pictures taken with upstream RR bridge illustrate this bridge's geometry.
Assumed bridge opening 410' from DEM.  Pictures show 3 spans on left bank and 2 in the middle.  Total width from DEM indicates that there are likely 3 spans on the right bank.  Simple 5 ft wide piers assumed since this bridge is so high.
END DESCRIPTION:
Bridge Culvert--1,0,-1,-1, 0
Deck Dist Width WeirC Skew NumUp NumDn MinLoCord MaxHiCord MaxSubmerge Is_Ogee
27,30,2.6,0, 86, 80, , , 0.95, 0, 0,0,,
       0    7.45    14.9   22.35   29.79   37.24   44.69   52.14   59.59   67.04
   74.48   81.93   89.38   96.83  104.28  109.28  116.73  124.17  131.62  139.07
  146.52  153.97  161.42  168.87  176.31  183.76  191.21  198.66  206.11     290
     290     700     700  805.62  813.23  820.84  828.44  836.05  843.65  851.26
  861.43  869.35  877.26  885.18  893.09  901.01  908.92  916.84  924.75  932.67
  940.58   948.5  956.44  964.49  972.54  980.58  988.63  996.67 1004.72 1012.76
 1020.81 1028.86 1036.93 1045.45 1053.97 1062.49 1071.02 1079.54 1088.06 1096.58
  1105.1 1113.63 1118.77 1127.52 1136.27 1145.02 1153.77 1162.52 1171.27 1180.02
 1188.77 1197.52 1206.27 1215.02 1223.77 1286.15
   89.98   89.98   89.44   89.18   89.05   89.21   89.69   89.88   89.83   89.96
   89.51    89.3   89.23   88.96   89.05   89.21   89.46   89.47   89.03   88.69
   89.03   89.58   89.81   89.72   89.41   89.38   89.58   89.65   89.39      90
      90      90      90   90.41   91.03   91.36   91.43   91.36   91.41    91.7
   92.19   92.43   91.86   91.48   91.15   91.09   90.99   90.99   91.24   91.41
   91.24   91.34   91.51   91.33   91.09   91.02   90.98   91.23   91.33   91.28
   91.61   91.67   91.59   91.75    91.7   91.37   91.52   92.13   91.99   91.73
   91.23   91.24   91.36   91.28   91.42   91.36   91.66   91.94   91.74   91.53
   91.65   91.69   91.71   92.14   92.79   93.16
                                                                                
                                                                                
                                                                                
      80      80
                                                                                
                                                                                
                                                                                
                                                                                
                                                
       0     595  602.45   609.9  617.35  624.79  632.24  639.69  647.14  654.59
  662.04  669.48  676.93  684.38  691.83  699.28  704.28  711.73  719.17  726.62
  734.07  741.52  748.97  756.42  763.87  771.31  778.76  786.21  793.66  801.11
     910     910    1320    1320 1400.62 1408.23 1415.84 1423.44 1431.05 1438.65
 1446.26 1456.43 1464.35 1472.26 1480.18 1488.09 1496.01 1503.92 1511.84 1519.75
 1527.67 1535.58  1543.5 1551.44 1559.49 1567.54 1575.58 1583.63 1591.67 1599.72
 1607.76 1615.81 1623.86 1631.93 1640.45 1648.97 1657.49 1666.02 1674.54 1683.06
 1691.58  1700.1 1708.63 1713.77 1722.52 1731.27 1740.02 1748.77 1757.52 1768.46
      90   89.98   89.98   89.44   89.18   89.05   89.21   89.69   89.88   89.83
   89.96   89.51    89.3   89.23   88.96   89.05   89.21   89.46   89.47   89.03
   88.69   89.03   89.58   89.81   89.72   89.41   89.38   89.58   89.65   89.39
      90      90      90      90   90.41   91.03   91.36   91.43   91.36   91.41
    91.7   92.19   92.43   91.86   91.48   91.15   91.09   90.99   90.99   91.24
   91.41   91.24   91.34   91.51   91.33   91.09   91.02   90.98   91.23   91.33
   91.28   91.61   91.67   91.59   91.75    91.7   91.37   91.52   92.13   91.99
   91.73   91.23   91.24   91.36   91.28   91.42   91.36   91.66   91.94   91.74
                                                                                
                                                                                
                                                                                
              80      80
                                                                                
                                                                                
                                                                                
                                                                                
Pier Skew, UpSta & Num, DnSta & Num=  ,330, 2 ,950, 2 , 0 , 0 , 0 ,,
       5       5
       0      90
       5       5
       0      90
Pier Skew, UpSta & Num, DnSta & Num=  ,385, 2 ,1005, 2 , 0 , 0 , 0 ,,
       5       5
       0      90
       5       5
       0      90
Pier Skew, UpSta & Num, DnSta & Num=  ,440, 2 ,1060, 2 , 0 , 0 , 0 ,,
       5       5
       0      90
       5       5
       0      90
Pier Skew, UpSta & Num, DnSta & Num=  ,495, 2 ,1115, 2 , 0 , 0 , 0 ,,
       5       5
       0      90
       5       5
       0      90
Pier Skew, UpSta & Num, DnSta & Num=  ,550, 2 ,1170, 2 , 0 , 0 , 0 ,,
       5       5
       0      90
       5       5
       0      90
Pier Skew, UpSta & Num, DnSta & Num=  ,605, 2 ,1225, 2 , 0 , 0 , 0 ,,
       5       5
       0      90
       5       5
       0      90
Pier Skew, UpSta & Num, DnSta & Num=  ,660, 2 ,1280, 2 , 0 , 0 , 0 ,,
       5       5
       0      90
       5       5
       0      90
BR Coef=-1 , 1 , 0 ,, 0 ,,,0.8,-1,0.5,0,
WSPro=,,,, 1 ,,,, 0 ,,,, 0 ,,,,-1 ,-1 ,-1 , 0 , 0 , 0 , 0 , 0
BC Design=,, 0 ,, 0 ,,,,,,
BC Use User HTab Curves=0
BC User HTab FreeFlow(D)= 0

Type RM Length L Ch R = 1 ,2693.309,177.48,187.27,170.7
XS GIS Cut Line= 5
1550934.51998852 726085.110849531550674.20886758 726454.97152251
1550524.76977009726964.4902816411550505.72933523727205.926748022
1550255.87133193727688.047120526
#Sta/Elev= 30
       0   69.89  119.84   66.19  205.44   64.63   385.2   62.78  402.32   63.62
  445.12   61.99  612.77   61.29  736.78   57.52  780.55   53.75  838.91   44.87
  868.09   42.25  897.27   35.96 1018.37   27.69 1025.39   26.38 1046.46      20
 1088.59   18.92 1165.83   19.01 1176.38   19.79 1186.89   22.23 1207.96   30.12
 1214.98   31.29 1233.33   31.56 1264.87    35.2 1335.83   38.49 1367.36   38.32
 1469.86   39.93 1588.12   43.86 1643.31    46.9 1714.27   52.85 1768.46   59.68
#Mann= 3 , 0 , 0
       0      .1       0 1046.46    .035       0 1176.38      .1       0
Bank Sta=1046.46,1176.38
XS Rating Curve= 0 ,0
Exp/Cntr=0.5,0.3

Type RM Length L Ch R = 1 ,2506.036,222.38,263.62,265.48
XS GIS Cut Line= 5
1550906.04378749726059.946571931 1550453.5985228726639.585508198
1550315.92325367727033.400812864 1550344.7390077727228.707589984
1550160.79053158727710.711032331
#Sta/Elev= 30
       0   64.33   53.28    60.3   133.2   59.12  168.72   62.47  284.16   60.89
  337.44   57.86  417.36   50.58  479.52   47.75  497.28   45.47   621.6   37.89
  683.76   36.15  728.16   38.83  750.15   38.52  779.81    32.5  802.05   34.44
  861.38    34.7 1069.01   33.38  1113.5   29.25  1152.5   28.35  1180.8   19.42
 1194.95   18.74 1307.76   19.39 1315.24   20.31 1336.47    29.4 1379.89   33.13
 1499.77   36.43 1657.11   38.74 1702.07   40.64 1754.51    45.1 1865.83    63.8
#Mann= 3 , 0 , 0
       0      .1       0  1180.8    .035       0 1307.76      .1       0
#XS Ineff= 2 , 0
       0   727.6   38.68               0
Permanent Ineff=
       T       F
Bank Sta=1180.8,1307.76
XS Rating Curve= 0 ,0
Exp/Cntr=0.3,0.1

Type RM Length L Ch R = 1 ,2242.419,115.25,299.45,391.15
XS GIS Cut Line= 5
1550949.18397561725973.6661956311550389.56351389726437.875230208
1550053.37971723727014.1903101951550082.19547126727283.137347505
 1550018.2091582727744.213759407
#Sta/Elev= 30
       0   62.43   27.28   63.28   45.47   60.08  163.71   50.63  200.09    51.3
  254.66   46.82  281.94   47.21  400.17      40  609.35   32.74  682.11   32.17
  718.49   37.35  767.61   30.49  791.93   33.42  872.97   33.48  897.28   35.78
  921.59   33.66  970.21   33.27 1326.78   35.63  1367.3    34.1 1415.42   27.62
  1464.7   27.62 1506.94   19.38  1570.3   18.48 1615.39   19.32 1626.62   21.22
 1654.78   30.08 1883.86   34.31 2011.07    41.2 2039.34   45.45 2130.28   64.09
#Mann= 3 , 0 , 0
       0      .1       0 1506.94    .035       0 1615.39      .1       0
#XS Ineff= 2 , 0
       0  721.33   37.08               0
Permanent Ineff=
       T       F
Bank Sta=1506.94,1615.39
XS Rating Curve= 0 ,0
Exp/Cntr=0.5,0.3

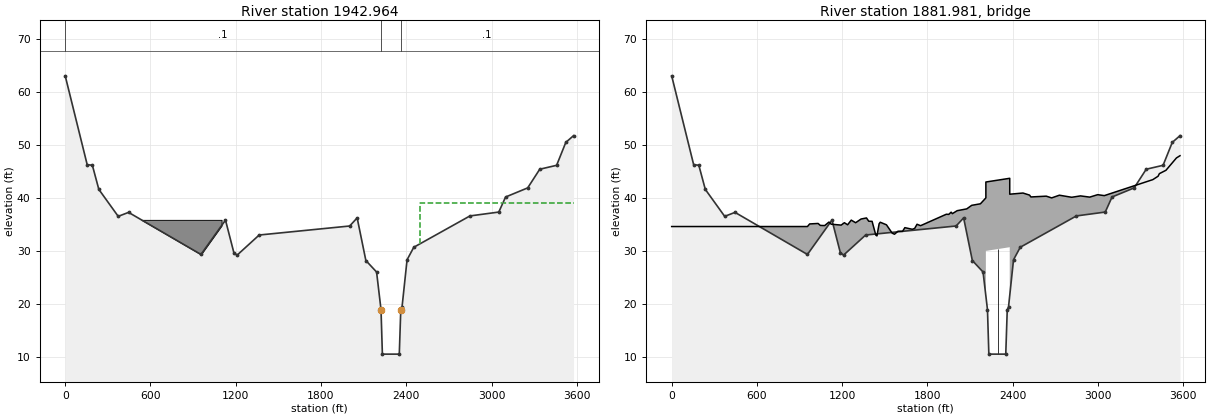
Type RM Length L Ch R = 1 ,1942.964,100.4,121.1,116.37
BEGIN DESCRIPTION:
Modified below water portion - Bridge Inspection report indicated a flow depth of 8'.  Assumed this was an "average condition" and was applied to xsections upstream and downstream of  the bridge.
Blocked obstruction used instead of permanent ineffective flow area since Check-RAS indicates there is a bug with permanent ineffective flow areas at bridges.
END DESCRIPTION:
XS GIS Cut Line= 6
1551183.80406703725430.2575176511550444.50910304726044.174973115
1550142.73965482726646.0496260521549672.28954202727313.877753198
1549391.07102349727614.1491278411548853.75297701 728081.62072067
#Sta/Elev= 30
       0   63.03  154.68   46.27  191.08   46.16  236.57   41.61  373.05   36.52
  445.84   37.27  955.38   29.33 1127.97   35.81 1186.85   29.67 1209.47    29.2
 1365.08      33 2001.87    34.7  2054.5   36.23 2115.75   28.19 2191.19   26.02
 2222.34   18.92    2232   10.53    2351   10.53 2361.48   18.91 2370.32   19.41
 2405.71   28.33 2453.06   30.69 2848.26    36.6 3051.14   37.33 3098.99   40.17
 3254.58   41.89 3339.39   45.41 3458.11   46.15 3522.73   50.47 3577.14   51.74
#Mann= 3 , 0 , 0
       0      .1       0 2222.34    .035       0 2361.48      .1       0
#XS Ineff= 2 , 0
       0                    2500       0      39
Permanent Ineff=
       F       F
#Block Obstruct= 2 , 0
       0 1100.36   35.86               0
Bank Sta=2222.34,2361.48
XS Rating Curve= 0 ,0
Exp/Cntr=0.5,0.3

Type RM Length L Ch R = 3 ,1881.981,,,
BEGIN DESCRIPTION:
Susquehanna River Rd.  CE033007FS-2
Top of road obtained from DEM.
Opening from MDE2 bridge/culvert surveys.
END DESCRIPTION:
Bridge Culvert--1,0,-1,-1, 0
Deck Dist Width WeirC Skew NumUp NumDn MinLoCord MaxHiCord MaxSubmerge Is_Ogee
46,30,2.6,0, 60, 60, , , 0.95, 0, 2,2,,
       0  955.38  970.98 1030.46 1045.85 1076.65 1106.65 1123.06  1192.7 1215.31
 1237.93 1263.74 1294.47 1332.87 1370.91 1386.68 1410.34 1436.56 1444.33 1459.85
 1467.62 1511.25 1551.77 1567.97 1592.29  1624.7 1640.91 1693.52 1710.08 1726.64
 1751.47 1932.76  1949.7 1966.64 1975.12 2009.01 2076.36 2111.36 2172.61    2211
    2211    2379    2379 2472.27 2518.37 2527.59 2636.08 2673.93 2728.21 2815.07
 2876.81    2942 2997.87 3044.43 3385.97  3422.9 3432.13 3478.28 3552.13 3577.14
    34.6    34.6   35.09   35.18   34.81   34.78   35.44   35.04   34.87   35.32
   34.93   35.81   35.32   36.02   36.22    35.6   35.58   32.98   32.83   35.12
   35.41   34.93   33.35   33.15   33.71   33.69   34.39   34.08   34.25   35.03
   34.76   36.92   36.89   37.31   37.03   37.59   37.93    38.6   38.89      40
      43    43.7    40.7   40.92   40.53   40.18   40.33      40   40.51   40.12
   40.38   40.15   40.61   40.43   43.45   44.09   44.58   45.21   47.54   47.96
                                                                                
                                                                                
                                                                                
                                                                                
      30    30.7
                                                                                
       0   63.69  100.09  118.29  154.68  309.36  336.66  400.35  955.38  970.98
 1030.46 1076.65 1106.65 1131.26  1192.7 1215.31 1237.93 1263.74 1294.47 1370.91
 1386.68 1410.34 1436.56 1444.33 1459.85 1467.62 1511.25 1551.77 1567.97 1592.29
  1624.7 1640.91 1693.52 1710.08 1726.64 1751.47 1966.64 1975.12 2009.01 2076.36
 2111.36 2172.61 2193.18 2220.24    2286    2286    2454    2454 2472.27 2527.59
 2636.08 2673.93 2728.21 2815.07 3044.43 3385.97 3432.13 3478.28 3552.13 3579.38
   52.32    45.3   42.36   41.43   39.99   37.16   35.97   34.74    34.6   35.09
   35.18   34.78   35.44      35   34.87   35.32   34.93   35.81   35.32   36.22
    35.6   35.58   32.98   32.83   35.12   35.41   34.93   33.35   33.15   33.71
   33.69   34.39   34.08   34.25   35.03   34.76   37.31   37.03   37.59   37.93
    38.6   38.89    39.4   38.97      40      43    43.7    40.7   40.92   40.18
   40.33      40   40.51   40.12   40.43   43.45   44.58   45.21   47.54   47.96
                                                                                
                                                                                
                                                                                
                                                                                
                                              30    30.7
                                                                                
Pier Skew, UpSta & Num, DnSta & Num=  ,2295, 2 ,2370, 2 , 0 , 0 , 0 ,,
       2       2
      10      35
       2       2
      10      35
BR Coef=-1 , 1 , 0 ,, 0 ,,,0.8,0,0.5,0,
WSPro=,,,, 1 ,,,, 0 ,,,, 0 ,,,,-1 ,-1 ,-1 , 0 , 0 , 0 , 0 , 0
BC Design=,, 0 ,, 0 ,,,,,,
BC Use User HTab Curves=0
BC User HTab FreeFlow(D)= 0