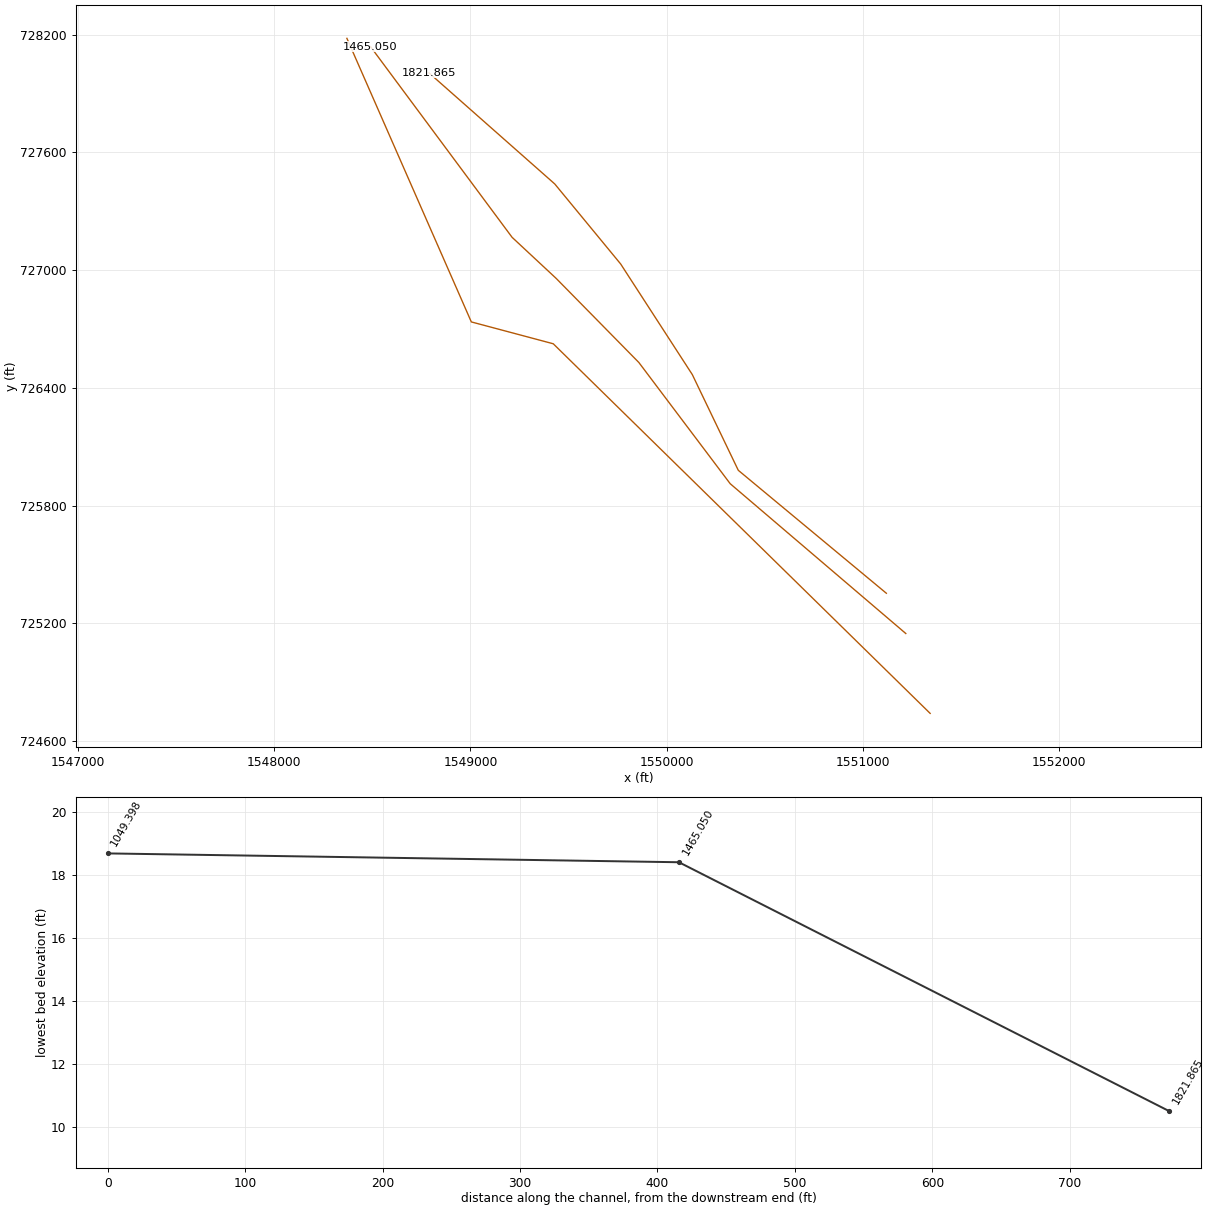
HEC-RAS study OctoraroCreek.prj: OctoraroCreek

--- OctoraroCreek.g01 (geometry) --- (continued)

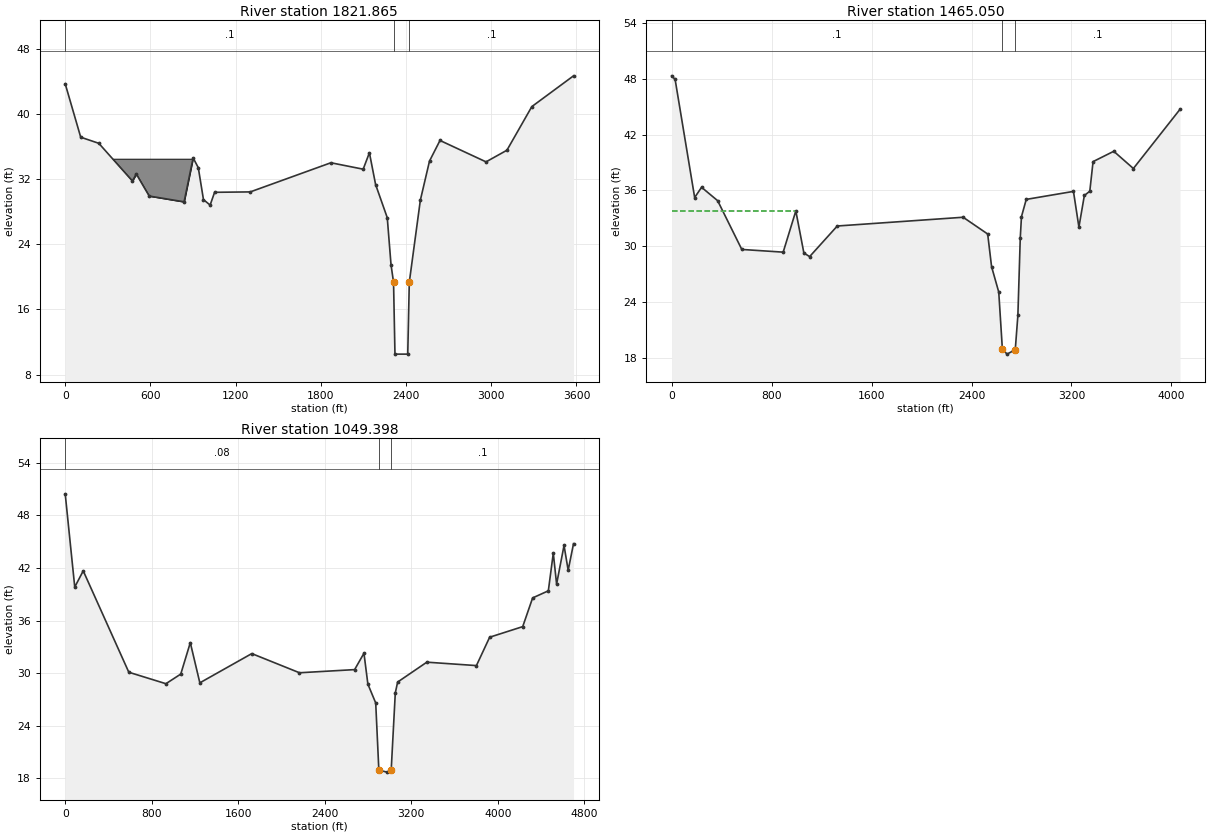
Type RM Length L Ch R = 1 ,1821.865,237.79,356.82,371.04
BEGIN DESCRIPTION:
Modified below water portion - Bridge Inspection report indicated a flow depth of 8'.  Assumed this was an "average condition" and was applied to xsections upstream and downstream of  the bridge.
Blocked obstruction used instead of permanent ineffective flow area since Check-RAS indicates there is a bug with permanent ineffective flow areas at bridges.
END DESCRIPTION:
XS GIS Cut Line= 6
1551119.91847965725353.3248736111550365.21771364725980.035451159
1550130.85841113726467.9539868681549765.66721813727031.683224708
1549429.63472496727439.6650874611548788.56434672728005.789048687
#Sta/Elev= 30
       0   43.72  109.19   37.16  236.57   36.41  473.14   31.78  500.44   32.64
  591.43   29.93   837.1   29.22  900.79   34.62  937.18   33.41  973.58   29.49
  1020.5   28.82 1051.81   30.39 1303.15   30.44  1870.9   34.02 2098.23   33.23
 2141.98   35.25 2185.73   31.34 2267.78   27.27 2294.32   21.47 2312.01   19.34
    2322   10.51    2412   10.51 2422.86   19.33 2500.71   29.42 2565.24   34.23
    2639   36.76 2963.23   34.13 3110.39   35.56 3285.76   40.92 3579.38    44.7
#Mann= 3 , 0 , 0
       0      .1       0 2312.01    .035       0 2422.86      .1       0
#Block Obstruct= 2 , 0
       0  899.64   34.52               0
Bank Sta=2312.01,2422.86
XS Rating Curve= 0 ,0
Exp/Cntr=0.5,0.3

Type RM Length L Ch R = 1 ,1465.050,263.69,415.65,466.19
XS GIS Cut Line= 6
1551219.05619013 725148.107822941550324.04784986725911.631815091
1549858.49039984726529.4450933931549437.26091078726957.865666837
1549212.28786962727167.5492780511548490.95041999728139.199134558
#Sta/Elev= 30
       0   48.31    27.6   47.92  184.02   35.23  239.23   36.33  368.04   34.89
  561.27   29.65  892.51   29.36  993.72   33.79 1058.13   29.27 1104.13   28.88
 1325.44   32.17 2332.88   33.11 2529.21   31.31 2560.41    27.8 2617.82   25.07
 2646.53      19 2683.62    18.4 2749.96   18.87 2770.93   22.56 2790.07   30.89
 2799.64   33.17 2837.91   35.03 3215.82   35.89 3259.41   32.05    3303   35.45
 3346.59   35.91 3372.74   39.09 3538.39    40.2 3695.31   38.35  4068.5   44.71
#Mann= 3 , 0 , 0
       0      .1       0 2646.53    .035       0 2749.96      .1       0
#XS Ineff= 2 , 0
       0  990.14   33.76               0
Permanent Ineff=
       T       F
Bank Sta=2646.53,2749.96
XS Rating Curve= 0 ,0
Exp/Cntr=0.3,0.1

Type RM Length L Ch R = 1 ,1049.398,568.58,1049.4,1086.44
XS GIS Cut Line= 4
1551343.14709084724741.0646394491549422.14006469726624.950756952
1549004.52984156726736.3134831041548370.31674889 728181.73058933
#Sta/Elev= 30
       0   50.47   88.24   39.82  166.67   41.67  588.26   30.09  931.41   28.78
 1068.67   29.88 1156.91   33.47 1245.15   28.88 1725.56   32.22 2166.75   30.03
 2676.57   30.39 2763.03   32.26 2799.26   28.73  2871.7   26.58 2900.68   18.91
 2975.65   18.68 3014.98   18.93 3052.82   27.73 3074.55   28.97 3344.48   31.24
 3803.13   30.85 3925.44   34.09 4231.21    35.3 4322.94   38.58 4468.17   39.39
 4514.04   43.69 4544.62   40.16 4613.41   44.57 4651.63   41.74 4701.23   44.78
#Mann= 3 , 0 , 0
       0     .08       0 2900.68    .035       0 3014.98      .1       0
#XS Ineff= 2 , 0
       0 1155.91   33.37               0
Permanent Ineff=
       T       F
Bank Sta=2900.68,3014.98
XS Rating Curve= 0 ,0
Exp/Cntr=0.3,0.1

Chan Stop Cuts=-1
Use User Specified Reach Order=0
User Specified Reach Order=OctoraroCreek   ,Reach1