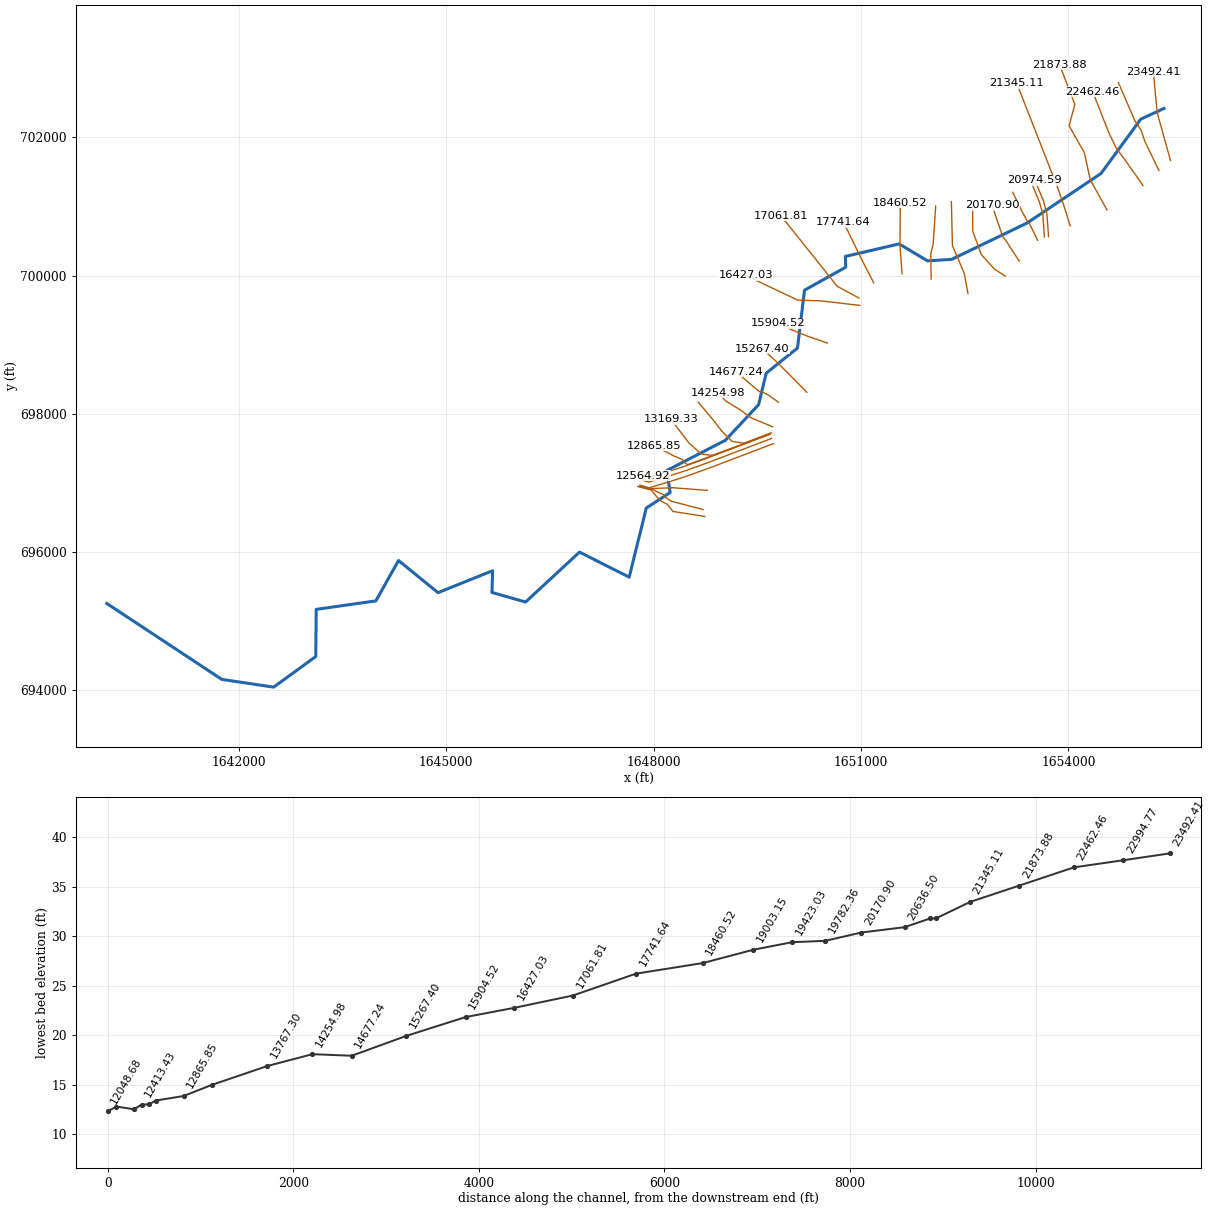
--- PerchCreek.prj (project) ---

Proj Title=PerchCreek
Current Plan=p01
Default Exp/Contr=0.3,0.1
English Units
Geom File=g01
Flow File=f01
Plan File=p01
Y Axis Title=Elevation
X Axis Title(PF)=Main Channel Distance
X Axis Title(XS)=Station
BEGIN DESCRIPTION:
Perch Creek - Georeferenced HEC-RAS model.  This was formerly an approximate method stream.  Projection:  MD Stateplane.  Horizontal datum:  NAD83.  Vertrial datum: NAVD88.  Units:Feet.  Created by: Aaron W. Buesing, USACE- St Paul District as part of FEMA Map Modernization study for Cecil County, MD.
END DESCRIPTION:
DSS Export Rating Curves= 0
DSS Export Rating Curve Sorted= 0
DSS Export Volume Flow Curves= 0
DXF OffsetX= 0
DXF OffsetY= 0
DXF ScaleX= 1
DXF ScaleY= 10

--- PerchCreek.p01 (plan) ---

Plan Title=PerchCreek_100yr
Program Version=4.00
Short Identifier=PerchCreek100
Geom File=g01
Flow File=f01
Subcritical Flow
K Sum by GR= 0
Std Step Tol= 0.01
Critical Tol= 0.01
Num of Std Step Trials= 20
Max Error Tol= 0.3
Flow Tol Ratio= 0.001
Split Flow NTrial= 30
Split Flow Tol= 0.02
Split Flow Ratio= 0.02
Log Output Level= 0
Friction Slope Method= 1
Unsteady Friction Slope Method= 2
Unsteady Bridges Friction Slope Method= 1
Secant Critical Depth
Global Vel Dist= 0 , 0 , 0
Global Log Level= 0
CheckData=True
Encroach Param=-1 ,0,0, 0
Computation Interval=1HOUR
Output Interval=1HOUR
Run HTab= 0
Run UNet= 0
Run PostProcess= 0
Run WQNet= 0
UNET Theta= 1
UNET Theta Warmup= 1
UNET ZTol= 0.02
UNET ZSATol= 0.05
UNET MxIter= 20
UNET MaxInSteps= 0
UNET DtIC= 0
UNET DtMin= 0
UNET MaxCRTS= 20
UNET WFStab= 2
UNET SFStab= 1
UNET WFX= 1
UNET SFX= 1
UNET DSS MLevel= 4
UNET DZMax Abort= 100
UNET Convert EG Bridges= 0
UNET Use Existing IB Tables=-1
UNET Froude Reduction=False
UNET Froude Limit= 1
UNET Froude Power= 10
UNET Time Slicing=0,0, 5
Instantaneous Interval=1HOUR
Write IC File= 0
Echo Input=False
Echo Output=False
Write Detailed= 0
Detailed Automatic Start=False, 10
WQ ULTIMATE=-1
WQ Max Comp Step=1HOUR
WQ Output Interval=15MIN
WQ Output Selected Increments= 0
WQ Output face flow=0
WQ Output face velocity=0
WQ Output face area=0
WQ Output face dispersion=0
WQ Output cell volume=0
WQ Output cell surface area=0
WQ Output cell continuity=0
WQ Output face conc=0
WQ Output face dconc_dx=0
WQ Output face courant=0
WQ Output face peclet=0
WQ Output face adv mass=0
WQ Output face disp mass=0
WQ Output cell mass=0
WQ Output cell source sink temp=0
WQ Output cell source sink nsm=0
WQ Output MaxMinRange=-1
WQ Create Restart=0
WQ Fixed Restart=0
Sorting and Armoring Iterations= 10
XS Update Threshold= 0.02
Hydraulics Update Threshold= 0.02
Energy Slope Method= 1
Volume Change Method= 0
XS Weighting Method= 0
Number of US Weighted Cross Sections= 1
Number of DS Weighted Cross Sections= 1
Upstream XS Weight=0.25
Main XS Weight=0.5
Downstream XS Weight=0.25
Number of DS XS's Weighted with US Boundary= 1
Upstream Boundary Weight= 1
Weight of XSs Associated with US Boundary= 0
Number of US XS's Weighted with DS Boundary= 1
Downstream Boundary Weight= 0.5
Weight of XSs Associated with DS Boundary= 0.5
Sediment Output Level= 4
Mass or Volume Output= 0
Output Increment Type= 1
Profile and TS Output Increment= 10
XS Output Flag= 0
XS Output Increment= 10
Disregard all LS=0
Disregard all Conn=0
Disregard all Breaches=0
Disregard all Pumps=0

--- PerchCreek.f01 (steady flow) ---

Flow Title=PerchCreek_100yr
Program Version=4.00
Number of Profiles= 2
Profile Names=100CUR,100ULT
River Rch & RM=PerchCreek,Reach1          ,23492.41
     670     670
River Rch & RM=PerchCreek,Reach1          ,21345.11
    1200    1200
River Rch & RM=PerchCreek,Reach1          ,19423.03
    1260    1260
River Rch & RM=PerchCreek,Reach1          ,15267.40
    1650    1650
River Rch & RM=PerchCreek,Reach1          ,11001.41
    1940    1940
River Rch & RM=PerchCreek,Reach1          ,6234.726
    2810    2810
River Rch & RM=PerchCreek,Reach1          ,5320.312
    2840    2840
River Rch & RM=PerchCreek,Reach1          ,2703.339
    2900    2900
River Rch & RM=PerchCreek,Reach1          ,2233.010
    3130    3130
River Rch & RM=PerchCreek,Reach1          ,469.1109
    3160    3160
Boundary for River Rch & Prof#=PerchCreek,Reach1          , 1
Up Type= 0
Dn Type= 3
Dn Slope=0.00016
Boundary for River Rch & Prof#=PerchCreek,Reach1          , 2
Up Type= 0
Dn Type= 3
Dn Slope=0.00016
DSS Import GetInterval= 0
DSS Import GetPeak= 0
DSS Import FillOption= 0

--- PerchCreek.g01 (geometry) ---

Geom Title=PerchCreek
Program Version=4.00

River Reach=PerchCreek      ,Reach1
Reach XY= 30
1655383.85431014702417.7060584281655048.08325335702263.843909457
1654472.62606494 701477.102947221653403.71685225700761.002991766
1652311.07607512 700234.656669931651962.02431555700212.902735889
 1651551.6660147700458.1289012431650774.45728095700277.373485848
1650779.40135686700121.1406869441650183.14580156699788.404377893
1650081.29783769698951.6689701231649628.42048396698587.290575221
1649518.66199864698132.3367095891649037.10900462697616.669591695
1648191.67202322697180.3054514831648239.13515201696861.906962603
1647894.03865321696636.9515085221647646.83485745695637.654884666
1646927.96621947695999.363478571 1646147.7910402695277.429513544
 1645661.2939702695415.6658761051645671.18212201 695730.60351187
1644881.11879091695413.1938381491644309.58361521695877.936974108
1643982.28578967695294.0416086321643119.05013502 695171.42852594
1643112.61329177694488.7983815371642503.36569764694046.322676301
 1641753.3741972694158.146601811 1640089.5113056695256.334670246

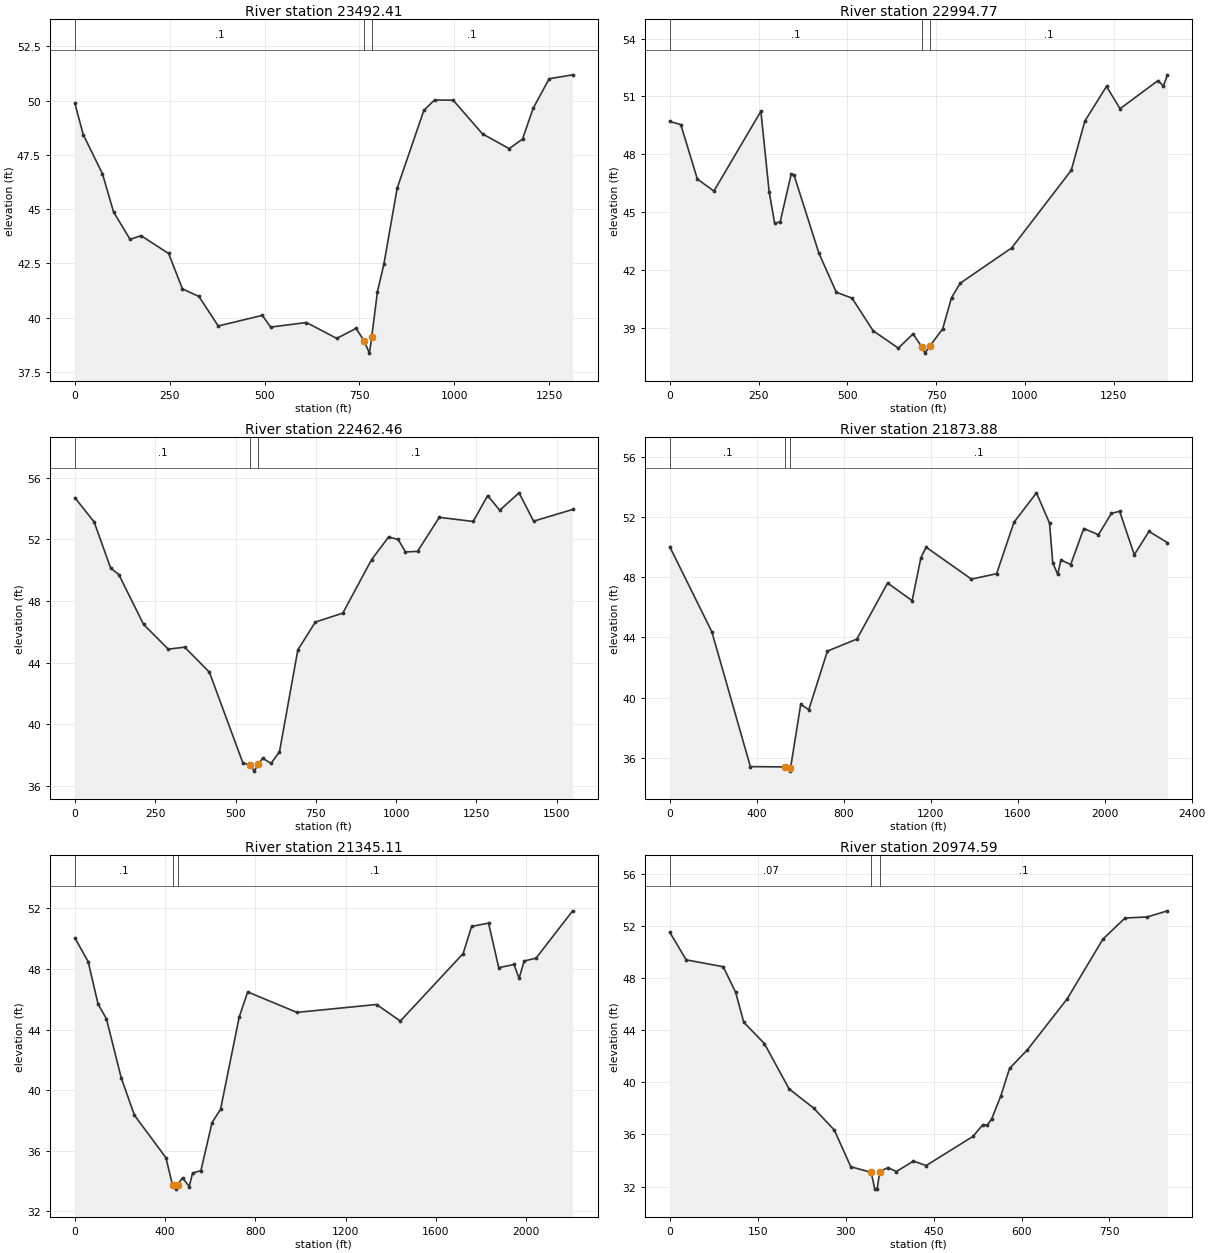
Type RM Length L Ch R = 1 ,23492.41,331.99,497.65,393.47
XS GIS Cut Line= 4
1655477.58271208701665.1609280261655286.57872854702352.105079502
 1655276.5258873702445.9315977691655229.61262815702948.573659822
#Sta/Elev= 30
       0   49.87    21.8   48.44   72.66   46.63  101.72   44.88  145.31   43.61
  174.37   43.78  247.03   42.96  283.36   41.33  326.95   40.98  377.81   39.62
  494.06   40.11  515.85   39.57  610.31   39.78  690.23   39.05  741.16   39.51
  762.28   38.94  776.37   38.37  782.46   39.11  797.49    41.2   814.4   42.46
  849.55   45.97  919.85   49.55  947.98   50.03  997.19   50.02 1074.52   48.47
 1144.83   47.79 1179.98   48.23  1208.1   49.65 1250.28   51.01 1312.19   51.19
#Mann= 3 , 0 , 0
       0      .1       0  762.28     .04       0  782.46      .1       0
Bank Sta=762.28,782.46
XS Rating Curve= 0 ,0
Exp/Cntr=0.3,0.1

Type RM Length L Ch R = 1 ,22994.77,465.24,532.3,485.14
XS GIS Cut Line= 5
 1655310.0353581701521.0702035871655108.97853327701936.587641552
1655052.01243286702100.7840484981654961.53686172702241.523825854
  1654723.619619702791.079147041
#Sta/Elev= 30
       0    49.7   31.11   49.54   77.76   46.71  124.42   46.09  256.62   50.23
  279.95   46.05   295.5   44.41  311.06    44.5  342.16   46.98  349.94   46.92
  419.93   42.87  469.01   40.84  513.47   40.53  572.74   38.84  643.72   37.94
  685.33   38.68   710.3   37.99  718.62   37.68  731.75   38.03  768.55   38.94
  793.51   40.56  817.97   41.31   962.9   43.14 1130.71   47.17 1168.85   49.72
 1229.87   51.52 1268.01   50.36  1374.8   51.82 1390.06   51.54 1401.56   52.12
#Mann= 3 , 0 , 0
       0      .1       0   710.3     .04       0  731.75      .1       0
Bank Sta=710.3,731.75
XS Rating Curve= 0 ,0
Exp/Cntr=0.3,0.1

Type RM Length L Ch R = 1 ,22462.46,611.45,588.58,551.77
XS GIS Cut Line= 5
1655078.97572313701303.5899390431654814.09519018701681.915663421
1654693.46109529701842.761123285 1654589.5817358702057.221736446
1654351.66449307702660.392210901
#Sta/Elev= 30
       0   54.71   59.82   53.14  111.09   50.15  136.72   49.72  213.63   46.49
  290.53   44.88  341.81   45.01  418.71   43.38  523.09   37.48  546.54   37.37
  558.09   36.96  571.49   37.42  584.34    37.8  610.59   37.46  636.84   38.22
     694   44.83  748.45   46.64  834.01   47.22  923.76    50.7  976.44   52.16
 1006.54      52 1029.11   51.19 1066.73   51.23 1134.46   53.44 1239.81   53.17
 1284.96   54.85 1322.58    53.9 1382.78   55.03 1427.93   53.19 1549.59   53.95
#Mann= 3 , 0 , 0
       0      .1       0  546.54     .04       0  571.49      .1       0
Bank Sta=546.54,571.49
XS Rating Curve= 0 ,0
Exp/Cntr=0.3,0.1

Type RM Length L Ch R = 1 ,21873.88,510.45,528.78,508.3
XS GIS Cut Line= 6
1654559.42321205700948.0582528111654316.27960692701387.293308109
1654231.03039818701779.0931287711654010.98499593702166.543900833
1654093.64156789702476.0901214931653872.47906061703052.453019321
#Sta/Elev= 30
       0   50.02   193.4   44.38  370.68   35.42  530.28    35.4  551.37   35.12
  555.22   35.31  602.15   39.55  639.32    39.2   724.9   43.09  860.41   43.89
 1001.78   47.61 1114.48   46.44 1154.73   49.29 1178.88   49.99 1386.98   47.87
  1502.9   48.23  1582.6   51.64 1686.14    53.6 1746.12   51.59 1761.12   48.95
 1783.61   48.19  1798.6   49.14 1843.59   48.84 1903.57   51.23 1971.05   50.82
 2031.03   52.24 2068.52   52.37    2136   49.49 2203.48   51.04 2288.48   50.29
#Mann= 3 , 0 , 0
       0      .1       0  530.28     .04       0  555.22      .1       0
Bank Sta=530.28,555.22
XS Rating Curve= 0 ,0
Exp/Cntr=0.3,0.1

Type RM Length L Ch R = 1 ,21345.11,327.48,370.52,334.39
XS GIS Cut Line= 4
1654026.39922982 700719.598127441653944.21329883700984.273070812
1653849.20993304701261.3662209211653252.55385071702784.377252892
#Sta/Elev= 30
       0   50.04   58.64   48.48  102.62   45.67  139.26   44.72  205.23   40.81
  263.87   38.34  402.94   35.55  432.54   33.75  447.34   33.47  454.74   33.76
  476.94   34.22  506.54   33.64  521.34   34.53  558.34   34.69  607.66   37.86
  645.25   38.73  727.95   44.82  765.54   46.48  983.56   45.13  1336.9   45.65
 1442.15   44.56 1720.32   49.01 1757.91    50.8 1833.09   51.02 1878.19   48.08
 1945.86   48.29 1968.41   47.38 1990.96   48.52 2043.59   48.71 2205.78   51.83
#Mann= 3 , 0 , 0
       0      .1       0  432.54     .04       0  454.74      .1       0
Bank Sta=432.54,454.74
XS Rating Curve= 0 ,0
Exp/Cntr=0.5,0.3

Type RM Length L Ch R = 1 ,20974.59,60.69,60.4,62.34
BEGIN DESCRIPTION:
Center of channel lowered 1 ft based on bridge survey info.
END DESCRIPTION:
XS GIS Cut Line= 5
1653713.58342491 700563.285470561653690.00222254700892.017206177
1653682.34895845 700926.355611161653638.85408255701082.212249696
1653515.59284168 701380.09358193
#Sta/Elev= 30
       0   51.51   28.07   49.39   91.23   48.86  112.29   46.91  126.32    44.6
  161.41   42.97  203.52   39.49  245.63   38.01  280.72   36.33  308.79   33.52
  343.74   33.08  349.69    31.8  353.67    31.8  358.26   33.14  372.02   33.45
  386.56   33.15  415.63   33.95  437.43   33.61  517.37   35.85  534.14   36.75
  541.72   36.71   549.3   37.21  564.45   38.92   579.6   41.06   609.9   42.48
  678.08   46.41  738.69   50.97  776.56    52.6  814.44   52.68  848.95   53.15
#Mann= 3 , 0 , 0
       0     .07       0  343.74     .04       0  358.26      .1       0
Bank Sta=343.74,358.26
XS Rating Curve= 0 ,0
Exp/Cntr=0.5,0.3

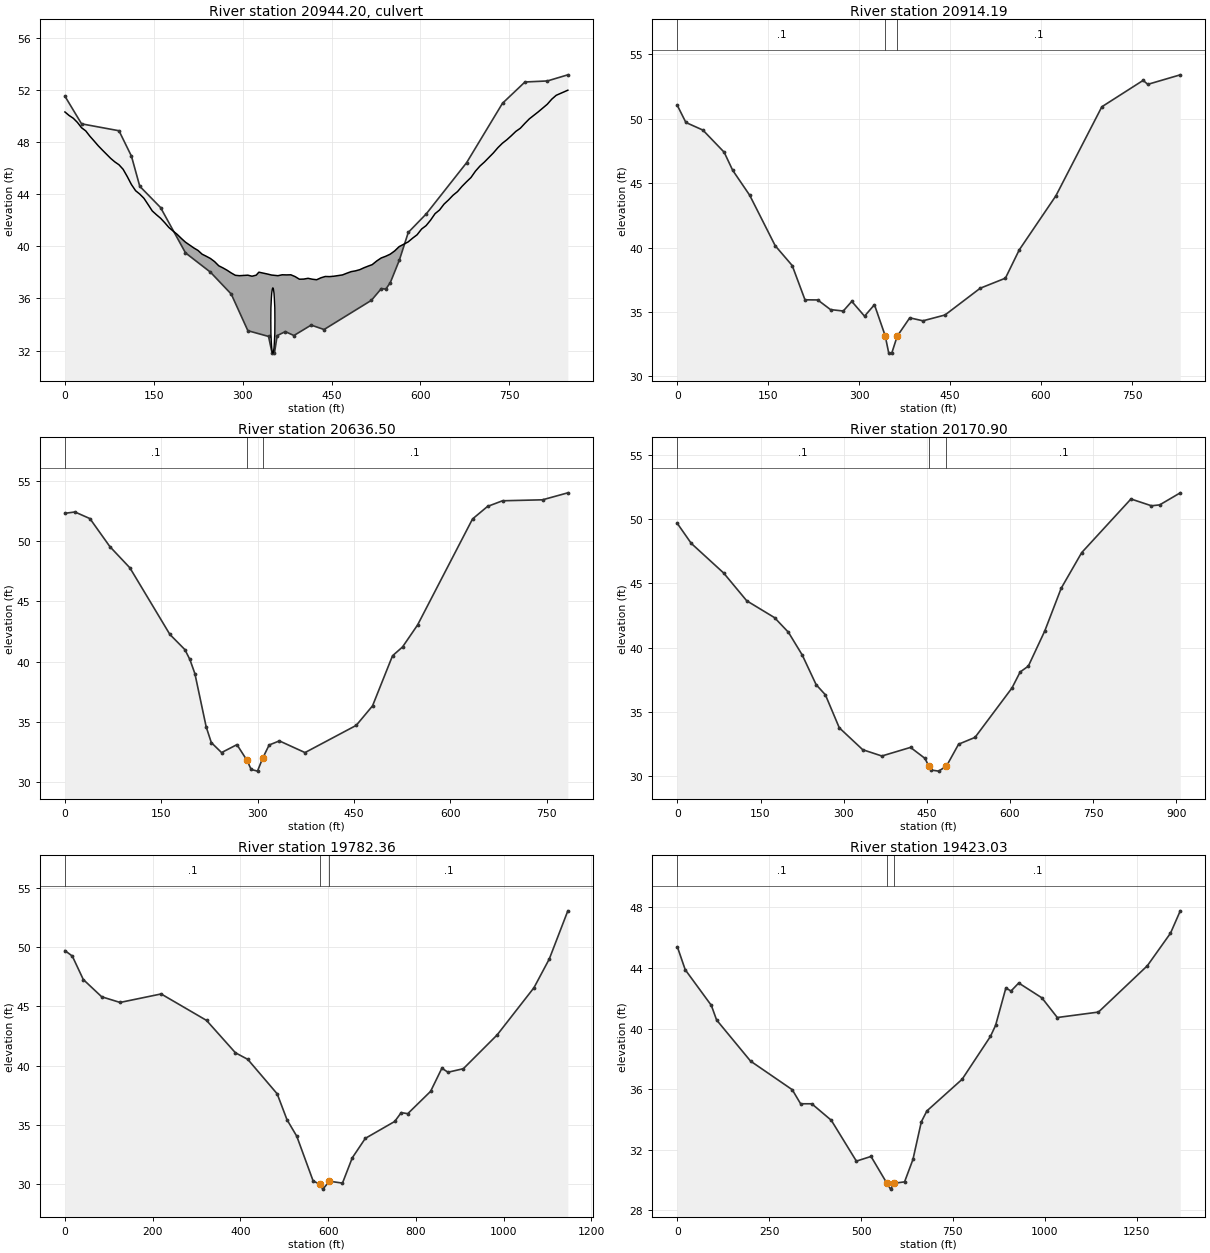
Type RM Length L Ch R = 2 ,20944.20,,,
BEGIN DESCRIPTION:
Hutton Road, MDE Bridge #: CE051007FS-1
Top of road obtained from DEM.
Opening from MDE2 bridge/culvert surveys.
END DESCRIPTION:
Bridge Culvert--1,0,-1,-1, 0
Deck Dist Width WeirC Skew NumUp NumDn MinLoCord MaxHiCord MaxSubmerge Is_Ogee
15,30,2.6,0, 116, 115, , , 0.95, 0, 2,2,,
       0    7.02   14.04   21.05   28.07   35.09   42.11   49.13   56.14   63.16
   70.18    77.2   84.22   91.23   98.25  105.27  112.29  119.31  126.32  133.34
  140.36  147.38   154.4  161.41  168.43  175.45  182.47  189.49   196.5  203.52
  210.54  217.56  224.58  231.59  238.61  245.63  252.65  259.67  266.68   273.7
  280.72  287.74  294.76  301.77  308.79  315.81  322.83  327.36  334.53   341.7
  348.87  359.53  366.79  374.06  381.33   388.6  395.86  403.13   410.4  417.67
  424.93   432.2  439.47  446.74     454  461.27  468.54  475.81  483.07  490.34
  497.61  504.87  512.14  518.74  526.32  533.89  541.47  549.04  556.62  564.19
  571.77  579.34  586.92   594.5  602.07  609.65  617.22   624.8  632.37  639.95
  647.52   655.1  662.68  670.25  677.83   685.4  692.98  700.55  708.13  715.71
  723.28  730.86  738.43  746.01  753.58  761.16  768.73  776.31  783.89  791.46
  799.04  806.61  814.19  821.76  829.34  848.95
    50.3   50.03   49.82    49.5   49.09   48.85   48.44   48.08   47.71   47.38
   47.06   46.74   46.47   46.25    45.9   45.34   44.73   44.26      44   43.68
    43.2   42.71   42.42   42.15   41.81   41.44   41.17   40.91    40.6   40.31
   40.09   39.87   39.68   39.39   39.23   39.06   38.82    38.5   38.34   38.16
   37.95   37.77   37.74   37.76   37.78    37.7   37.78   38.01   37.94   37.87
   37.79   37.74   37.81    37.8   37.81   37.67   37.47   37.48   37.54   37.47
   37.43   37.58   37.68   37.67    37.7   37.75    37.8   37.93   38.05   38.11
    38.2   38.35   38.48   38.59   38.87    39.1   39.23   39.39   39.64   39.97
   40.15   40.33   40.62   40.88   41.32   41.58      42    42.5   42.78   43.23
   43.55   43.91   44.19   44.59   44.94   45.27   45.76   46.15   46.46   46.81
   47.16   47.56    47.9   48.17   48.48   48.81   49.05   49.42   49.77   50.04
   50.31    50.6   50.89   51.28   51.58   51.97
                                                                                
                                                                                
                                                                                
                                                                                
                                                                                
                                                                                
                                                                                
                                                                                
                                                                                
                                                                                
                                                                                
                                                
       0    7.02   14.04   21.05   28.07   35.09   42.11   49.13   56.14   63.16
   70.18    77.2   84.22   91.23   98.25  105.27  112.29  119.31  126.32  133.34
  140.36  147.38   154.4  161.41  168.43  175.45  182.47  189.49   196.5  203.52
  210.54  217.56  224.58  231.59  238.61  245.63  252.65  259.67  266.68   273.7
  280.72  287.74  294.76  301.77  308.79  315.81  322.83  327.36  334.53   341.7
  348.87  359.53  366.79  374.06  381.33   388.6  395.86  403.13   410.4  417.67
  424.93   432.2  439.47  446.74     454  461.27  468.54  475.81  483.07  490.34
  497.61  504.87  512.14  518.74  526.32  533.89  541.47  549.04  556.62  564.19
  571.77  579.34  586.92   594.5  602.07  609.65  617.22   624.8  632.37  639.95
  647.52   655.1  662.68  670.25  677.83   685.4  692.98  700.55  708.13  715.71
  723.28  730.86  738.43  746.01  753.58  761.16  768.73  776.31  783.89  791.46
  799.04  806.61  814.19  821.76  829.68
    50.3   50.03   49.82    49.5   49.09   48.85   48.44   48.08   47.71   47.38
   47.06   46.74   46.47   46.25    45.9   45.34   44.73   44.26      44   43.68
    43.2   42.71   42.42   42.15   41.81   41.44   41.17   40.91    40.6   40.31
   40.09   39.87   39.68   39.39   39.23   39.06   38.82    38.5   38.34   38.16
   37.95   37.77   37.74   37.76   37.78    37.7   37.78   38.01   37.94   37.87
   37.79   37.74   37.81    37.8   37.81   37.67   37.47   37.48   37.54   37.47
   37.43   37.58   37.68   37.67    37.7   37.75    37.8   37.93   38.05   38.11
    38.2   38.35   38.48   38.59   38.87    39.1   39.23   39.39   39.64   39.97
   40.15   40.33   40.62   40.88   41.32   41.58      42    42.5   42.78   43.23
   43.55   43.91   44.19   44.59   44.94   45.27   45.76   46.15   46.46   46.81
   47.16   47.56    47.9   48.17   48.48   48.81   49.05   49.42   49.77   50.04
   50.31    50.6   50.89   51.28   51.58
                                                                                
                                                                                
                                                                                
                                                                                
                                                                                
                                                                                
                                                                                
                                                                                
                                                                                
                                                                                
                                                                                
                                        
BR Coef=-1 , 0 , 0 ,, 0 ,,,0.8,0,,0,
WSPro=,,,, 1 ,,,, 0 ,,,, 0 ,,,,-1 ,-1 ,-1 , 0 , 0 , 0 , 0 , 0
Culvert=3,5,6.88,32,0.025,0.5,1,34,1,31.8,351,31.8,351,Culvert #1  , 0 ,14
Culvert Bottom n=0.025
BC Design=,, 0 ,, 0 ,,,,,,
BC Use User HTab Curves=0
BC User HTab FreeFlow(D)= 0

Type RM Length L Ch R = 1 ,20914.19,231.62,277.69,275.6
BEGIN DESCRIPTION:
Center of channel lowered 1 ft based on bridge survey info.
END DESCRIPTION:
XS GIS Cut Line= 5
1653653.73720418700558.9924690281653630.47357932700883.297042802
1653624.13088086700911.7552462521653582.03271574701062.607004523
 1653460.1518317701357.152474359
#Sta/Elev= 30
       0   51.03   14.04   49.71   42.11   49.12    77.2    47.4   91.23      46
  119.31   44.06  161.41   40.14  189.49    38.6  210.54   35.94  231.59   35.93
  252.65   35.18   273.7   35.07  287.74   35.82  308.79   34.67  325.14   35.56
  342.79   33.16  348.75    31.8   353.7    31.8  362.73   33.12  383.36   34.54
  405.17   34.31   441.5   34.76  499.64   36.84  541.21   37.62  563.94   39.81
  624.54   44.02   700.3   50.93  768.48   52.98  776.06   52.67  829.68   53.41
#Mann= 3 , 0 , 0
       0      .1       0  342.79     .04       0  362.73      .1       0
Bank Sta=342.79,362.73
XS Rating Curve= 0 ,0
Exp/Cntr=0.5,0.3

Type RM Length L Ch R = 1 ,20636.50,432.75,465.61,405.48
XS GIS Cut Line= 6
1653554.85444547700511.7113796471653462.42603301700702.344980299
 1653429.6909703700762.0383300041653408.50945912700783.219841212
1653327.63459823700931.4904194921653194.76875536701204.924472958
#Sta/Elev= 30
       0   52.32   15.56   52.43    38.9   51.88   70.01   49.55  101.13   47.79
  163.37   42.26  186.71      41  194.48   40.18  202.26   39.01  219.84   34.59
  227.83   33.28  243.79   32.45  267.74   33.11  283.45    31.8  289.84   31.05
  299.74   30.91  307.56   31.96  317.87   33.08  333.81   33.42  373.68   32.45
  453.42   34.71  478.79   36.33  509.92   40.49  525.48   41.22  548.83   43.04
  634.44   51.85  657.79   52.89  681.14   53.36   743.4   53.44  782.79   54.02
#Mann= 3 , 0 , 0
       0      .1       0  283.45     .04       0  307.56      .1       0
Bank Sta=283.45,307.56
XS Rating Curve= 0 ,0
Exp/Cntr=0.3,0.1

Type RM Length L Ch R = 1 ,20170.90,393.32,388.54,388.84
XS GIS Cut Line= 5
1653289.92712088700207.345982447 1653121.8497902700466.125586838
1653034.94462548700586.8094647531653029.16784972700629.172487125
1652896.30200684701014.290872306
#Sta/Elev= 30
       0   49.68   25.04   48.13   83.47   45.82   125.2   43.65  175.28   42.34
  200.33    41.2  225.37   39.42  250.41   37.11   267.1   36.32  292.14   33.75
  334.45   32.04  368.95   31.55  420.71   32.22  446.59   31.37  453.35   30.79
  457.29   30.46  471.42   30.37  485.55   30.76  507.45   32.47  537.07      33
  603.71   36.85  618.52    38.1  633.33   38.56  662.95    41.3  692.57   44.63
   729.6   47.41  818.46   51.59  855.48   51.06  870.29   51.13  907.44   52.07
#Mann= 3 , 0 , 0
       0      .1       0  453.35     .04       0  485.55      .1       0
Bank Sta=453.35,485.55
XS Rating Curve= 0 ,0
Exp/Cntr=0.3,0.1

Type RM Length L Ch R = 1 ,19782.36,345.88,359.33,356.46
XS GIS Cut Line= 5
1653088.93432318699990.144088149  1652929.265448700095.222409248
1652738.63177486700307.583822548 1652615.7041764700647.998710558
 1652615.6287027700956.206244975
#Sta/Elev= 30
       0   49.73   16.76   49.27    41.9   47.28    83.8   45.82   125.7   45.34
  219.36   46.06  322.84   43.82  388.68   41.08   416.9   40.52  483.96    37.6
  506.29   35.41  528.61   34.01  565.83   30.23  580.7829.94605  588.15   29.53
  603.04    30.2  632.81   30.04  655.14   32.18  684.91   33.83  751.89   35.26
  766.77   36.01  781.66   35.92  833.75   37.81  859.45   39.77  873.45   39.43
  908.45   39.73  985.45   42.59 1069.45   46.59 1104.45   49.03 1146.66    53.1
#Mann= 3 , 0 , 0
       0      .1       0  580.78     .04       0  603.04      .1       0
Bank Sta=580.78,603.04
XS Rating Curve= 0 ,0
Exp/Cntr=0.3,0.1

Type RM Length L Ch R = 1 ,19423.03,408.78,419.87,363.46
XS GIS Cut Line= 5
1652547.55049698 699740.524000631652495.68138792700025.804100633
1652415.70720209700216.4792173061652322.98140773700434.028196469
1652307.65586749701069.669921115
#Sta/Elev= 30
       0    45.4   21.34   43.89   92.49   41.53  106.72   40.57  199.21   37.85
  312.73   35.96   335.5   35.03  365.87   35.03     419   33.94  487.32   31.24
  527.16   31.55  569.87    29.8  580.43   29.39  590.47   29.78  618.47   29.87
   641.3   31.35  664.13   33.84  679.35   34.56  775.22   36.65  852.24   39.48
  866.25   40.21  894.26   42.68  908.26   42.48  929.27   43.01  992.29   42.03
  1034.3   40.73 1146.33   41.09 1279.37   44.15 1342.39    46.3 1369.04   47.78
#Mann= 3 , 0 , 0
       0      .1       0  569.87     .04       0  590.47      .1       0
Bank Sta=569.87,590.47
XS Rating Curve= 0 ,0
Exp/Cntr=0.3,0.1

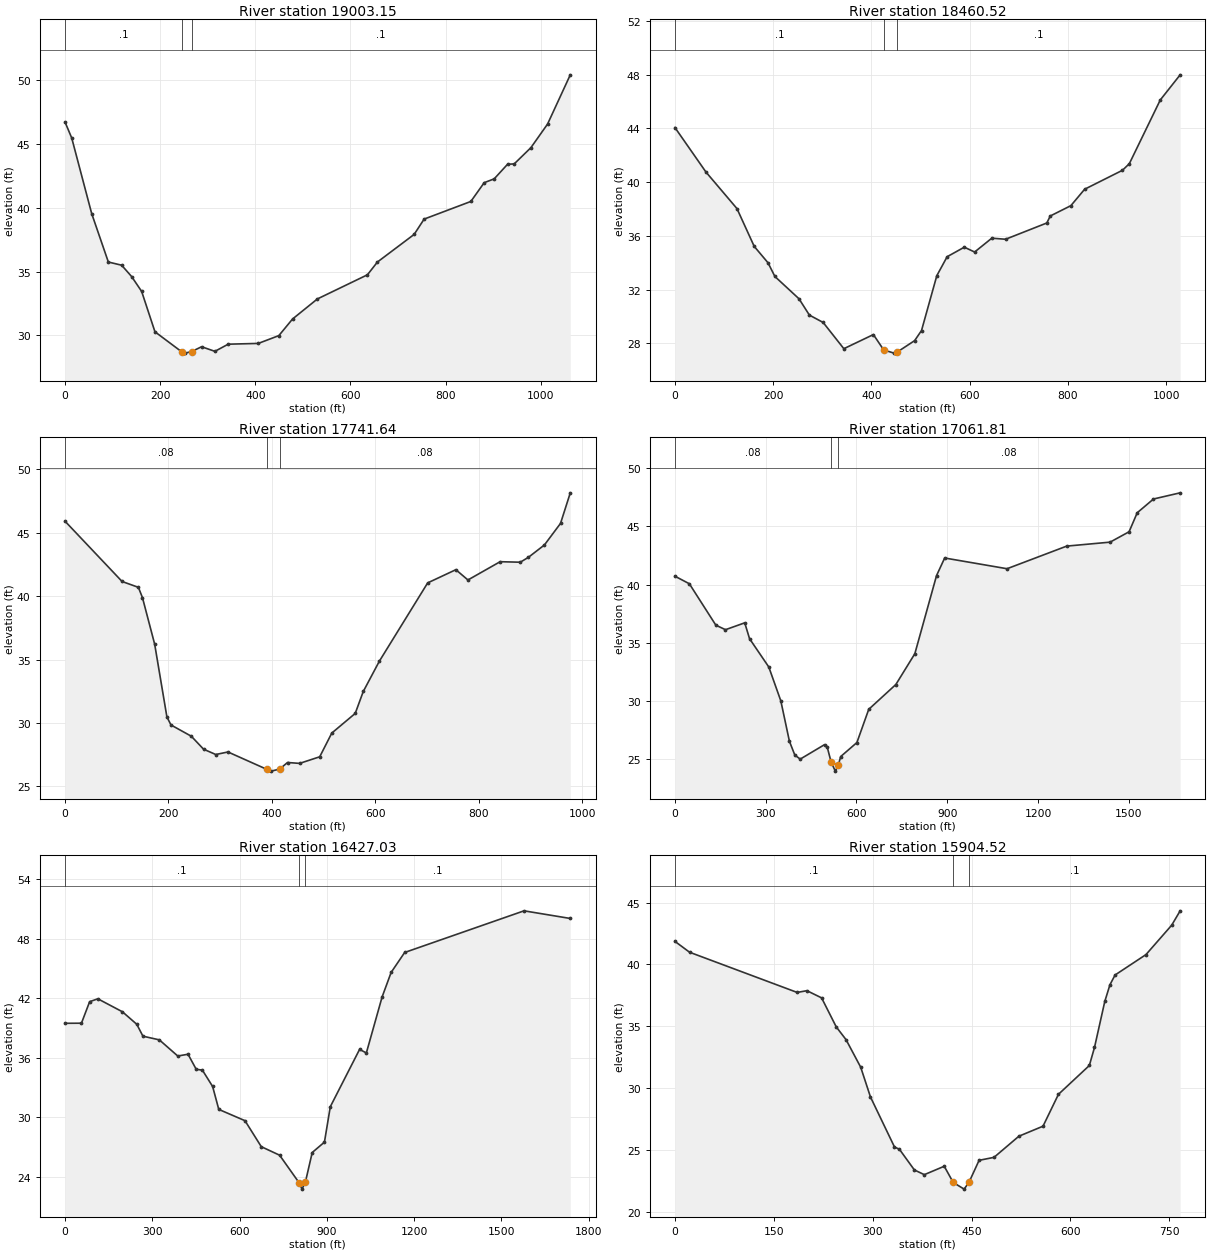
Type RM Length L Ch R = 1 ,19003.15,491.02,542.64,493.96
XS GIS Cut Line= 4
1652015.89212881699951.2422563141652009.40849017700314.326019958
1652045.06850271700463.4497085961652080.72851519701008.075354069
#Sta/Elev= 30
       0    46.7      14   45.46   56.01   39.54   91.01   35.75  119.02    35.5
  140.02   34.61  161.03   33.45  189.03   30.29  245.04   28.73  252.04   28.62
  266.04   28.74  287.05   29.12  315.05   28.76  343.05   29.32  406.33   29.38
  449.51   29.99   478.3   31.29   530.5   32.86  635.73   34.75  656.77   35.75
  733.94   37.91  754.98   39.11  853.19   40.49  881.25   41.96   902.3   42.26
  930.36    43.4  944.39   43.43  979.46    44.7 1014.54   46.55 1062.26    50.4
#Mann= 3 , 0 , 0
       0      .1       0  245.04     .04       0  266.04      .1       0
Bank Sta=245.04,266.04
XS Rating Curve= 0 ,0
Exp/Cntr=0.3,0.1

Type RM Length L Ch R = 1 ,18460.52,565.33,718.88,656.36
XS GIS Cut Line= 4
1651594.45561746700025.804100633 1651565.2792436700414.822418839
 1651565.2792436700550.9788302031651568.52106291701053.460824504
#Sta/Elev= 30
       0   44.06   63.18   40.75  126.35   38.03  161.45   35.22  189.53      34
  203.57   32.98  252.71   31.32  273.77   30.11  301.85   29.56  343.96   27.61
  404.11   28.66  425.11   27.52  446.02   27.28  453.11   27.37  488.11   28.21
  502.11   28.96  533.27   33.04  554.27   34.45  589.27   35.16  610.27    34.8
  645.27   35.83  673.27   35.75  757.27   36.96  764.27   37.48  806.27   38.25
  834.27   39.47  911.27   40.88  925.27   41.37  988.28   46.11 1028.76   47.98
#Mann= 3 , 0 , 0
       0      .1       0  425.11     .04       0  453.11      .1       0
Bank Sta=425.11,453.11
XS Rating Curve= 0 ,0
Exp/Cntr=0.3,0.1

Type RM Length L Ch R = 1 ,17741.64,541.46,679.83,625.2
XS GIS Cut Line= 4
1651182.98137201699897.6592084621651007.21270497700238.478940934
1650936.47653408 700384.238323391650747.84674497700772.215503126
#Sta/Elev= 30
       0   45.91  110.27   41.16  141.77    40.7  149.65   39.89  173.27   36.22
   196.9   30.49  204.78   29.85  244.16   28.96  267.79   27.94  291.41   27.52
  315.04   27.72  390.76   26.34  398.69   26.21  414.8926.37149  430.16   26.89
   453.5   26.82   492.4   27.34  515.75   29.21  561.06   30.76  576.62   32.49
  607.76   34.88  701.16   41.05  755.65   42.09     779   41.28  841.26   42.72
  880.18   42.68  895.75   43.06  926.88   44.04  958.02   45.74  976.89   48.15
#Mann= 3 , 0 , 0
       0     .08       0  390.76     .04       0  414.89     .08       0
Bank Sta=390.76,414.89
XS Rating Curve= 0 ,0
Exp/Cntr=0.3,0.1

Type RM Length L Ch R = 1 ,17061.81,460.73,634.79,596.24
XS GIS Cut Line= 4
1650972.91637965699673.6613339631650655.67537083699845.142960384
1650482.05022408700064.8537942021649838.99412504700868.673917979
#Sta/Elev= 30
       0   40.72   47.74   40.07  135.27   36.52   167.1   36.13  230.76   36.72
  246.67   35.36  310.33   32.93  350.12   30.02  378.47   26.56  396.31   25.38
  414.15   25.03  494.45   26.27  503.37   26.07  516.21   24.79  530.14      24
  540.26   24.53  547.98   25.25  601.51   26.45  640.65    29.3   730.3   31.43
  793.05   34.07  864.76   40.77  891.66   42.28 1097.84   41.36 1295.05    43.3
 1438.48   43.64 1501.23   44.53 1528.13   46.16 1581.91   47.34 1670.04   47.87
#Mann= 3 , 0 , 0
       0     .08       0  516.21     .04       0  540.26     .08       0
Bank Sta=516.21,540.26
XS Rating Curve= 0 ,0
Exp/Cntr=0.3,0.1

Type RM Length L Ch R = 1 ,16427.03,502.06,522.51,456.76
XS GIS Cut Line= 4
 1650983.6339813699568.6288378091650424.77740513699633.376625612
1650083.35544267699645.7955696731649330.66231038700002.217577726
#Sta/Elev= 30
       0   39.47   56.37   39.48   84.56   41.65  112.75   41.94  197.31   40.63
  246.64   39.37  267.78   38.17  324.15    37.8  387.58   36.17  422.81   36.35
     451   34.83  472.14   34.75  507.37    33.1  528.51   30.79  618.63   29.65
  674.67   27.03  737.71   26.17   805.3   23.37  814.76   22.75  826.64    23.5
  849.78   26.44  891.81   27.49  911.99   31.06 1012.67   36.84 1035.91   36.48
 1090.13   42.13 1121.11    44.6 1167.58   46.61 1578.07   50.81 1737.06   50.04
#Mann= 3 , 0 , 0
       0      .1       0   805.3     .04       0  826.64      .1       0
Bank Sta=805.3,826.64
XS Rating Curve= 0 ,0
Exp/Cntr=0.3,0.1

Type RM Length L Ch R = 1 ,15904.52,608.72,637.12,547.99
XS GIS Cut Line= 4
 1650512.0595087699024.174673975 1650211.9666625699129.207170129
1649989.04054818 699219.235023991649802.55427942699311.406398192
#Sta/Elev= 30
       0   41.86   22.25   40.98  185.41   37.73  200.24   37.87  222.49   37.29
  244.74   34.94  259.57   33.91  281.82   31.68  296.65   29.27  333.04   25.23
  340.59   25.04  363.24   23.37  378.34   22.99  408.53   23.67  422.12   22.36
  438.73   21.82  446.42   22.41  461.38   24.15  484.03   24.39  521.77    26.1
  558.36   26.91  581.79   29.49  628.64   31.82  636.45   33.28  652.06      37
  659.87   38.35  667.68   39.14  714.53   40.79  753.57   43.17  766.38   44.33
#Mann= 3 , 0 , 0
       0      .1       0  422.12     .04       0  446.42      .1       0
Bank Sta=422.12,446.42
XS Rating Curve= 0 ,0
Exp/Cntr=0.3,0.1

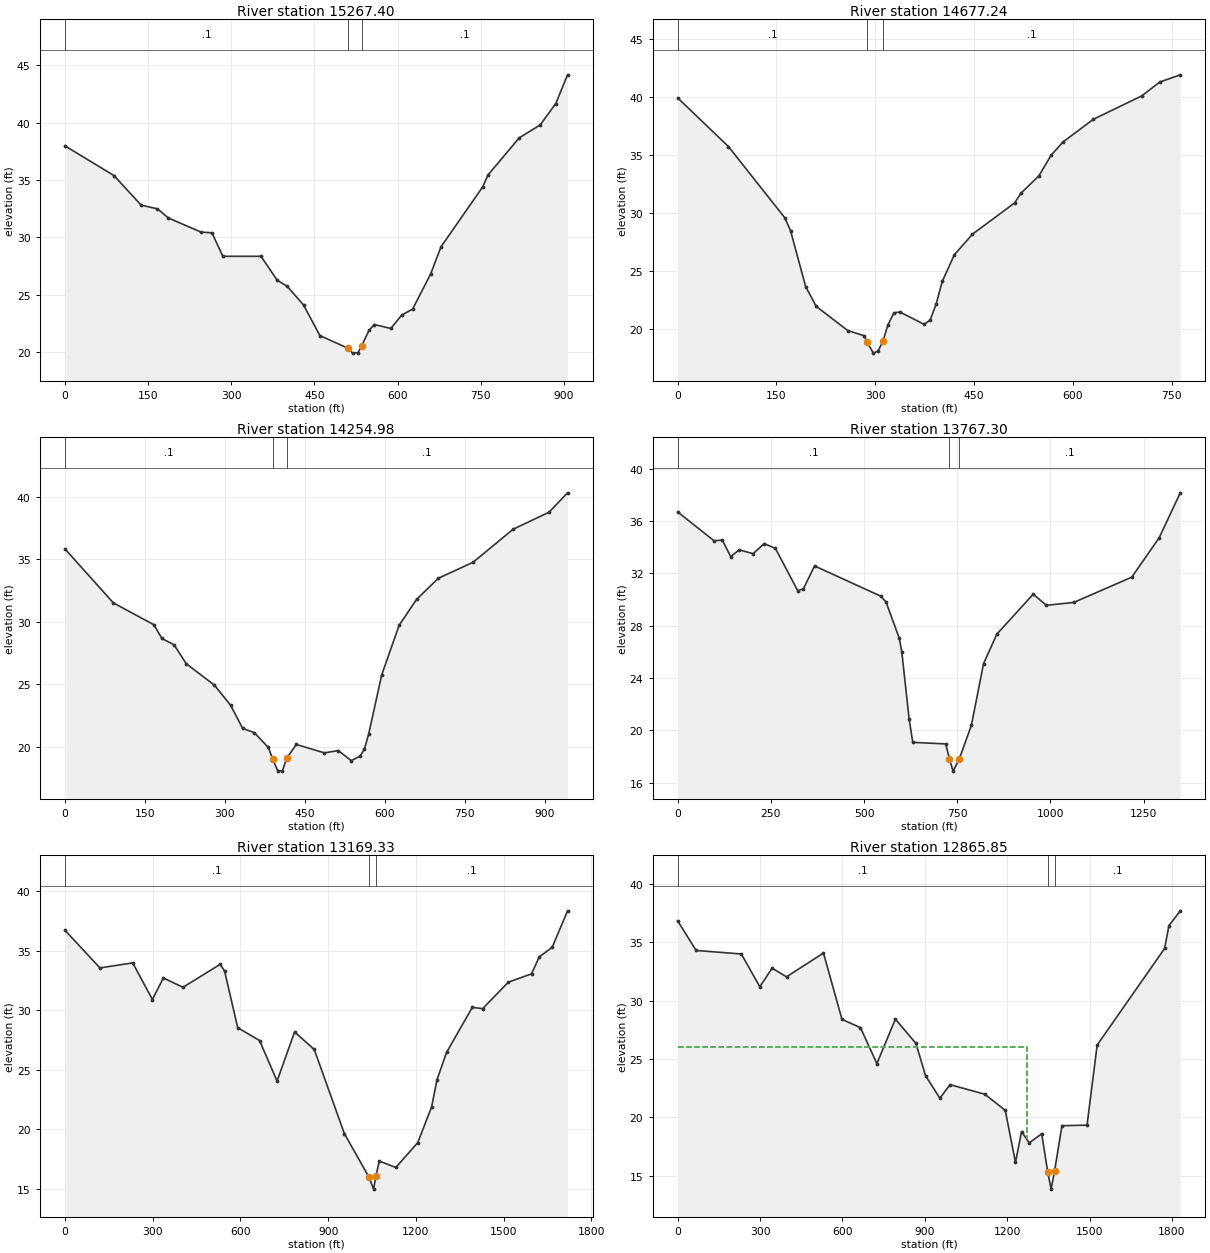
Type RM Length L Ch R = 1 ,15267.40,475.08,590.16,529.4
XS GIS Cut Line= 4
1650216.25370315698312.525924385 1649941.8831009698591.183567286
1649757.54035249698773.3827953641649566.76704314698944.864421755
#Sta/Elev= 30
       0   37.99   88.41    35.4  137.53   32.82     167    32.5  186.65    31.7
  245.59   30.47  265.24   30.41  284.89   28.36  353.65   28.36  383.12   26.27
   400.9   25.75  430.43   24.12  459.96   21.45  511.33   20.33  519.01   19.92
  528.85   19.97  535.45   20.56  548.54   21.91  558.38   22.41   587.9   22.07
  607.59   23.24  627.27   23.76  659.66   26.81  678.49   29.19  753.79   34.42
   763.2   35.45  819.67   38.69  857.32   39.81  885.56   41.68  906.77   44.18
#Mann= 3 , 0 , 0
       0      .1       0  511.33     .04       0  535.45      .1       0
Bank Sta=511.33,535.45
XS Rating Curve= 0 ,0
Exp/Cntr=0.3,0.1

Type RM Length L Ch R = 1 ,14677.24,420.22,422.26,397.46
XS GIS Cut Line= 5
1649804.69779977698168.9100622681649658.93841735698271.799038112
1649573.19760415698318.9564853911649530.32719752698321.100005716
1649191.65098539698608.331729949
#Sta/Elev= 30
       0   39.95   77.11   35.75   162.8   29.59  171.37   28.49  194.39   23.66
  210.37   21.95   258.3   19.86  283.28   19.41   287.6   18.86  297.29   17.91
   304.3   18.09  311.72   18.93  319.19   20.33  328.37   21.39  337.55   21.46
  374.26    20.4  383.44   20.76  392.62   22.16   401.8    24.1  420.16    26.4
  447.69   28.18  511.94   30.89  521.12   31.71  548.65   33.22  567.01   34.99
  585.37   36.15  631.26    38.1  704.69   40.12  732.22   41.32  763.27   41.94
#Mann= 3 , 0 , 0
       0      .1       0   287.6     .04       0  311.72      .1       0
Bank Sta=287.6,311.72
XS Rating Curve= 0 ,0
Exp/Cntr=0.3,0.1

Type RM Length L Ch R = 1 ,14254.98,434.01,487.68,415.02
XS GIS Cut Line= 5
1649721.10050687697813.0856874731649401.30392434697946.230703279
1649248.96838391 698061.10668461 1649046.2460639698182.740076602
1648930.14150511698306.095363408
#Sta/Elev= 30
       0   35.83   90.99   31.51  166.81   29.77  181.98   28.67  204.73   28.17
  227.47   26.66  280.55   24.94  310.88   23.33  333.63   21.48  355.17   21.15
  381.48   19.97  390.24      19  399.01   18.12  407.78   18.07  416.15    19.1
  434.08    20.2  486.68   19.53  512.98   19.71   537.2   18.91  553.53   19.26
  561.69   19.81  569.85   21.03  594.34   25.76     627   29.72  659.65   31.79
  700.47   33.48  765.77   34.76   840.9    37.4   908.2   38.76  943.02   40.31
#Mann= 3 , 0 , 0
       0      .1       0  390.24     .04       0  416.15      .1       0
Bank Sta=390.24,416.15
XS Rating Curve= 0 ,0
Exp/Cntr=0.3,0.1

Type RM Length L Ch R = 1 ,13767.30,425.51,597.97,470.67
XS GIS Cut Line= 6
1649702.59665763697726.1736447811649306.25686115697574.709274486
1649131.63241611697603.0206951351648990.16007434697746.636557266
1648852.97477321697922.405224308 1648645.0533012698168.910062268
#Sta/Elev= 30
       0   36.69   97.42   34.49   119.9   34.53  142.38   33.27  164.86   33.79
  202.33    33.5  232.31   34.27  262.28    33.9  322.23   30.66  337.22   30.81
  367.19   32.56  544.85   30.25  559.03    29.8  594.49   27.03   601.2   25.99
  620.85   20.88  630.68   19.07  719.11   18.95  728.94   17.83  738.76   16.87
  755.42    17.8  787.89   20.37  820.55   25.09  856.07   27.34  953.75    30.4
  989.27   29.55 1062.39   29.77 1218.07    31.7 1291.33    34.7 1348.25   38.15
#Mann= 3 , 0 , 0
       0      .1       0  728.94     .04       0  755.42      .1       0
Bank Sta=728.94,755.42
XS Rating Curve= 0 ,0
Exp/Cntr=0.3,0.1

Type RM Length L Ch R = 1 ,13169.33,308.22,303.47,270.98
XS GIS Cut Line= 6
1649679.22601323697708.1145104771648850.83125292697397.242743447
1648705.07187043697416.5344264361648675.06258582697431.539068744
1648510.01152043697579.4419714961648248.50204015697922.405224308
#Sta/Elev= 30
       0   36.74  119.63   33.57  231.78   33.99  299.07   30.91  336.45   32.72
  403.74   31.94  530.84   33.87   545.8   33.31  590.66   28.54  665.42   27.46
  725.24   24.05  785.05   28.18  852.34   26.71  955.42   19.62 1038.54   16.01
 1055.31   14.96 1063.45    16.1 1074.79   17.32 1131.18   16.78 1206.38   18.88
 1253.37   21.86 1272.17   24.18 1304.62   26.46 1392.64   30.25 1427.85   30.14
 1515.88   32.37 1595.11   33.07 1621.51    34.5 1665.53   35.29  1718.3   38.37
#Mann= 3 , 0 , 0
       0      .1       0 1038.54     .04       0 1063.45      .1       0
Bank Sta=1038.54,1063.45
XS Rating Curve= 0 ,0
Exp/Cntr=0.3,0.1

Type RM Length L Ch R = 1 ,12865.85,270.45,300.94,339.96
XS GIS Cut Line= 6
1649682.23932165697705.778962061 1648490.7220289697263.212373897
1648434.67134941697309.4510870131648418.26195219697337.951619029
1648293.89599426697390.6344206631648012.35656604697539.501417384
#Sta/Elev= 30
       0   36.85   67.31   34.31  231.85   34.01  299.17    31.2  344.04   32.79
   396.4   32.05  531.02   34.09  598.33    28.4  665.65   27.69  725.48   24.61
  792.79   28.42  867.58   26.34  902.65   23.57  954.74   21.64  991.94    22.8
 1118.42   21.98 1192.83    20.6 1230.03   16.14 1252.35   18.78 1280.15    17.8
 1325.53   18.59 1347.74   15.28  1359.9   13.84 1372.26   15.37 1399.43   19.28
 1490.66   19.33 1527.53    26.2    1773   34.48 1788.83   36.44 1830.17   37.71
#Mann= 3 , 0 , 0
       0      .1       0 1347.74     .04       0 1372.26      .1       0
#XS Ineff= 2 , 0
       0    1271      26               0
Permanent Ineff=
       F       F
Bank Sta=1347.74,1372.26
XS Rating Curve= 0 ,0
Exp/Cntr=0.3,0.1

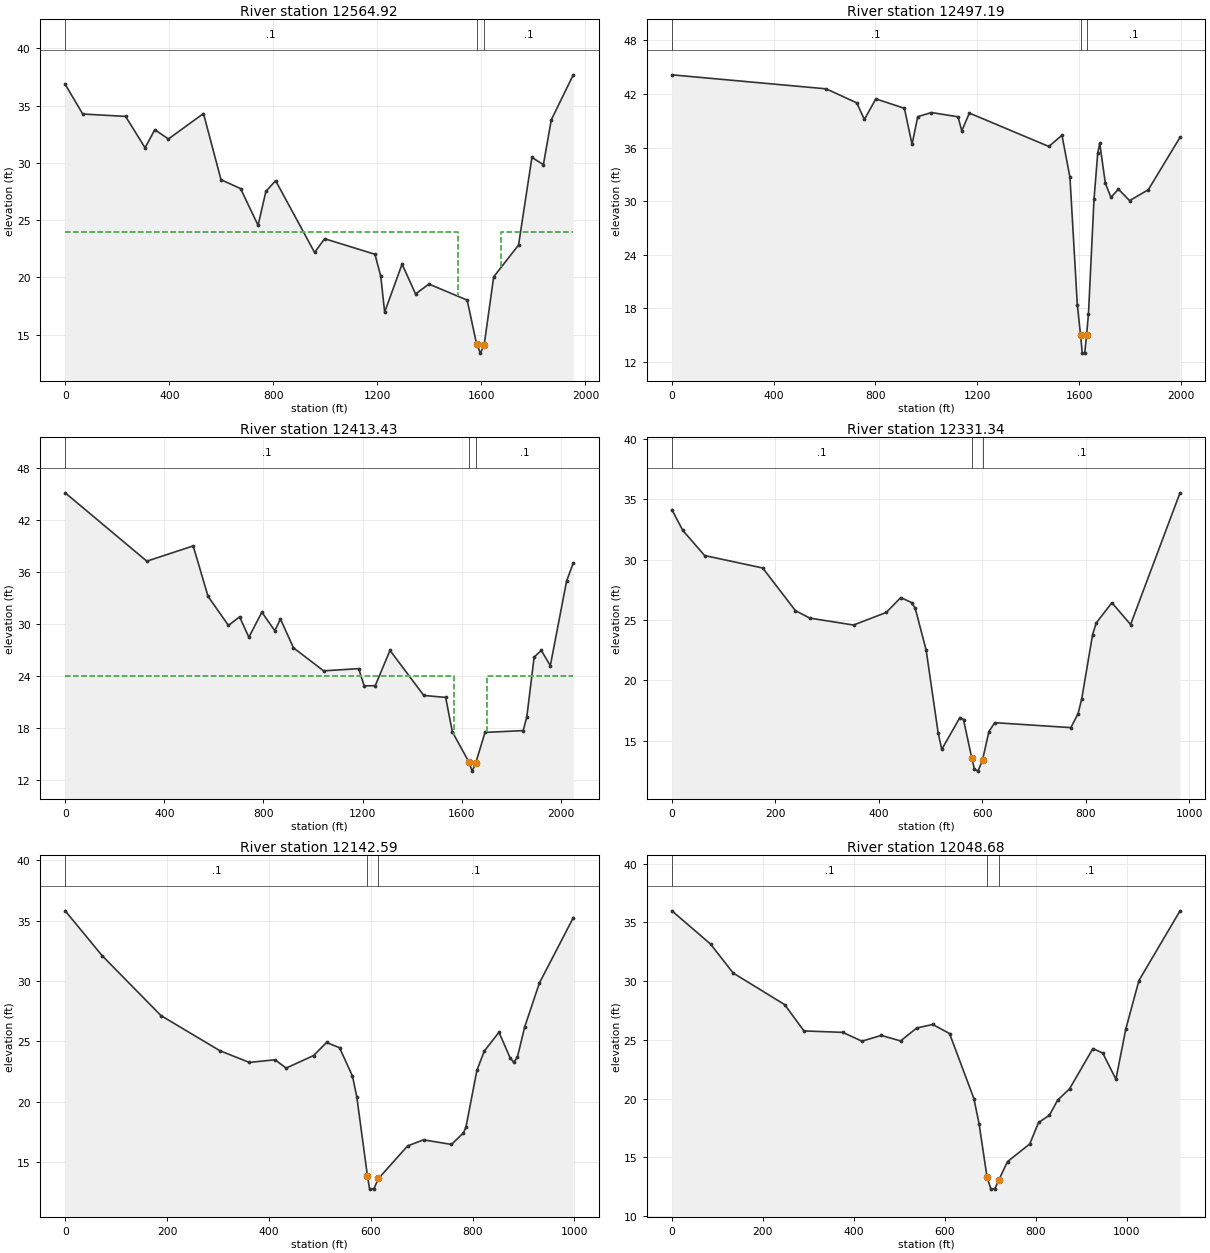
Type RM Length L Ch R = 1 ,12564.92,81.3,67.72,65.38
XS GIS Cut Line= 6
 1649684.4315279697705.1946698281648773.08084804697358.648870289
1648437.13626097697237.5429203961648241.20866868697174.355972782
1647931.75237983697080.8813760131647843.80423261697107.276260376
#Sta/Elev= 30
       0   36.85   67.39   34.26   232.1   34.05  306.98   31.31  344.41   32.89
  396.82   32.08  531.59    34.3  598.98   28.52  674.03   27.75  741.46   24.54
  771.43    27.5  808.89   28.44  958.74   22.17  997.34   23.37  1190.8   22.01
 1213.13   20.08 1228.01   16.96 1294.98   21.15 1346.83   18.55 1398.32   19.41
 1545.26   18.01 1581.44   14.17 1596.18   13.38 1610.73   14.11  1647.1   20.04
 1742.75   22.82 1794.15   30.47  1838.2   29.84  1868.6   33.75 1953.11   37.68
#Mann= 3 , 0 , 0
       0      .1       0 1581.44     .04       0 1610.73      .1       0
#XS Ineff= 2 , 0
       0    1510      24    1677       0      24
Permanent Ineff=
       F       F
Bank Sta=1581.44,1610.73
XS Rating Curve= 0 ,0
Exp/Cntr=0.5,0.3

Type RM Length L Ch R = 1 ,12497.19,80.42,83.76,85.67
BEGIN DESCRIPTION:
Bottom of channel lowered 1 ft based on DEM immediately upstream and downstream of where the cross-section was cut.
END DESCRIPTION:
XS GIS Cut Line= 6
1649707.49688134697644.4246980251648795.69099788697297.705093339
1648458.13945967697176.0198474681648260.03602296697112.131186724
1647932.26488058697012.863355055   1647825.11984 697045.01958625
#Sta/Elev= 30
       0   44.15  606.47   42.58  726.42   41.01  756.39   39.15  801.34   41.46
  913.73    40.4   943.7   36.37  966.17   39.47 1020.15   39.93 1124.32   39.45
  1139.2   37.88 1168.97   39.87 1481.42   36.13  1532.9   37.39 1564.29   32.68
 1593.39   18.35 1605.86   15.06 1612.61      13  1622.3      13 1629.76   15.06
 1637.04   17.38 1658.86   30.23 1673.41   35.36 1681.32   36.49 1703.35   32.03
 1725.38   30.43 1754.75   31.35  1798.8   30.07 1872.23   31.29 1996.85   37.15
#Mann= 3 , 0 , 0
       0      .1       0 1605.86     .04       0 1629.76      .1       0
Bank Sta=1605.86,1629.76
XS Rating Curve= 0 ,0
Exp/Cntr=0.5,0.3

Type RM Length L Ch R = 1 ,12413.43,94.51,82.1,79.99
XS GIS Cut Line= 6
1649735.88500868697569.6308866141648823.51887469697222.697367877
 1648483.9895504697100.2991423611648283.20815136697035.546834663
1647932.89565074696929.1488677261647802.12366448696968.395987347
#Sta/Elev= 30
       0    45.1  329.44   37.21  516.62   38.97  576.52   33.15  658.92   29.79
  703.87   30.78  741.33   28.43  793.78   31.32  846.23   29.17   868.7   30.54
  921.15   27.21 1043.07   24.55 1184.45    24.8 1206.77   22.81 1251.42   22.84
 1310.94   26.91 1447.34   21.71  1535.6   21.48 1562.53   17.51 1630.22   13.98
 1642.55   12.97  1657.1   13.92 1694.39   17.44 1848.59   17.65 1863.27   19.26
 1892.64   26.13 1921.45   26.91 1957.99   25.15 2023.77   34.92 2050.67      37
#Mann= 3 , 0 , 0
       0      .1       0 1630.22     .04       0  1657.1      .1       0
#XS Ineff= 2 , 0
       0    1569      24    1704       0      24
Permanent Ineff=
       F       F
Bank Sta=1630.22,1657.1
XS Rating Curve= 0 ,0
Exp/Cntr=0.5,0.3

Type RM Length L Ch R = 1 ,12331.34,190.39,188.74,86.19
XS GIS Cut Line= 5
1648779.10389419696892.2018375251648273.05767132696931.451960102
1648163.71804424696925.8447997271647952.04774053 696918.83584927
1647803.45799086696956.684181705
#Sta/Elev= 30
       0   34.13   21.06   32.42   63.19   30.34  175.53   29.31  238.71   25.78
   266.8   25.16  351.05   24.59  414.24   25.63  442.32   26.86  463.39   26.45
  470.41   25.96  491.47   22.51  514.58   15.68  521.58    14.3  556.63   16.93
  563.64   16.77  579.78   13.55  584.67   12.68  591.68    12.5  600.44   13.42
   612.7   15.77  624.05   16.51  771.13    16.1  785.14   17.26  792.15   18.48
  813.16   23.79  820.16   24.76  850.51   26.44  886.62   24.63  982.17   35.53
#Mann= 3 , 0 , 0
       0      .1       0  579.78     .04       0  600.44      .1       0
Bank Sta=579.78,600.44
XS Rating Curve= 0 ,0
Exp/Cntr=0.5,0.3

Type RM Length L Ch R = 1 ,12142.59,86.64,93.92,78.89
XS GIS Cut Line= 6
1648716.02334011696616.0491896121648252.03081998696736.603137434
1648167.92341451696794.0765311571648148.29835325696824.915913165
1647996.90502343696900.6125780791647792.24367015696951.077021346
#Sta/Elev= 30
       0   35.81   72.32   32.11  188.04   27.14  303.76   24.23  361.62   23.26
  412.25   23.48  433.94   22.79  487.88   23.83  513.31   24.91  538.75   24.48
  564.18   22.13  572.66   20.42  593.54   13.89  597.86   12.77  606.16    12.8
  615.29   13.65   672.6   16.35  703.91   16.85  758.69   16.47  782.17   17.43
  787.08   17.91  808.71   22.62  823.13    24.2  851.97   25.76   873.6   23.66
  880.81   23.27  888.02   23.68  902.44   26.19  931.28   29.83  997.87   35.24
#Mann= 3 , 0 , 0
       0      .1       0  593.54     .04       0  615.29      .1       0
Bank Sta=593.54,615.29
XS Rating Curve= 0 ,0
Exp/Cntr=0.5,0.3

Type RM Length L Ch R = 1 ,12048.68,177.58,250.76,288.94
XS GIS Cut Line= 6
1648741.06750011696515.721109658 1648279.0113087696587.917389572
1648201.03932643 696688.992181421648093.04889087696747.205181867
1647962.63961054696898.5893814121647770.21752554696948.746796921
#Sta/Elev= 30
       0   35.98   85.02   33.15  134.61   30.69  247.97      28  290.48   25.76
   375.5   25.64  418.01   24.89  460.52   25.38  503.03   24.91  538.39   26.01
  573.75   26.31  610.64   25.54  664.29      20   675.6   17.87  692.99   13.36
  701.69    12.3  710.38   12.34  718.65   13.05  738.18   14.64  787.02   16.14
  806.55   17.97  830.49   18.59  848.18   19.86   874.7   20.84  926.02   24.26
  947.72   23.88  976.66   21.65  998.36   25.92 1027.29   30.05 1117.64   35.98
#Mann= 3 , 0 , 0
       0      .1       0  692.99     .04       0  718.65      .1       0
Bank Sta=692.99,718.65
XS Rating Curve= 0 ,0
Exp/Cntr=0.5,0.3