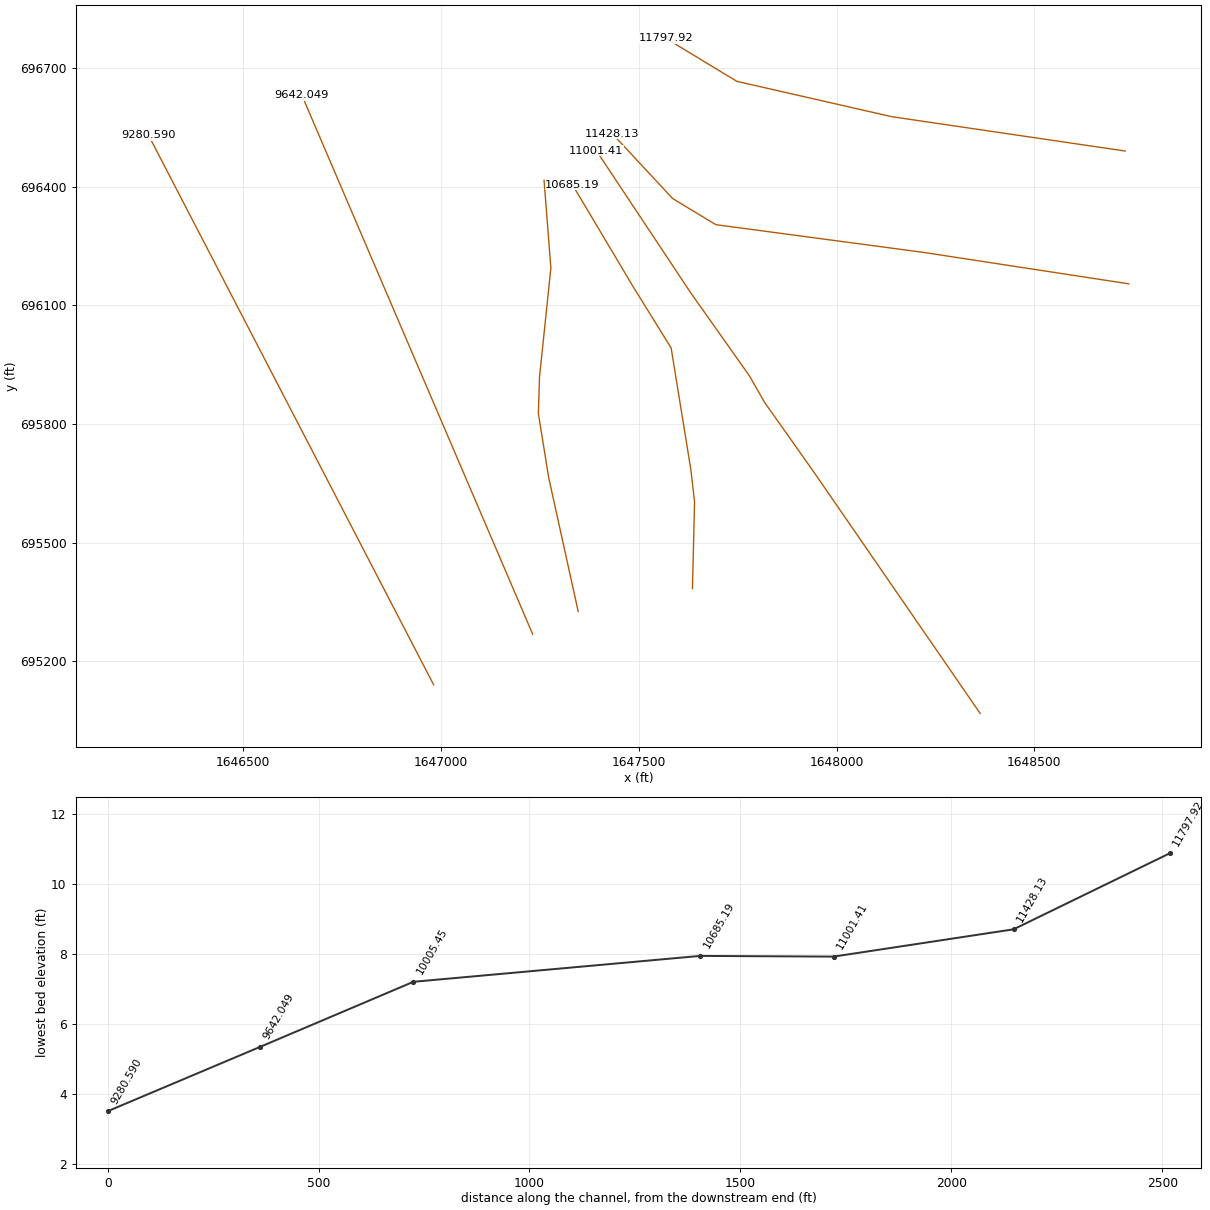
HEC-RAS study PerchCreek.prj: PerchCreek

--- PerchCreek.g01 (geometry) --- (continued)

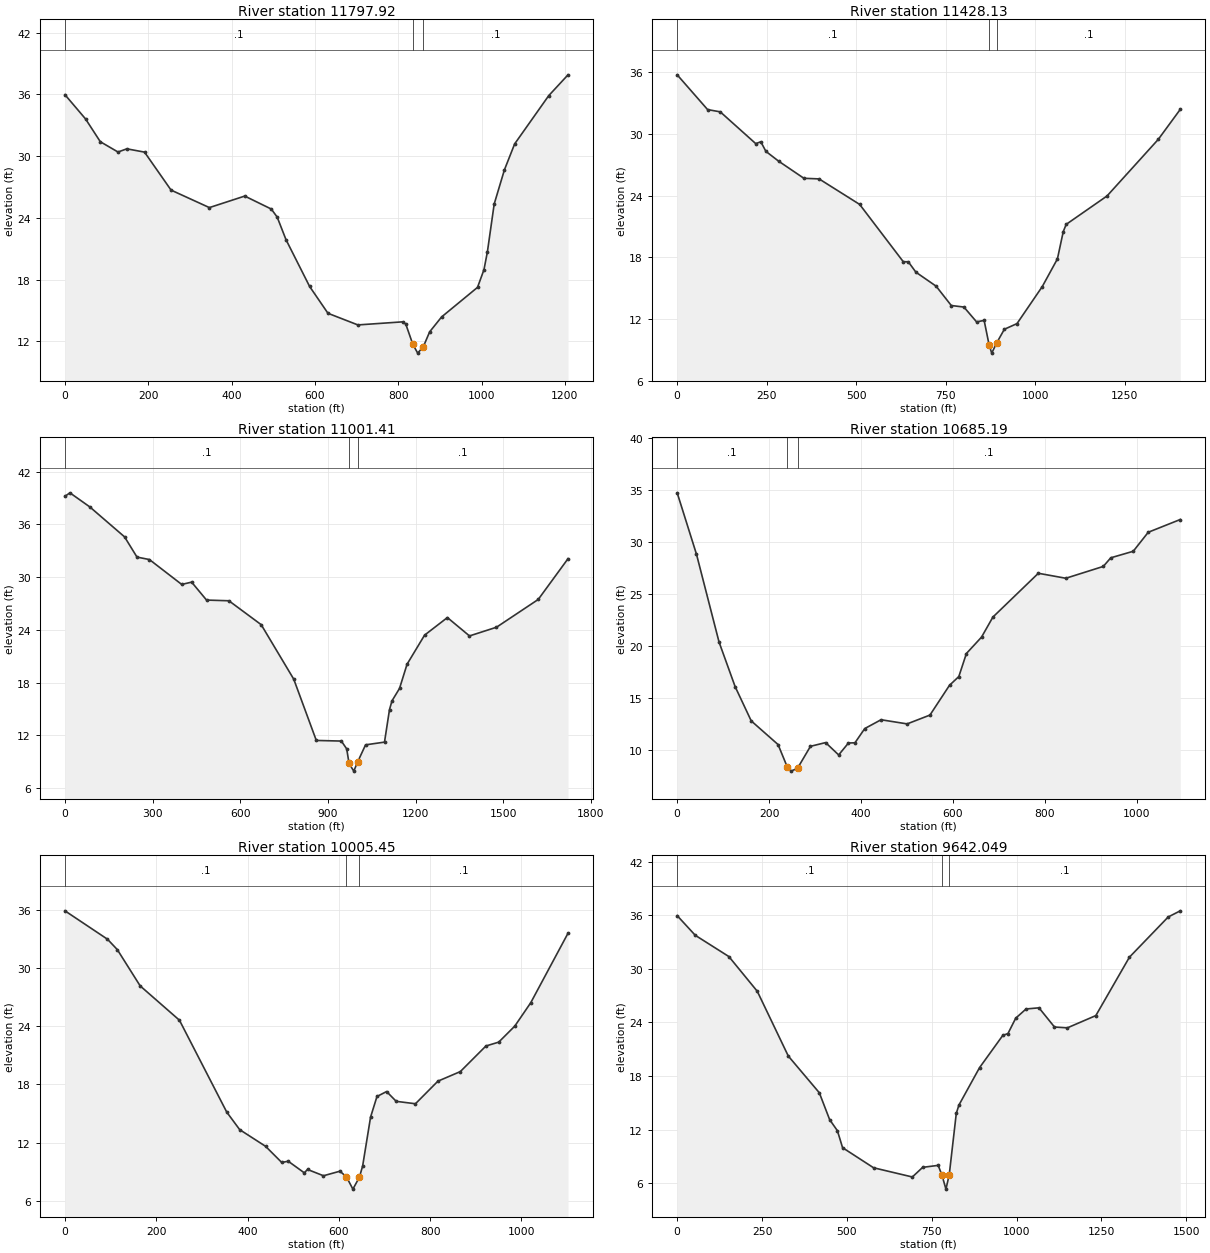
Type RM Length L Ch R = 1 ,11797.92,357.37,369.79,358.74
XS GIS Cut Line= 4
1648729.51609533696489.7304488721648140.39445128696576.365984783
1647748.29650739696665.7747925071647568.72335836 696774.51915139
#Sta/Elev= 30
       0   35.98   49.53   33.62    84.9   31.41  127.36   30.41  148.58   30.72
  191.03    30.4  254.71   26.71  346.69   25.01  431.59   26.13  495.27   24.87
  509.42   24.09  530.65   21.89  587.25   17.35  631.36   14.74  703.15   13.61
  810.85   13.91  818.03    13.7  835.14   11.71  846.75   10.87  860.38   11.51
  875.47   12.94  904.18   14.39  990.34   17.26  1005.8   18.98 1013.99    20.7
 1030.35   25.36 1054.91   28.68 1079.46    31.2 1161.29   35.89 1207.55   37.91
#Mann= 3 , 0 , 0
       0      .1       0  835.14     .04       0  860.38      .1       0
Bank Sta=835.14,860.38
XS Rating Curve= 0 ,0
Exp/Cntr=0.3,0.1

Type RM Length L Ch R = 1 ,11428.13,484.5,426.71,368.33
XS GIS Cut Line= 5
1648738.58245128696154.1126371181648218.83050792696233.704525203
 1647694.9921824696303.6076618731647585.74581817 696369.73046127
1647433.37588909696533.600007623
#Sta/Elev= 30
       0   35.76   84.98   32.38  120.39   32.16  219.53   29.07  233.69   29.25
  247.86   28.32  283.26   27.37  354.08    25.7  396.57   25.64  509.88   23.16
  631.74   17.59  645.87   17.58  667.05   16.57  723.55   15.21  765.92   13.33
  801.23   13.18  836.54   11.74  857.73   11.88  871.85    9.46  878.91     8.7
  893.04    9.71  914.22   11.02  949.54   11.57 1020.16   15.17 1062.48   17.86
 1078.84   20.52 1087.02   21.22 1201.11   23.98 1344.49   29.49 1405.76    32.4
#Mann= 3 , 0 , 0
       0      .1       0  871.85     .04       0  893.04      .1       0
Bank Sta=871.85,893.04
XS Rating Curve= 0 ,0
Exp/Cntr=0.3,0.1

Type RM Length L Ch R = 1 ,11001.41,336.07,316.22,218.53
XS GIS Cut Line= 6
1648362.91027337695068.5768657031647943.02293158695678.013350338
1647818.25640717695854.3660338521647779.86670737695921.548008561
1647630.71542959696132.5637155621647393.12722859696490.476442799
#Sta/Elev= 30
       0   39.18      17   39.58   85.01   37.98  204.01   34.57  246.52   32.27
  289.02   31.99  399.53   29.16  433.53   29.42  484.53   27.38  561.04    27.3
  671.55   24.58  782.95   18.38  860.13   11.41  945.87   11.34  964.17   10.45
  972.23    8.79  988.35    7.92 1001.38    8.95 1028.66   10.91 1093.49   11.22
 1110.63   14.93  1119.2   15.92 1144.92   17.33 1170.63   20.08 1230.64   23.39
 1308.69   25.39 1384.31    23.3 1476.73   24.29 1619.56   27.45 1721.48   32.09
#Mann= 3 , 0 , 0
       0      .1       0  972.23     .04       0 1001.38      .1       0
Bank Sta=972.23,1001.38
XS Rating Curve= 0 ,0
Exp/Cntr=0.3,0.1

Type RM Length L Ch R = 1 ,10685.19,471.35,679.74,409.81
XS GIS Cut Line= 6
1647635.90533307695384.0922110831647641.22180136695603.461924344
1647631.77591467695685.1013733891647582.01800275695992.090368852
1647485.12416689696148.3628284781647332.75423783696404.229313135
#Sta/Elev= 30
       0   34.75   42.01   28.83   91.03   20.38  126.04   16.08  161.05   12.78
  219.43    10.5  239.43    8.34  247.62    7.94  261.71    8.21   289.9   10.33
  322.89   10.69  351.26     9.5  372.53   10.65  386.71   10.67  407.99   12.04
  443.44   12.89  500.18   12.49  549.82   13.34  592.36   16.21  612.61   17.05
  629.09   19.27  662.03   20.85  686.74   22.78  785.58      27  845.37   26.52
  926.84   27.66  943.14   28.49  992.02   29.12 1024.61   30.95 1094.29   32.18
#Mann= 3 , 0 , 0
       0      .1       0  239.43     .04       0  261.71      .1       0
Bank Sta=239.43,261.71
XS Rating Curve= 0 ,0
Exp/Cntr=0.3,0.1

Type RM Length L Ch R = 1 ,10005.45,260.68,363.4,360.89
XS GIS Cut Line= 6
1647347.12875944695326.1401923891647272.38124706695665.378902376
1647246.50710817 695826.373544411647249.38201249695918.370482713
1647278.13105571696194.3612976371647260.88162978696415.728930429
#Sta/Elev= 30
       0   35.92   93.18   32.99  114.69   31.92  164.86   28.17  250.88   24.63
  354.47   15.15  382.83   13.34  439.54   11.62  474.99    9.95  489.17   10.08
  524.44    8.88  531.45    9.23  566.46    8.58  602.48    9.05  616.69    8.47
   630.9     7.2  645.11    8.43  652.21    9.58  669.59   14.63  683.64   16.76
  704.71   17.27  725.78   16.26  767.92   16.01  817.09   18.34  866.25   19.33
   922.3   21.97  950.38   22.37  985.49   24.02 1020.59   26.44 1102.21   33.61
#Mann= 3 , 0 , 0
       0      .1       0  616.69     .04       0  645.11      .1       0
Bank Sta=616.69,645.11
XS Rating Curve= 0 ,0
Exp/Cntr=0.3,0.1

Type RM Length L Ch R = 1 ,9642.049,336.1,361.46,356.44
XS GIS Cut Line= 2
1647232.13258655695268.6421059521646648.52700919696631.346754581
#Sta/Elev= 30
       0   35.96    53.3   33.76   152.3   31.38  236.06   27.49  327.44   20.24
  418.82   16.13  449.28   13.12  472.13   11.88  487.36    9.98  578.74    7.73
  692.96     6.7  723.42    7.78  769.11       8   780.2     6.9  791.95    5.34
  801.67    6.95  822.41   13.81  830.03   14.74  890.95   18.94  959.48   22.55
  974.71   22.76  997.56   24.48 1028.02   25.51 1066.09   25.64 1111.78   23.49
 1149.86    23.4 1233.62   24.77 1332.62   31.31 1446.84   35.81 1482.42    36.5
#Mann= 3 , 0 , 0
       0      .1       0   780.2     .04       0  801.67      .1       0
Bank Sta=780.2,801.67
XS Rating Curve= 0 ,0
Exp/Cntr=0.5,0.3

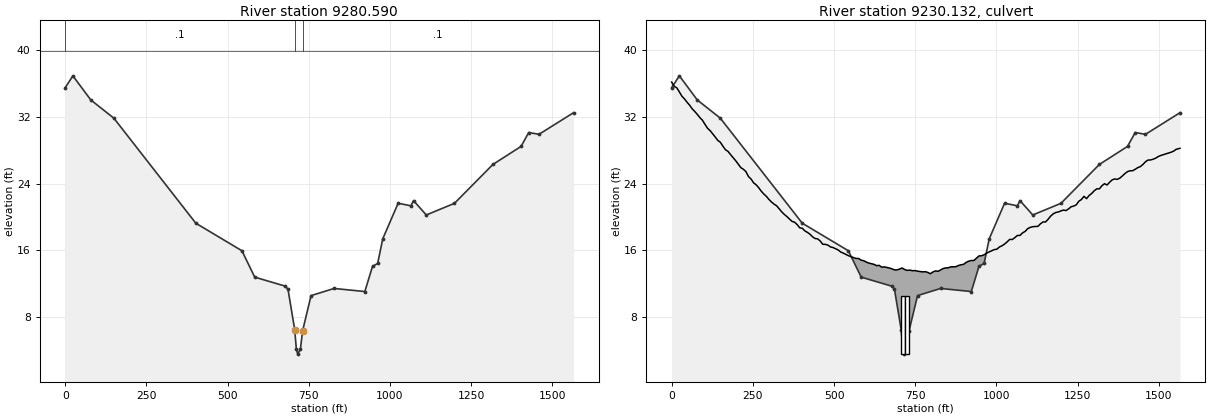
Type RM Length L Ch R = 1 ,9280.590,100.03,101.5,100.15
BEGIN DESCRIPTION:
Center of channel lowered 1 ft based on bridge survey info.
END DESCRIPTION:
XS GIS Cut Line= 2
1646981.81224218695140.8865432441646260.94359875696530.302718952
#Sta/Elev= 30
       0   35.51   23.66   36.94   78.86   34.04  149.84   31.85  402.19   19.23
  544.14   15.92  583.57   12.75   678.2   11.66  686.09   11.28  706.73    6.43
  711.74    4.11  715.86     3.5  724.31    4.11  730.99     6.3  757.06   10.53
  828.04   11.39  922.67   11.02  946.33   14.05   962.1   14.39  977.87   17.36
 1025.19   21.63 1064.62   21.32  1072.5   21.95 1111.93   20.22 1198.68   21.62
 1316.97   26.29 1403.72   28.46 1427.38   30.13 1458.92   29.91 1565.29   32.51
#Mann= 3 , 0 , 0
       0      .1       0  706.73     .04       0  730.99      .1       0
Bank Sta=706.73,730.99
XS Rating Curve= 0 ,0
Exp/Cntr=0.5,0.3

Type RM Length L Ch R = 2 ,9230.132,,,
BEGIN DESCRIPTION:
Augustine Herman Highway, MDE Bridge #: CE051007PF-2
Top of road obtained from DEM.
Opening from MDE2 bridge/culvert surveys.
END DESCRIPTION:
Bridge Culvert--1,0,-1,-1, 0
Deck Dist Width WeirC Skew NumUp NumDn MinLoCord MaxHiCord MaxSubmerge Is_Ogee
27,47,2.6,0, 199, 199, , , 0.95, 0, 2,2,,
       0    7.89   15.77   23.66   31.54   39.43   47.32    55.2   63.09   70.97
   78.86   86.75   94.63  102.52   110.4  118.29  126.18  134.06  141.95  149.84
  157.72  165.61  173.49  181.38  189.27  197.15  205.04  212.92  220.81   228.7
  236.58  244.47  252.35  260.24  268.13  276.01   283.9  291.78  299.67  307.56
  315.44  323.33  331.21   339.1  346.99  354.87  362.76  370.64  378.53  386.42
   394.3  402.19  410.07  417.96  425.85  433.73  441.62  449.51  457.39  465.28
  473.16  481.05  488.94  496.82  504.71  512.59  520.48  528.37  536.25  544.14
  552.02  559.91   567.8  575.68  583.57  591.45  599.34  607.23  615.11     623
  630.88  638.77  646.66  654.54  662.43  670.31   678.2  686.09  693.97  701.86
  709.74  717.63  725.52   733.4  741.29  749.17  757.06  764.95  772.83  780.72
  788.61  796.49  804.38  812.26  820.15  828.04  835.92  843.81  851.69  859.58
  867.47  875.35  883.24  891.12  899.01   906.9  914.78  922.67  930.55  938.44
  946.33  954.21   962.1  969.98  977.87  985.76  993.64 1001.53 1009.41  1017.3
 1025.19 1033.07 1040.96 1048.84 1056.73 1064.62  1072.5 1080.39 1088.28 1096.16
 1104.05 1111.93 1119.82 1127.71 1135.59 1143.48 1151.36 1159.25 1167.14 1175.02
 1182.91 1190.79 1198.68 1206.57 1214.45 1222.34 1230.23 1238.11    1246 1253.88
 1261.77 1269.66 1277.54 1285.43 1293.31  1301.2 1309.09 1316.97 1324.86 1332.74
 1340.63 1348.52  1356.4 1364.29 1372.18 1380.06 1387.95 1395.83 1403.72 1411.61
 1419.49 1427.38 1435.26 1443.15 1451.04 1458.92 1466.81 1474.69 1482.58 1490.47
 1498.35 1506.24 1514.13 1522.01  1529.9 1537.78 1545.67 1553.56 1565.29
   36.19   35.67    35.5   35.01   34.49   34.17   33.77   33.41   32.98   32.66
   32.31   31.92   31.61   31.11   30.64   30.36   29.98   29.59   29.18   28.96
   28.49   28.06   27.86   27.47   27.11   26.74   26.33   25.91   25.71   25.43
   24.83   24.54   24.08   23.84   23.49   23.07   22.73   22.45   22.08   21.77
   21.52   21.32   20.95   20.59   20.28   20.03   19.73   19.45   19.35   19.06
   18.68   18.62   18.31   18.13   17.91    17.6   17.39   17.35   17.09    16.7
   16.69    16.6   16.38   16.31   16.17   16.02   15.77   15.64   15.48   15.33
   15.21    15.1      15   14.99   14.79   14.72   14.56   14.44   14.37   14.29
   14.13   14.17   13.95   13.98   13.91   13.85   13.75   13.62   13.62   13.72
   13.85   13.66   13.56    13.6   13.52   13.54   13.47   13.42   13.38   13.41
   13.32   13.16   13.37    13.5   13.45   13.61   13.78   13.86   13.87   13.99
   13.99   14.01   14.15   14.24   14.29   14.53   14.67   14.75   14.75   15.02
    15.3   15.32   15.44   15.64   15.79   15.92   16.06   16.11   16.38   16.52
   16.73   16.99   17.29   17.27    17.5   17.76   17.76   18.07   18.24   18.57
   18.73   18.81   18.84   18.85   19.16   19.38   19.38   19.71   20.09   20.36
   20.52   20.58   20.71   20.81   20.75   20.96   21.21   21.29   21.44   21.88
   22.08   22.46   22.18   22.56    22.8   23.13   23.36   23.36   23.73   23.98
   23.82   24.15   24.44   24.55    24.5   24.65   24.91    25.2   25.43   25.53
   25.54   25.71   25.91   26.03   26.29   26.61   26.82   26.83   26.92   27.05
   27.24   27.37   27.47   27.58   27.66   27.76   27.89   28.11   28.23
                                                                                
                                                                                
                                                                                
                                                                                
                                                                                
                                                                                
                                                                                
                                                                                
                                                                                
                                                                                
                                                                                
                                                                                
                                                                                
                                                                                
                                                                                
                                                                                
                                                                                
                                                                                
                                                                                
                                                                        
       0    7.89   15.77   23.66   31.54   39.43   47.32    55.2   63.09   70.97
   78.86   86.75   94.63  102.52   110.4  118.29  126.18  134.06  141.95  149.84
  157.72  165.61  173.49  181.38  189.27  197.15  205.04  212.92  220.81   228.7
  236.58  244.47  252.35  260.24  268.13  276.01   283.9  291.78  299.67  307.56
  315.44  323.33  331.21   339.1  346.99  354.87  362.76  370.64  378.53  386.42
   394.3  402.19  410.07  417.96  425.85  433.73  441.62  449.51  457.39  465.28
  473.16  481.05  488.94  496.82  504.71  512.59  520.48  528.37  536.25  544.14
  552.02  559.91   567.8  575.68  583.57  591.45  599.34  607.23  615.11     623
  630.88  638.77  646.66  654.54  662.43  670.31   678.2  686.09  693.97  701.86
  709.74  717.63  725.52   733.4  741.29  749.17  757.06  764.95  772.83  780.72
  788.61  796.49  804.38  812.26  820.15  828.04  835.92  843.81  851.69  859.58
  867.47  875.35  883.24  891.12  899.01   906.9  914.78  922.67  930.55  938.44
  946.33  954.21   962.1  969.98  977.87  985.76  993.64 1001.53 1009.41  1017.3
 1025.19 1033.07 1040.96 1048.84 1056.73 1064.62  1072.5 1080.39 1088.28 1096.16
 1104.05 1111.93 1119.82 1127.71 1135.59 1143.48 1151.36 1159.25 1167.14 1175.02
 1182.91 1190.79 1198.68 1206.57 1214.45 1222.34 1230.23 1238.11    1246 1253.88
 1261.77 1269.66 1277.54 1285.43 1293.31  1301.2 1309.09 1316.97 1324.86 1332.74
 1340.63 1348.52  1356.4 1364.29 1372.18 1380.06 1387.95 1395.83 1403.72 1411.61
 1419.49 1427.38 1435.26 1443.15 1451.04 1458.92 1466.81 1474.69 1482.58 1490.47
 1498.35 1506.24 1514.13 1522.01  1529.9 1537.78 1545.67 1553.56 1565.29
   36.19   35.67    35.5   35.01   34.49   34.17   33.77   33.41   32.98   32.66
   32.31   31.92   31.61   31.11   30.64   30.36   29.98   29.59   29.18   28.96
   28.49   28.06   27.86   27.47   27.11   26.74   26.33   25.91   25.71   25.43
   24.83   24.54   24.08   23.84   23.49   23.07   22.73   22.45   22.08   21.77
   21.52   21.32   20.95   20.59   20.28   20.03   19.73   19.45   19.35   19.06
   18.68   18.62   18.31   18.13   17.91    17.6   17.39   17.35   17.09    16.7
   16.69    16.6   16.38   16.31   16.17   16.02   15.77   15.64   15.48   15.33
   15.21    15.1      15   14.99   14.79   14.72   14.56   14.44   14.37   14.29
   14.13   14.17   13.95   13.98   13.91   13.85   13.75   13.62   13.62   13.72
   13.85   13.66   13.56    13.6   13.52   13.54   13.47   13.42   13.38   13.41
   13.32   13.16   13.37    13.5   13.45   13.61   13.78   13.86   13.87   13.99
   13.99   14.01   14.15   14.24   14.29   14.53   14.67   14.75   14.75   15.02
    15.3   15.32   15.44   15.64   15.79   15.92   16.06   16.11   16.38   16.52
   16.73   16.99   17.29   17.27    17.5   17.76   17.76   18.07   18.24   18.57
   18.73   18.81   18.84   18.85   19.16   19.38   19.38   19.71   20.09   20.36
   20.52   20.58   20.71   20.81   20.75   20.96   21.21   21.29   21.44   21.88
   22.08   22.46   22.18   22.56    22.8   23.13   23.36   23.36   23.73   23.98
   23.82   24.15   24.44   24.55    24.5   24.65   24.91    25.2   25.43   25.53
   25.54   25.71   25.91   26.03   26.29   26.61   26.82   26.83   26.92   27.05
   27.24   27.37   27.47   27.58   27.66   27.76   27.89   28.11   28.23
                                                                                
                                                                                
                                                                                
                                                                                
                                                                                
                                                                                
                                                                                
                                                                                
                                                                                
                                                                                
                                                                                
                                                                                
                                                                                
                                                                                
                                                                                
                                                                                
                                                                                
                                                                                
                                                                                
                                                                        
BR Coef=-1 , 1 , 0 ,, 0 ,,,0.8,0,0.5,0,
WSPro=,,,, 1 ,,,, 0 ,,,, 0 ,,,,-1 ,-1 ,-1 , 0 , 0 , 0 , 0 , 0
Multiple Barrel Culv=2,7,12,52,0.013,0.4,1,8,1,3.5,3.5, 2,Culvert #1  , 0 ,25
     712     707     725     720
Culvert Bottom n=0.013
BC Design=,, 0 ,, 0 ,,,,,,
BC Use User HTab Curves=0
BC User HTab FreeFlow(D)= 0