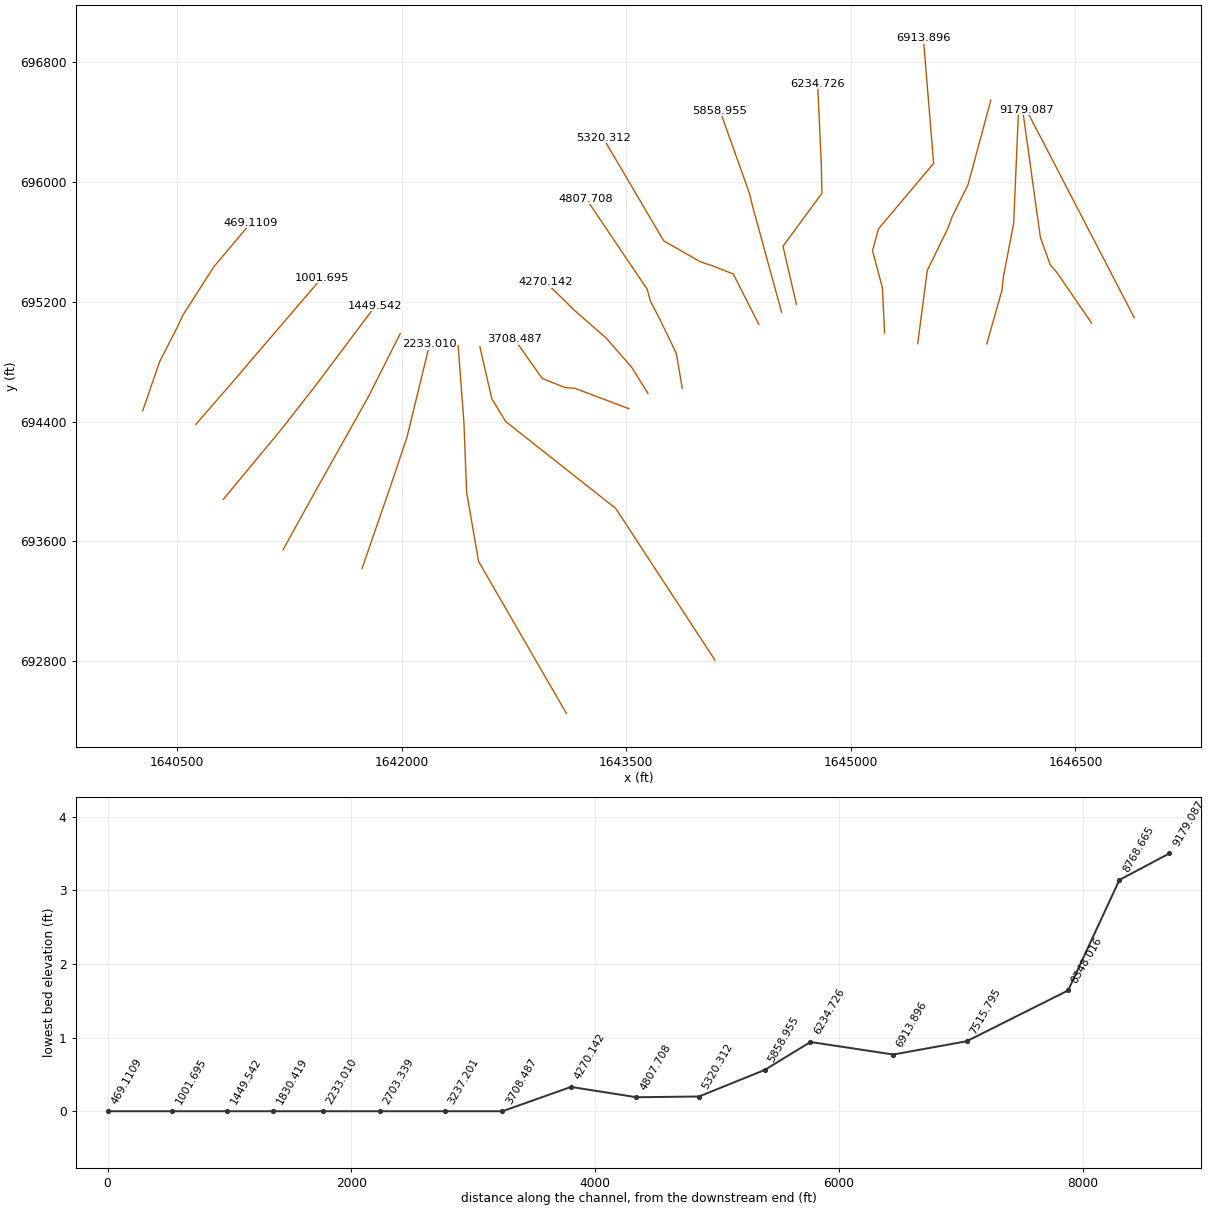
HEC-RAS study PerchCreek.prj: PerchCreek

--- PerchCreek.g01 (geometry) --- (continued)

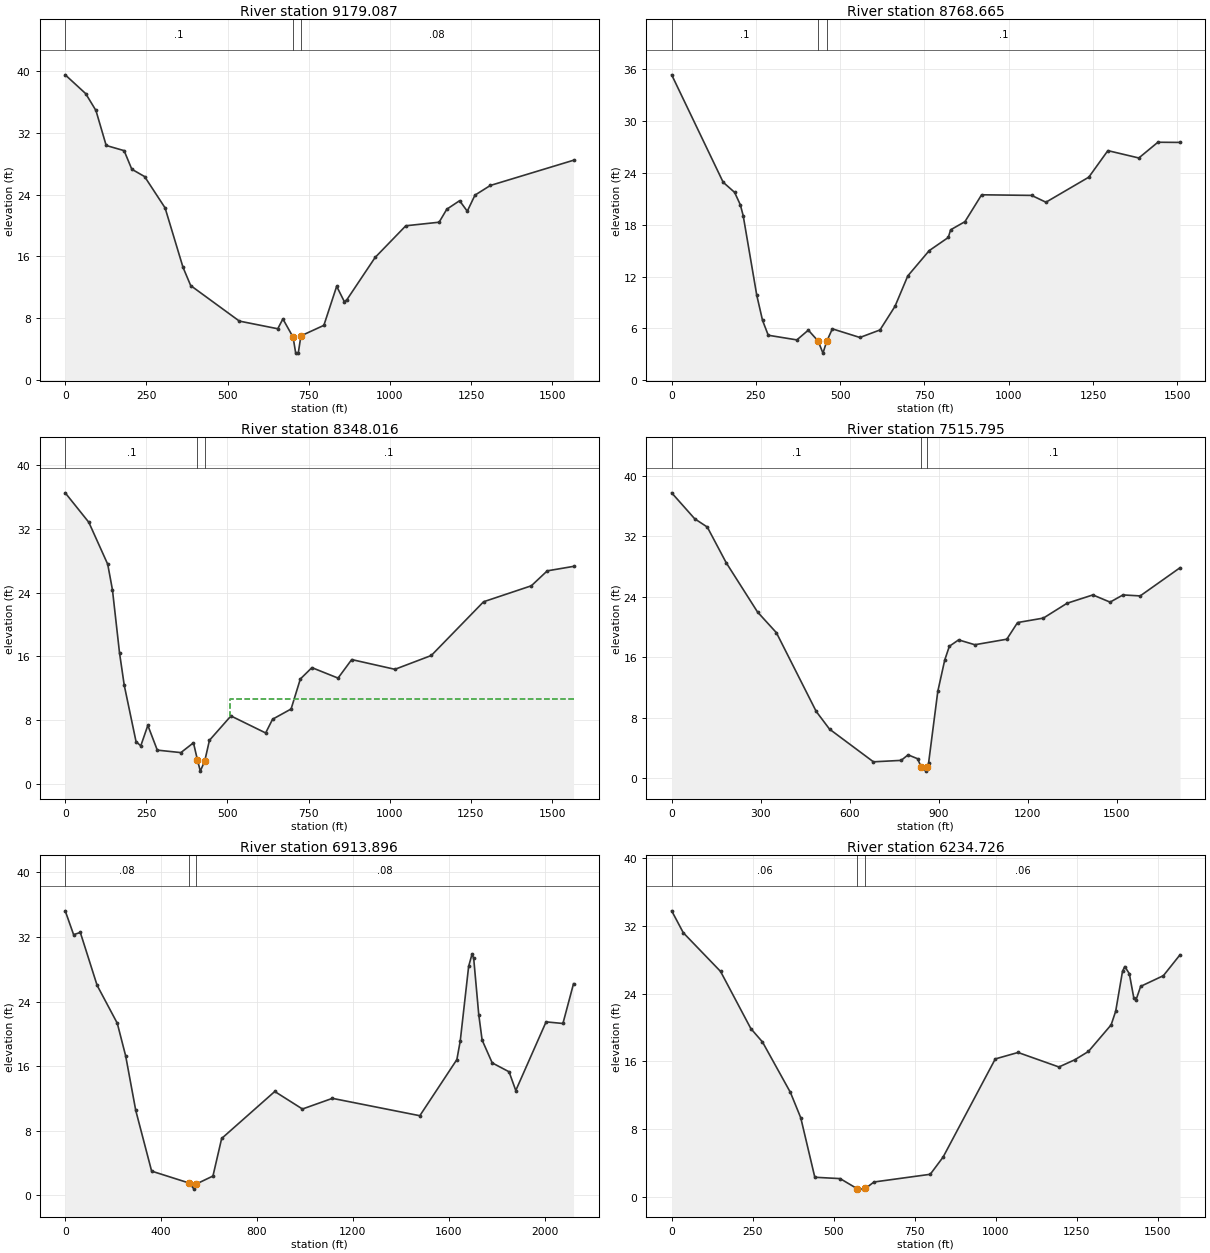
Type RM Length L Ch R = 1 ,9179.087,374.91,410.42,352.79
BEGIN DESCRIPTION:
Center of channel lowered 1 ft based on bridge survey info.
END DESCRIPTION:
XS GIS Cut Line= 2
1646893.04803398695094.8331465271646172.17939056 696484.24932225
#Sta/Elev= 30
       0   39.47   63.09   37.04   94.63   34.86  126.18   30.34  181.38   29.67
  205.04   27.27  244.47   26.32  307.56   22.27  362.76   14.59  386.42   12.23
  536.25    7.64  654.54    6.65  670.31    7.92  701.72    5.56  709.74     3.5
  717.63     3.5  725.83    5.73  796.49    7.09  835.92   12.14  859.58   10.15
  867.47   10.41  954.21   15.86 1048.84   19.96 1151.36   20.42 1175.02    22.1
 1214.45    23.2 1238.11   21.84 1261.77   23.92 1309.09   25.17 1565.29   28.43
#Mann= 3 , 0 , 0
       0      .1       0  701.72     .04       0  725.83     .08       0
Bank Sta=701.72,725.83
XS Rating Curve= 0 ,0
Exp/Cntr=0.5,0.3

Type RM Length L Ch R = 1 ,8768.665,455.1,420.65,341.64
XS GIS Cut Line= 6
1646608.27834868695058.7740904391646470.28294122695260.017392978
 1646375.4110986 695398.012800441646332.28753378695446.886173904
1646266.16473436695630.8800505251646151.16856149696458.852495253
#Sta/Elev= 30
       0   35.34  152.78   22.91  186.73   21.74   203.7    20.3  212.19   19.04
  252.51    9.82   269.5    6.94  286.49    5.21  371.43    4.67  405.41     5.8
  434.48    4.54  448.81    3.14  459.97     4.5  476.65    5.95  558.47    4.95
  617.98    5.82  662.61    8.56  700.44   12.07  764.04      15  820.58   16.52
  827.64   17.41  870.05   18.35  919.52   21.46 1067.93   21.39 1110.33    20.6
 1237.54    23.5 1294.08   26.57 1385.95   25.72 1442.49   27.54 1508.08   27.52
#Mann= 3 , 0 , 0
       0      .1       0  434.48     .04       0  459.97      .1       0
Bank Sta=434.48,459.97
XS Rating Curve= 0 ,0
Exp/Cntr=0.3,0.1

Type RM Length L Ch R = 1 ,8348.016,646.17,832.22,554.52
XS GIS Cut Line= 5
1645908.44828406694920.2023136021646010.29824971 695280.14172323
1646018.92296267695366.388852894 1646087.9206664695725.751893148
1646119.54461394696464.602303922
#Sta/Elev= 30
       0   36.49   72.75    32.8  130.95   27.55   145.5   24.36  167.32   16.46
  181.87    12.4  218.25    5.34  232.79     4.8  254.62    7.37  283.72    4.27
  356.47    3.96  395.18    5.19  407.49    3.03  416.28    1.64  429.92    2.91
  444.42     5.5  510.64    8.55  617.56    6.42  638.95    8.14  695.97    9.42
  724.48   13.18  760.12    14.6  840.69   13.29  882.73   15.61 1015.85   14.39
 1127.95   16.12  1289.1   22.85 1436.24   24.85 1485.28   26.72 1566.21   27.28
#Mann= 3 , 0 , 0
       0      .1       0  407.49     .04       0  429.92      .1       0
#XS Ineff= 2 , 0
                           506.6           10.68
Permanent Ineff=
       F       F
Bank Sta=407.49,429.92
XS Rating Curve= 0 ,0
Exp/Cntr=0.3,0.1

Type RM Length L Ch R = 1 ,7515.795,468.83,601.9,573.39
XS GIS Cut Line= 6
1645446.81700259694920.7786829771645510.78076489695409.674907014
1645648.06030513695691.2530412821645676.80934836695768.875457972
1645783.18080826695984.4932821241645935.55073734696547.974529237
#Sta/Elev= 30
       0   37.72   77.66   34.29  120.01    33.2  183.55    28.5  289.45   21.97
  352.98   19.24  487.12    8.84     532     6.5  679.97    2.18  773.42    2.37
  796.78     3.1  828.72    2.59  840.62    1.53  858.58     .95  862.11    1.48
  866.04    2.06   896.9   11.48  920.32   15.63  935.93   17.45  967.15   18.29
 1021.79   17.65 1129.53   18.38 1165.78   20.58  1252.8   21.17 1332.57   23.13
 1419.58   24.23  1477.6   23.28  1521.1   24.23 1579.12    24.1 1713.25   27.82
#Mann= 3 , 0 , 0
       0      .1       0  840.62     .04       0  862.11      .1       0
Bank Sta=840.62,862.11
XS Rating Curve= 0 ,0
Exp/Cntr=0.3,0.1

Type RM Length L Ch R = 1 ,6913.896,736.43,679.17,486.34
XS GIS Cut Line= 6
 1645225.4493698694992.6512910281645211.07484819695294.516244844
1645144.95204878695541.7580165421645185.20070928695688.378136963
1645553.18846251696125.3635939061645484.70636843696960.486553937
#Sta/Elev= 30
       0   35.23   35.04   32.28   63.07   32.55  133.15      26  217.25   21.31
  252.29   17.26  294.33   10.51  360.52       3  516.41    1.53  537.86     .77
  545.01    1.38  616.36    2.39  652.66    7.04  874.27   12.86  989.73   10.69
 1114.65   12.01 1479.46    9.86 1633.98   16.81 1648.03    19.1 1683.14   28.35
 1697.19   29.86 1704.21   29.34 1725.28   22.39 1739.33   19.23 1781.47    16.4
 1851.71    15.3  1879.8   12.98 2006.22   21.48 2076.46   21.28 2120.73   26.21
#Mann= 3 , 0 , 0
       0     .08       0  516.41    .035       0  545.01     .08       0
Bank Sta=516.41,545.01
XS Rating Curve= 0 ,0
Exp/Cntr=0.3,0.1

Type RM Length L Ch R = 1 ,6234.726,286.5,375.77,460.13
XS GIS Cut Line= 5
1644636.55463429695183.6554683741644546.99976243695571.726580024
 1644807.1353427695925.6815499221644802.87082499696121.849364594
1644778.21148279696656.080397412
#Sta/Elev= 30
       0   33.77   35.92   31.18  150.86   26.62  244.26   19.88  280.17    18.3
  366.38   12.35  398.27    9.36  441.71    2.34  519.89    2.18  572.01       1
  589.39     .94  598.07    1.02  624.14    1.78  797.88    2.69  837.54    4.72
  998.57    16.3 1068.79   17.06 1194.92   15.35 1243.97    16.2 1286.02   17.18
 1356.09   20.32 1370.11   21.93 1391.13   26.63 1398.14    27.2 1412.15   26.36
 1426.17   23.46 1433.17    23.3 1447.19   24.86 1517.26   26.12 1568.55   28.58
#Mann= 3 , 0 , 0
       0     .06       0  572.01    .035       0  598.07     .06       0
Bank Sta=572.01,598.07
XS Rating Curve= 0 ,0
Exp/Cntr=0.3,0.1

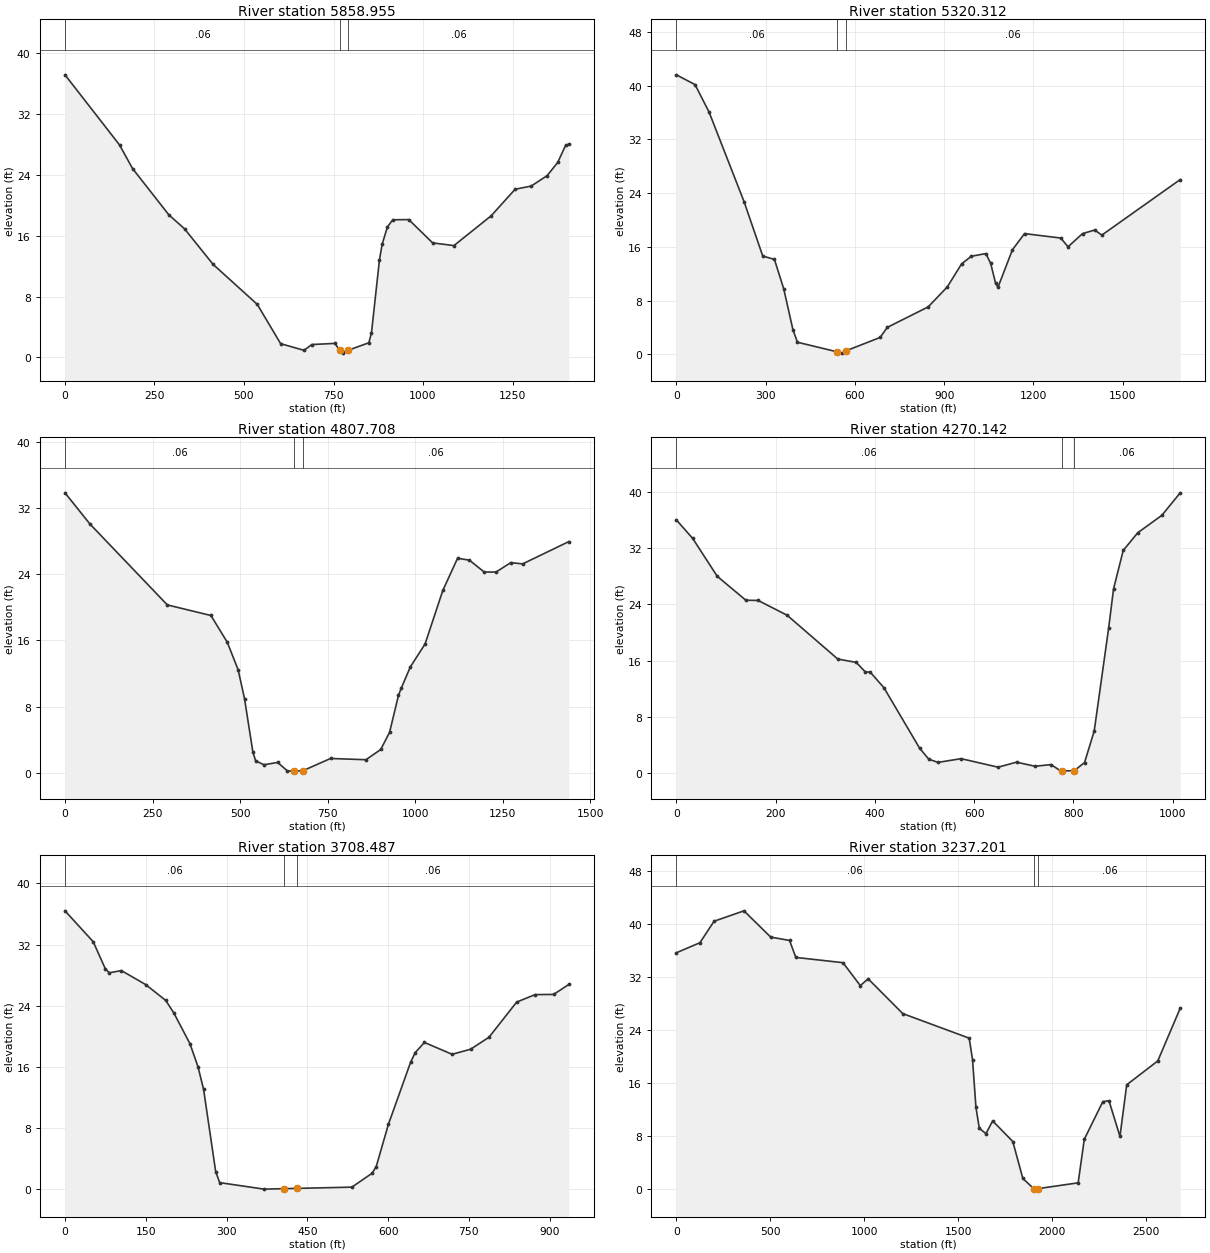
Type RM Length L Ch R = 1 ,5858.955,444.4,538.64,596.67
XS GIS Cut Line= 4
1644537.41258284695131.7779270411644342.04743759695845.087875918
1644323.87393573695922.3252589111644126.23710273696476.617066309
#Sta/Elev= 30
       0   37.15  152.41   27.93   188.7   24.83  290.31   18.73  333.86   16.91
  413.69   12.23  537.08    6.97   602.4     1.8  667.72     .93  689.49    1.69
  753.96    1.84  767.31     .92  775.54     .56  789.92     .92  848.65    1.92
  856.09    3.23  878.38   12.83  885.81   14.86  900.68   17.16  915.54   18.09
  960.13   18.12 1027.01   15.05 1086.47    14.7 1190.51   18.62 1257.39   22.11
 1301.98   22.52 1346.57   23.89  1376.3   25.63  1398.6   27.91  1407.4   28.01
#Mann= 3 , 0 , 0
       0     .06       0  767.31    .035       0  789.92     .06       0
Bank Sta=767.31,789.92
XS Rating Curve= 0 ,0
Exp/Cntr=0.3,0.1

Type RM Length L Ch R = 1 ,5320.312,547.95,512.6,406.28
XS GIS Cut Line= 6
1644385.20950454695049.9971685711644214.83292443695386.206953406
1644076.25997256695440.7274590581643994.47921409695467.987711877
1643749.86510293695608.1707382051643344.77652183696297.153735235
#Sta/Elev= 30
       0    41.6   62.78   40.15  109.87   36.07  227.58   22.73  290.36   14.64
   329.6   14.14  360.99    9.74  391.96    3.65     407    1.82  540.59     .39
  556.28      .2  570.43     .55  684.64    2.53  708.85    4.03     846    7.07
  910.21   10.03  958.93    13.5  991.41   14.61 1040.13   15.01 1056.37   13.54
 1072.61   10.62 1080.73    9.99 1129.45   15.58 1170.06   17.98 1291.86   17.32
 1316.22   16.02 1364.94   17.98 1405.54   18.51  1429.9   17.76 1693.21   26.02
#Mann= 3 , 0 , 0
       0     .06       0  540.59    .035       0  570.43     .06       0
Bank Sta=540.59,570.43
XS Rating Curve= 0 ,0
Exp/Cntr=0.3,0.1

Type RM Length L Ch R = 1 ,4807.708,452.68,537.57,543.69
XS GIS Cut Line= 6
1643874.07976414 694622.919874371643834.08736259694857.357858911
1643717.33331043695097.7026110291643660.54111703695206.743622303
1643640.09592742695283.9810053261643231.19213505 695890.52163063
#Sta/Elev= 30
       0   33.86   71.01    30.1   292.3    20.3  416.82   19.02  463.51   15.79
  494.64   12.45  512.92    8.94   536.6    2.53  544.49    1.44  568.17     .96
  607.63    1.24  635.21     .22  655.34     .19  679.67     .24  758.52    1.72
  859.83    1.57  902.04    2.81  927.36     4.9  952.69    9.37  961.13   10.28
  986.46   12.79 1028.67   15.58 1079.32   22.05 1121.53   25.95  1155.3   25.71
 1197.51   24.28 1231.28   24.27 1273.49   25.42 1307.26   25.26 1439.37   27.96
#Mann= 3 , 0 , 0
       0     .06       0  655.34    .035       0  679.67     .06       0
Bank Sta=655.34,679.67
XS Rating Curve= 0 ,0
Exp/Cntr=0.3,0.1

Type RM Length L Ch R = 1 ,4270.142,449.86,561.66,566.98
XS GIS Cut Line= 6
1643644.63930291694588.8445583431643536.73438326 694762.77427417
1643367.49339917 694956.857971431643147.13968883695149.951428935
1643099.43424641695197.6568713641642960.86129455695331.686447755
#Sta/Elev= 30
       0   35.98   32.95   33.35   82.38   27.98  140.04   24.58  164.75   24.55
  223.26   22.45  325.42   16.23  362.57   15.76  381.15   14.38  390.43    14.4
   418.3   12.17  490.11     3.6  508.73    2.02  527.34    1.57  573.88     2.1
  648.34     .89  685.57     1.6   722.8    1.02  755.18    1.26  774.98     .33
  777.72     .36  801.78     .39  822.64    1.55  842.12    6.02  871.34    20.7
  881.07   26.19  900.55   31.64  929.77   34.15  978.46   36.63 1015.43   39.82
#Mann= 3 , 0 , 0
       0     .06       0  777.72    .035       0  801.78     .06       0
Bank Sta=777.72,801.78
XS Rating Curve= 0 ,0
Exp/Cntr=0.3,0.1

Type RM Length L Ch R = 1 ,3708.487,499.77,471.29,416.51
XS GIS Cut Line= 6
1643517.42478968694486.6186102481643276.62588975694577.486119643
 1643156.2264398 694622.91987437 1643092.6191832694627.463249817
 1642938.1444172694688.7988186931642754.13771065694950.042908236
#Sta/Elev= 30
       0   36.41   52.37   32.37   74.82   28.84    82.3    28.3  104.75   28.59
  149.64   26.77  187.05   24.69  202.01   23.06  231.94   19.04   246.9   16.03
  257.37   13.04  279.82    2.29   287.3     .85   369.6       0  406.88   .0594
  430.93   .0977  532.68     .26  570.33    2.08  577.87    2.95  600.46    8.46
  641.72    16.6  650.28   17.86  667.41   19.19  718.78   17.64  753.03    18.3
  787.28   19.87  838.65   24.47   872.9   25.45  907.15   25.47  935.58   26.78
#Mann= 3 , 0 , 0
       0     .06       0  406.88    .035       0  430.93     .06       0
Bank Sta=406.88,430.93
XS Rating Curve= 0 ,0
Exp/Cntr=0.3,0.1

Type RM Length L Ch R = 1 ,3237.201,615.12,533.86,472.74
XS GIS Cut Line= 5
1644092.16178675692807.8413738911643429.37821116 693820.70531939
1642695.07382952694400.2944763151642601.93463241 694552.49755457
1642522.42556167694900.065778062
#Sta/Elev= 30
       0   35.65  125.48   37.17  200.77   40.41  359.72   41.98  501.93   38.02
  602.32   37.51  635.78   34.95  886.74   34.16  978.76    30.7 1020.59   31.72
 1204.63   26.48 1558.24   22.77 1576.07   19.49 1593.91   12.38 1611.75    9.18
 1647.42    8.37 1683.09   10.29  1790.1    7.18 1843.61    1.61 1902.65     .04
 1906.04       0 1926.78   .0849  2137.9     .95 2170.55    7.52 2269.03   13.19
 2301.85   13.34 2360.27    7.95 2396.18   15.74 2561.34   19.33 2680.92   27.29
#Mann= 3 , 0 , 0
       0     .06       0 1902.65    .035       0 1926.78     .06       0
Bank Sta=1902.65,1926.78
XS Rating Curve= 0 ,0
Exp/Cntr=0.3,0.1

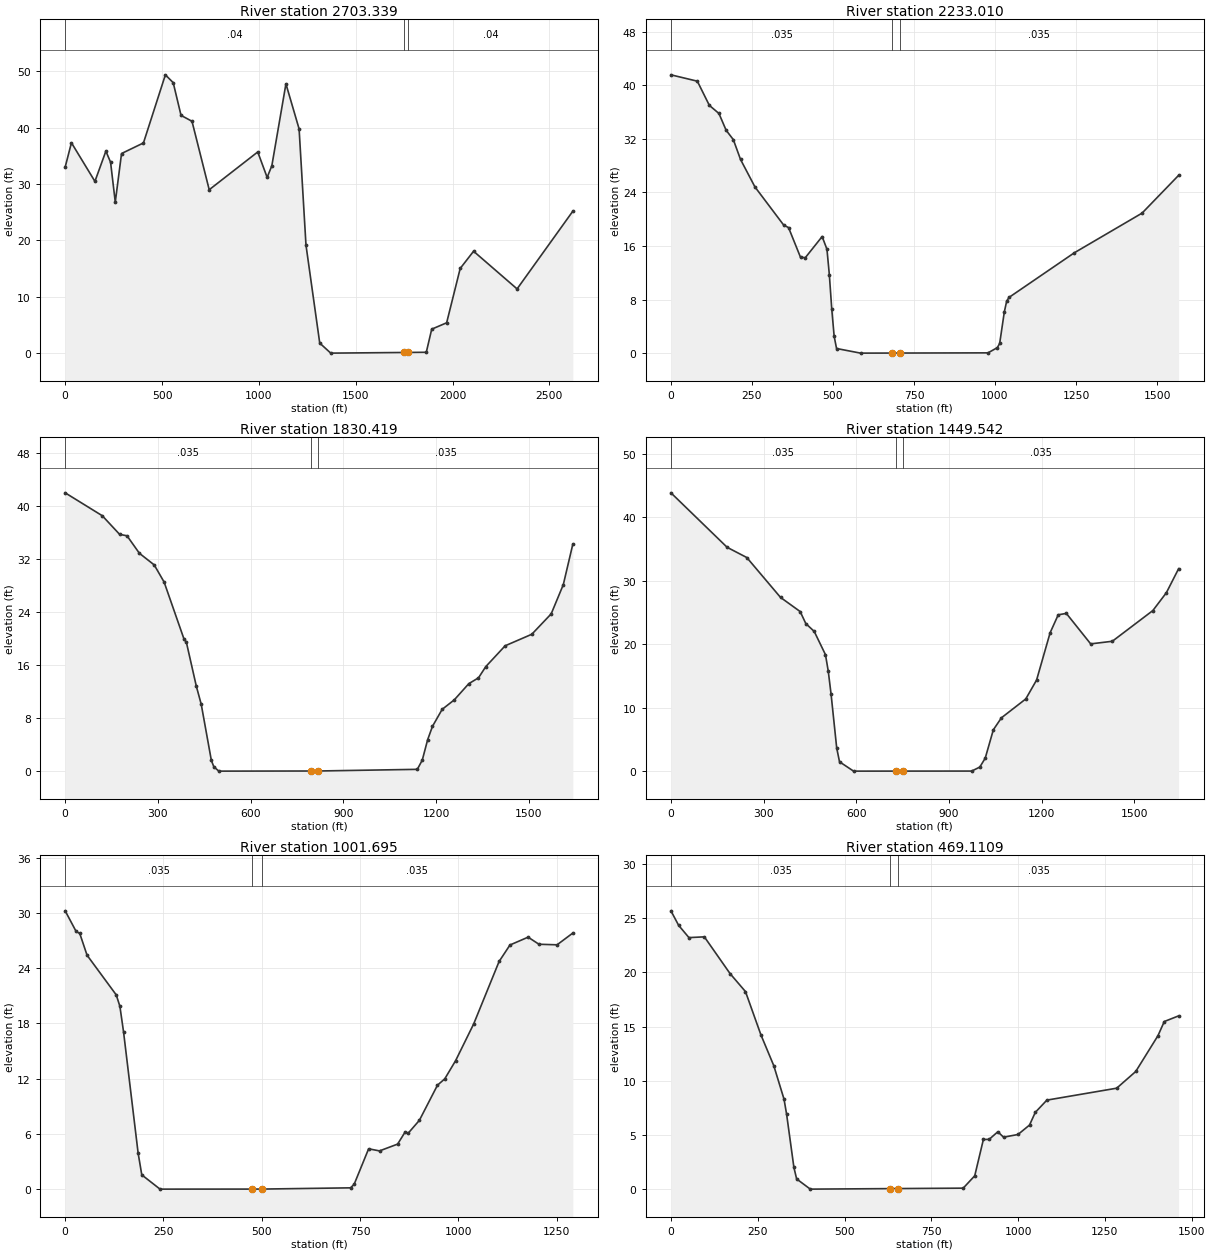
Type RM Length L Ch R = 1 ,2703.339,506.32,470.33,431.2
XS GIS Cut Line= 5
1643099.86314578692451.4703604281642513.59214389693466.582080632
1642433.82973997693927.7834273871642415.65623811694395.751100838
1642377.03754659694906.880841255
#Sta/Elev= 30
       0      33   32.33   37.31  153.59   30.46  210.17   35.83  234.42   33.85
  258.67   26.79  291.01    35.4  404.18   37.28  517.35   49.36  557.77   47.97
  598.18   42.17  654.77   41.12  743.69   28.98  994.28   35.68 1042.78   31.17
 1067.03   33.23 1139.78   47.76 1207.77   39.77 1243.29   19.16 1314.33    1.78
 1371.16       0 1747.82.1145327 1771.93 .121864 1864.46     .15 1892.48    4.25
 1969.54    5.38 2039.59   15.02 2108.61   18.07 2333.25   11.39  2621.2   25.18
#Mann= 3 , 0 , 0
       0     .04       0 1747.82    .035       0 1771.93     .04       0
Bank Sta=1747.82,1771.93
XS Rating Curve= 0 ,0
Exp/Cntr=0.3,0.1

Type RM Length L Ch R = 1 ,2233.010,424.66,402.59,375.83
XS GIS Cut Line= 4
1641734.62627164693417.5255247651641928.06663759 693977.01458323
1642035.20284025694295.4471856361642186.21577686694915.967592195
#Sta/Elev= 30
       0   41.56   81.47   40.61  118.51      37  148.13   35.79  170.35   33.28
  192.57   31.88  214.79   28.92  259.23   24.82  348.11   19.11  362.92   18.75
  399.96    14.3  414.77   14.26  466.61   17.41  481.43   15.51  488.83    11.7
  496.24    6.59  503.65    2.52  511.05     .69  585.12       0  682.56  .00991
  706.69   .0123  978.39     .04  1007.2     .82 1014.41    1.44 1028.82    6.17
 1036.02    7.76 1043.23    8.32 1244.95   14.99 1453.87   20.91 1566.59   26.55
#Mann= 3 , 0 , 0
       0    .035       0  682.56     .03       0  706.69    .035       0
Bank Sta=682.56,706.69
XS Rating Curve= 0 ,0
Exp/Cntr=0.3,0.1

Type RM Length L Ch R = 1 ,1830.419,399.24,380.88,361.67
XS GIS Cut Line= 4
 1641207.8732751693545.4937668591641437.02570863693959.158549443
1641779.26635608694569.2397036251641990.56275582694988.856497467
#Sta/Elev= 30
       0   42.03  120.03   38.57  176.05   35.76  200.06   35.54  240.07    32.9
  288.08   31.14  320.09   28.55  384.11   19.98  392.11   19.45  424.12   12.85
  440.13   10.09  472.89    1.61  480.92     .66  496.97       0  795.33.0188219
  819.31   .0203 1139.07     .27 1155.12    1.66 1172.41    4.73 1188.09    6.76
 1219.44    9.33 1258.63   10.76 1305.65   13.21    1337   14.09 1360.51   15.78
 1423.21   18.93 1509.42   20.67 1572.12   23.75 1611.31   28.16 1642.23    34.3
#Mann= 3 , 0 , 0
       0    .035       0  795.33     .03       0  819.31    .035       0
Bank Sta=795.33,819.31
XS Rating Curve= 0 ,0
Exp/Cntr=0.3,0.1

Type RM Length L Ch R = 1 ,1449.542,452.64,447.85,443.66
XS GIS Cut Line= 4
1640809.08852068693881.7824030821641198.94525823694351.991292626
1641422.14568049694637.6878331151641823.90644053695173.368846521
#Sta/Elev= 30
       0   43.83  181.86   35.25  245.51   33.64  354.63   27.36  418.28   25.13
  436.47   23.24  463.75      22  500.12   18.34  509.21   15.73  518.31   12.09
  536.49    3.63  545.58    1.47  591.05       0   727.5  .00356  751.49  .00419
  973.36     .01  999.61     .64 1017.11    2.04 1043.36    6.51 1069.61     8.4
 1148.36   11.37 1183.36   14.35 1227.11   21.79 1253.36   24.62 1279.61   24.84
 1358.36   20.04 1428.36   20.45 1559.61   25.29 1603.36    28.1 1642.96   31.88
#Mann= 3 , 0 , 0
       0    .035       0   727.5     .03       0  751.49    .035       0
Bank Sta=727.5,751.49
XS Rating Curve= 0 ,0
Exp/Cntr=0.3,0.1

Type RM Length L Ch R = 1 ,1001.695,497.54,532.59,556.43
XS GIS Cut Line= 4
1640624.57617159694381.7513489131640904.32070082694703.159956977
1640984.67285284694798.3921371251641466.78576493695360.857201234
#Sta/Elev= 30
       0   30.22   27.84   27.98   37.12   27.76   55.68    25.4  129.92   21.09
   139.2   19.85  148.48   17.08   185.6    3.91  194.88    1.55  241.28       0
  475.92  .00493  499.94  .00544  725.87     .14  735.09     .52  771.97    4.38
  799.63    4.15  845.73    4.89  864.17    6.16  873.39    6.11  901.04    7.47
  947.14   11.29  965.58   11.97  993.24   13.95 1039.34   17.95 1103.87   24.72
 1131.53   26.51 1177.63   27.36 1205.29   26.59 1251.39   26.53 1291.51   27.81
#Mann= 3 , 0 , 0
       0    .035       0  475.92     .03       0  499.94    .035       0
Bank Sta=475.92,499.94
XS Rating Curve= 0 ,0
Exp/Cntr=0.3,0.1

Type RM Length L Ch R = 1 ,469.1109,446.6,469.11,456.89
XS GIS Cut Line= 6
1640270.43150161694474.0075234471640383.51971555694801.368142754
1640499.58393514 695027.544570641640538.27200831695110.872728288
1640743.61639678695432.281336352 1640993.6008697695729.881899342
#Sta/Elev= 30
       0   25.67   22.22   24.33   51.84    23.2   96.28   23.27  170.34   19.88
  214.77   18.22  259.21   14.23  296.24   11.39  325.86    8.29  333.27     6.9
  354.21    2.01  362.08     .94  401.42       0  630.92.0468867  655.05   .0518
  841.95     .09  875.18    1.23   900.1    4.58  916.71    4.59  941.63    5.29
  958.24    4.79  999.78    5.04    1033    5.91 1049.62    7.08 1082.98    8.21
  1284.1    9.31 1338.95   10.85 1402.94   14.15 1421.23   15.46  1462.5   15.98
#Mann= 3 , 0 , 0
       0    .035       0  630.92     .03       0  655.05    .035       0
Bank Sta=630.92,655.05
XS Rating Curve= 0 ,0
Exp/Cntr=0.3,0.1

Chan Stop Cuts=-1
Use User Specified Reach Order=0
User Specified Reach Order=PerchCreek      ,Reach1