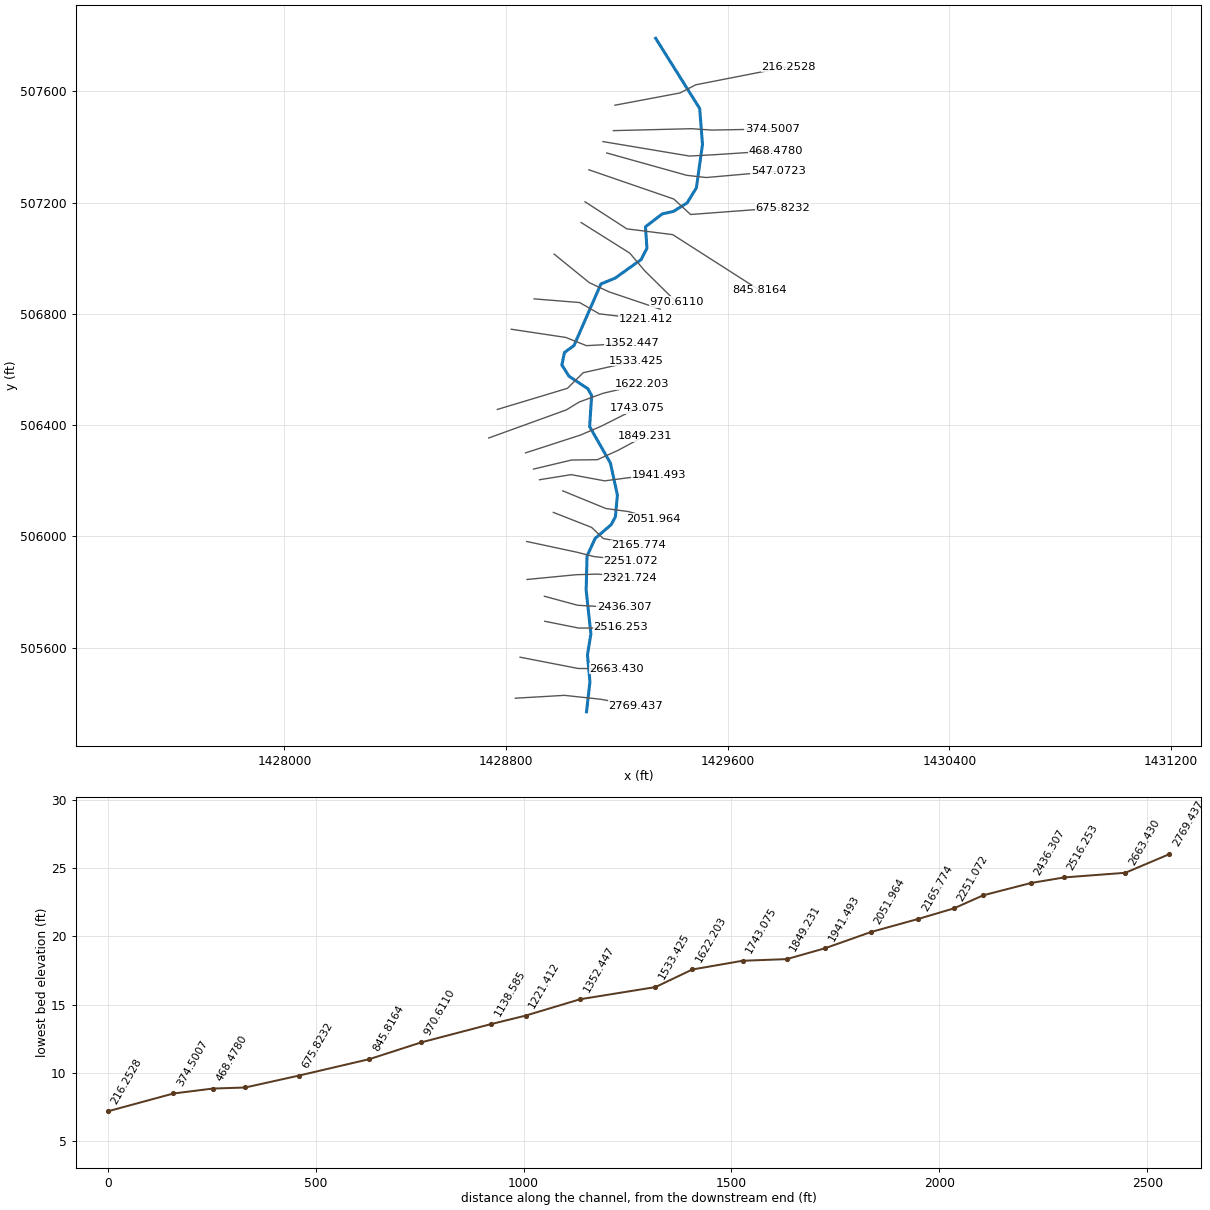
--- PlumCreek.prj (project) ---

Proj Title=PlumCreek
Current Plan=p01
Default Exp/Contr=0.3,0.1
English Units
Geom File=g02
Geom File=g01
Flow File=f01
Plan File=p01
Y Axis Title=Elevation
X Axis Title(PF)=Main Channel Distance
X Axis Title(XS)=Station
BEGIN DESCRIPTION:
Plum Creek  - Georeferenced HEC-RAS model.  This was formerly an approximate method stream.  Projection:  MD Stateplane.  Horizontal datum:  NAD83.  Vertrial datum: NAVD88.  Units:Feet.  Created by: Jodell L. Kormanik-Sonterre, USACE- St Paul District as part of FEMA Map Modernization study for Anne Arundel County, MD.
FLOW FILE:  There was no flow given for Plum Creek Tributary.  Assumed the flow from the trib to be the difference in the flow given at the upstrean end of Plum Creek and the downstream end.
END DESCRIPTION:
DSS Export Rating Curves= 0
DSS Export Rating Curve Sorted= 0
DSS Export Volume Flow Curves= 0
DXF OffsetX= 0
DXF OffsetY= 0
DXF ScaleX= 1
DXF ScaleY= 10

--- PlumCreek.p01 (plan) ---

Plan Title=PlumCreek
Program Version=4.00
Short Identifier=PlumCreek100
Geom File=g01
Flow File=f01
Subcritical Flow
K Sum by GR= 0
Std Step Tol= 0.01
Critical Tol= 0.01
Num of Std Step Trials= 20
Max Error Tol= 0.3
Flow Tol Ratio= 0.001
Split Flow NTrial= 30
Split Flow Tol= 0.02
Split Flow Ratio= 0.02
Log Output Level= 0
Friction Slope Method= 1
Unsteady Friction Slope Method= 2
Unsteady Bridges Friction Slope Method= 1
Parabolic Critical Depth
Global Vel Dist= 0 , 0 , 0
Global Log Level= 0
CheckData=True
Encroach Param=-1 ,0,0, 0
Computation Interval=1HOUR
Output Interval=1HOUR
Run HTab= 0
Run UNet= 0
Run PostProcess= 0
Run WQNet= 0
UNET Theta= 1
UNET Theta Warmup= 1
UNET ZTol= 0.02
UNET ZSATol= 0.05
UNET MxIter= 20
UNET MaxInSteps= 0
UNET DtIC= 0
UNET DtMin= 0
UNET MaxCRTS= 20
UNET WFStab= 2
UNET SFStab= 1
UNET WFX= 1
UNET SFX= 1
UNET DSS MLevel= 4
UNET DZMax Abort= 100
UNET Convert EG Bridges= 0
UNET Use Existing IB Tables=-1
UNET Froude Reduction=False
UNET Froude Limit= 1
UNET Froude Power= 10
UNET Time Slicing=0,0, 5
Instantaneous Interval=1HOUR
Write IC File= 0
Echo Input=False
Echo Output=False
Write Detailed= 0
Detailed Automatic Start=False, 10
WQ ULTIMATE=-1
WQ Max Comp Step=1HOUR
WQ Output Interval=15MIN
WQ Output Selected Increments= 0
WQ Output face flow=0
WQ Output face velocity=0
WQ Output face area=0
WQ Output face dispersion=0
WQ Output cell volume=0
WQ Output cell surface area=0
WQ Output cell continuity=0
WQ Output face conc=0
WQ Output face dconc_dx=0
WQ Output face courant=0
WQ Output face peclet=0
WQ Output face adv mass=0
WQ Output face disp mass=0
WQ Output cell mass=0
WQ Output cell source sink temp=0
WQ Output cell source sink nsm=0
WQ Output MaxMinRange=-1
WQ Daily Max Min Mean=-1
WQ Daily Range=0
WQ Daily Time=0
WQ Create Restart=0
WQ Fixed Restart=0
WQ System Summary=False
Sorting and Armoring Iterations= 10
XS Update Threshold= 0.02
Hydraulics Update Threshold= 0.02
Energy Slope Method= 1
Volume Change Method= 0
XS Weighting Method= 0
Number of US Weighted Cross Sections= 1
Number of DS Weighted Cross Sections= 1
Upstream XS Weight=0.25
Main XS Weight=0.5
Downstream XS Weight=0.25
Number of DS XS's Weighted with US Boundary= 1
Upstream Boundary Weight= 1
Weight of XSs Associated with US Boundary= 0
Number of US XS's Weighted with DS Boundary= 1
Downstream Boundary Weight= 0.5
Weight of XSs Associated with DS Boundary= 0.5
Sediment Output Level= 4
Mass or Volume Output= 0
Output Increment Type= 1
Profile and TS Output Increment= 10
XS Output Flag= 0
XS Output Increment= 10
Disregard all LS=0
Disregard all Conn=0
Disregard all Breaches=0
Disregard all Pumps=0

--- PlumCreek.f01 (steady flow) ---

Flow Title=PlumCreek_100yr
Program Version=4.00
Number of Profiles= 2
Profile Names=100CUR,100ULT
River Rch & RM=PlumCreek,Reach1          ,2769.437
     719     866
River Rch & RM=PlumCreek,Reach1          ,1622.203
     792     949
Boundary for River Rch & Prof#=PlumCreek,Reach1          , 1
Up Type= 0
Dn Type= 3
Dn Slope=0.003
Boundary for River Rch & Prof#=PlumCreek,Reach1          , 2
Up Type= 0
Dn Type= 3
Dn Slope=0.003
DSS Import GetInterval= 0
DSS Import GetPeak= 0
DSS Import FillOption= 0

--- PlumCreek.g01 (geometry) ---

Geom Title=PlumCreek
Program Version=4.00

River Reach=PlumCreek       ,Reach1
Reach XY= 30
1429090.46887074505369.5577594041429102.77258448505477.557024509
1429093.88656898505573.936115533 1429106.1902827505649.809016943
1429089.14604172505807.0872882011429092.27957317505929.295015395
1429121.52586688505993.0101552461429178.97394374506042.102148205
1429194.64160106506070.3039314151429201.95317452506148.642218083
1429176.88492277506263.5383718611429101.68016762506395.146693468
1429108.99174097506506.9093157951429095.41310464506530.933057055
1429027.51992285506575.8470080791429001.40716067506616.582917139
1429010.80775499506661.4968681781429045.27660114506686.565119907
1429142.41607663506908.0013435631429193.59709062506928.891553342
1429287.60303454506995.7402246451429308.49324441507036.476133689
1429303.27069196507113.7699098891429363.85230029507159.728371397
1429404.58820941 507169.128965811429453.68020232507199.419769973
1429487.10453802507253.7343153951429509.03925832507409.366378248
1429498.98774995507538.8621808591429339.92798477507791.411237329

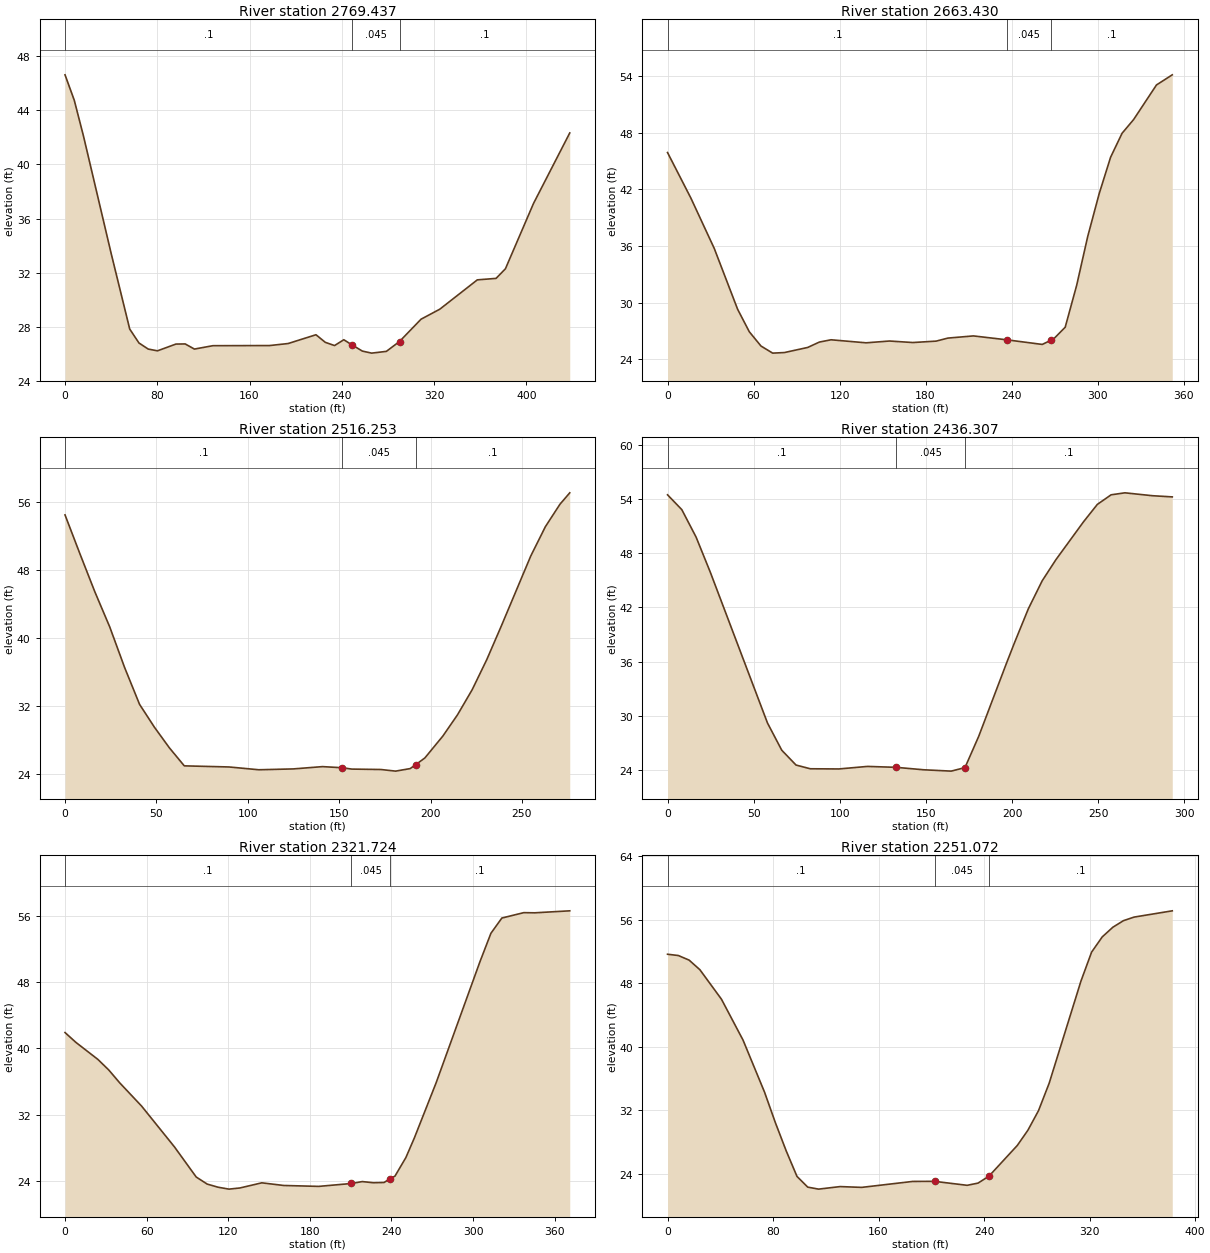
Type RM Length L Ch R = 1 ,2769.437,118.43,106.01,109.41
XS GIS Cut Line= 4
1428833.58042268505418.4609657971429010.63545722505428.789176136
1429141.21354517505414.7723192271429268.10298656505391.902710617
#Sta/Elev= 30
       0   46.63    8.01   44.75   16.03   42.09   40.07   33.39    56.1   27.82
   64.11   26.79   72.12   26.34   80.14   26.21   96.16   26.71  104.18   26.72
  112.19   26.34  128.22   26.59  177.36    26.6  193.45   26.75  217.59    27.4
  225.63   26.84  233.68    26.6  241.72   27.03  248.61   26.66  257.82   26.19
  265.86   26.04  278.63   26.17     290    26.9  308.68   28.55  324.94   29.29
  357.46   31.46  373.72   31.57  381.84   32.28  406.23   37.12  437.62   42.33
#Mann= 3 , 0 , 0
       0      .1       0  248.61    .045       0     290      .1       0
Bank Sta=248.61,290
XS Rating Curve= 0 ,0
Exp/Cntr=0.3,0.1

Type RM Length L Ch R = 1 ,2663.430,146.83,147.18,153.11
XS GIS Cut Line= 4
1428850.54819681505566.0068278761429060.06332099505525.431715801
1429139.73808655505524.6939865051429198.75643139505524.693986505
#Sta/Elev= 30
       0   45.88    16.3   41.06   32.59   35.74   48.89   29.31   57.04   26.93
   65.19   25.42   73.34   24.67   81.49   24.73   97.78   25.27  105.93   25.84
  114.08   26.08  138.53   25.76  154.82   25.95  171.12   25.79  187.42   25.94
  195.57   26.26  213.41   26.49  237.04   26.07  261.41   25.59  267.42   26.03
  269.41   26.18  277.41   27.41  285.41   31.84  293.09   36.99  301.09   41.52
  309.09   45.39  317.09   47.92  325.09   49.36  341.09   53.03   352.1    54.1
#Mann= 3 , 0 , 0
       0      .1       0  237.04    .045       0  267.42      .1       0
Bank Sta=237.04,267.42
XS Rating Curve= 0 ,0
Exp/Cntr=0.3,0.1

Type RM Length L Ch R = 1 ,2516.253,81.19,79.94,85.15
XS GIS Cut Line= 4
1428939.81344336 505695.109457211429062.27650894505670.764389977
1429144.16446242505670.7643899771429213.51101759 505672.97757791
#Sta/Elev= 29
       0   54.49    8.16   49.91   16.31   45.44   24.47    41.3   32.63   36.51
   40.78   32.19   48.94   29.49    57.1   27.07   65.25   24.95   89.72   24.82
  106.04   24.49  124.86   24.59  140.86   24.86  151.51   24.73  156.86   24.57
  172.86   24.52  180.86   24.33  188.86   24.63  191.93    25.1  196.86   25.88
  206.75   28.47  214.75   30.97  222.76   33.92  230.76   37.47  238.76   41.45
  254.77   49.64  262.78    53.1  270.78   55.75  276.13   57.09
#Mann= 3 , 0 , 0
       0      .1       0  151.51    .045       0  191.93      .1       0
Bank Sta=151.51,191.93
XS Rating Curve= 0 ,0
Exp/Cntr=0.3,0.1

Type RM Length L Ch R = 1 ,2436.307,104.46,114.58,121.33
XS GIS Cut Line= 4
1428938.33798474505785.1124331061429058.58786237505752.652343422
1429135.31171067505748.2259675861429226.79014516505745.275050327
#Sta/Elev= 26
       0   54.45    8.29   52.81   16.57   49.78   24.86   45.88      58   29.24
   66.29   26.23   74.58   24.59   82.86   24.18   99.44   24.16  116.01   24.44
  132.57   24.34  148.59   24.07  164.62   23.92  172.63   24.31  180.65   27.79
  196.67   35.82  201.41   38.13  209.41   41.86  217.41   44.94  225.42   47.29
  241.43   51.47  249.43   53.39  257.43   54.45  265.44   54.67  281.45   54.35
  292.93   54.22
#Mann= 3 , 0 , 0
       0      .1       0  132.57    .045       0  172.63      .1       0
Bank Sta=132.57,172.63
XS Rating Curve= 0 ,0
Exp/Cntr=0.3,0.1

Type RM Length L Ch R = 1 ,2321.724,101.42,70.65,65.61
XS GIS Cut Line= 4
1428875.70824583505845.4297518581429053.42375718505862.574010685
 1429131.6230641505864.7871986181429245.23337792505852.245800361
#Sta/Elev= 30
       0    41.9    8.04   40.71   24.11   38.67   32.15   37.39   40.19   35.84
   56.26   33.04   80.37   28.13   96.45   24.48  104.48   23.63  112.52   23.25
  120.56   23.02  128.59   23.16  144.67   23.78  160.74   23.46  186.54   23.35
  210.55    23.7  218.56   23.93  226.56   23.79  234.56   23.82  238.63   24.24
  242.57   24.59  250.57   26.82  256.77   29.17  272.87   35.86  305.06   50.45
  313.11   53.87  321.16   55.71  337.26   56.36  345.31   56.34  371.07   56.58
#Mann= 3 , 0 , 0
       0      .1       0  210.55    .045       0  238.63      .1       0
Bank Sta=210.55,238.63
XS Rating Curve= 0 ,0
Exp/Cntr=0.3,0.1

Type RM Length L Ch R = 1 ,2251.072,111.56,85.3,79.02
XS GIS Cut Line= 4
1428874.53086762505982.0056279151429056.37467444505943.281597272
1429117.60620722505927.7892817411429250.39748311505913.034695536
#Sta/Elev= 30
       0   51.65    8.18   51.49   16.36   50.91   24.54    49.7    40.9   45.98
   57.26   40.83   73.61   34.25   81.79   30.42   89.97   26.88   98.15   23.66
  106.33   22.31  114.51   22.06  130.87   22.38  147.23   22.28  185.92   23.03
  202.43   23.04  227.18   22.54  235.43   22.82  243.69   23.69  265.18   27.56
  273.23   29.48  281.28   31.95  289.33   35.39  313.48   48.28  321.53   51.92
  329.57   53.83  337.62   55.05  345.67   55.88  353.72   56.33  382.69   57.12
#Mann= 3 , 0 , 0
       0      .1       0  202.43    .045       0  243.69      .1       0
Bank Sta=202.43,243.69
XS Rating Curve= 0 ,0
Exp/Cntr=0.3,0.1

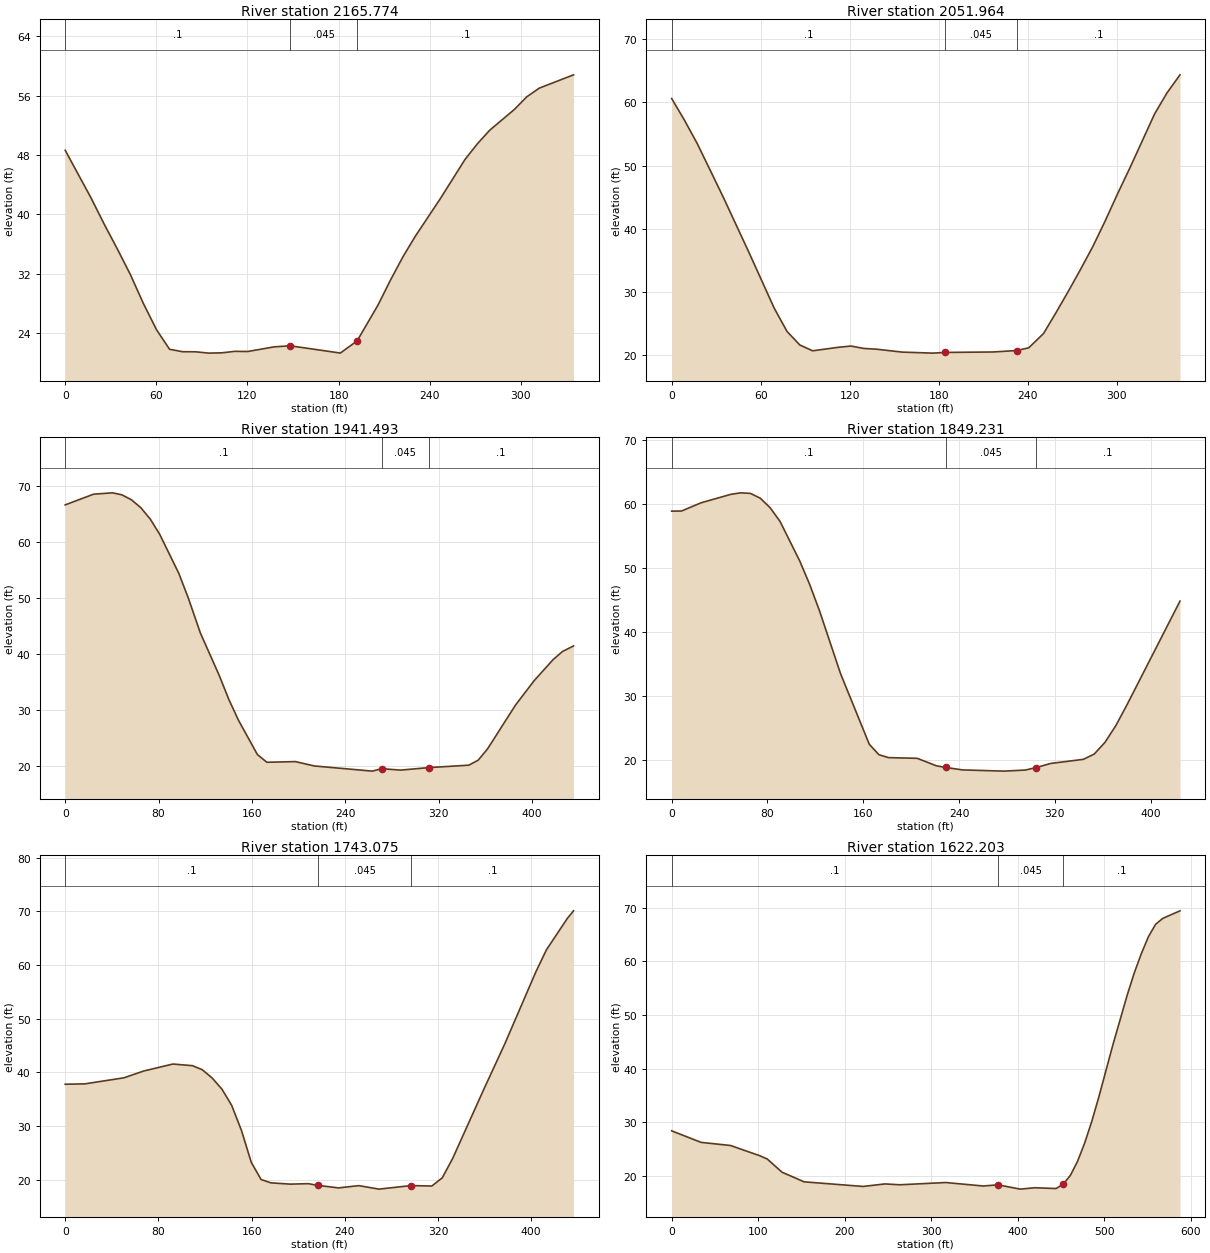
Type RM Length L Ch R = 1 ,2165.774,89.83,113.81,131.23
XS GIS Cut Line= 4
1428970.79807444506086.5486293441429108.75345548506032.694389686
1429150.80402619505992.8570069371429276.95573826505967.774210364
#Sta/Elev= 30
       0   48.65   17.18   42.16   25.76   38.65   34.35   35.33   42.94   31.87
   51.53   27.96   60.12   24.45    68.7   21.81   77.29   21.48   85.88   21.47
   94.47   21.29  103.06   21.33  111.64   21.53  120.23   21.51  137.41   22.13
  148.09   22.28  181.15    21.3  192.17   22.94  206.02   27.81  214.18   31.16
  222.33   34.28  230.49   37.06   246.8   42.08  263.12   47.39  271.27   49.51
  279.43   51.35  295.74   54.17   303.9   55.87  312.06   57.03  334.64   58.83
#Mann= 3 , 0 , 0
       0      .1       0  148.09    .045       0  192.17      .1       0
Bank Sta=148.09,192.17
XS Rating Curve= 0 ,0
Exp/Cntr=0.3,0.1

Type RM Length L Ch R = 1 ,2051.964,89.61,110.47,123.95
XS GIS Cut Line= 4
1429004.73362271506164.0102069681429160.39450724506100.565486252
1429242.28246067506089.4995465871429330.80997796506064.416750044
#Sta/Elev= 30
       0    60.6    8.64   57.17   17.28   53.46   34.56   45.11   51.83    36.4
   69.11   27.46   77.75   23.77   86.39   21.62   95.03    20.7  112.31   21.25
  120.95   21.45  129.58   21.07  138.22   20.95   155.5   20.49  176.17   20.33
  184.24   20.44  216.53   20.51  232.68   20.74  240.75   21.17  250.73   23.43
  259.04   26.69  267.36   30.07  275.67   33.57  283.99    37.2   292.3   41.24
  300.62   45.52  308.93   49.61  325.56   58.14  333.88   61.46  342.74   64.35
#Mann= 3 , 0 , 0
       0      .1       0  184.24    .045       0  232.68      .1       0
Bank Sta=184.24,232.68
XS Rating Curve= 0 ,0
Exp/Cntr=0.3,0.1

Type RM Length L Ch R = 1 ,1941.493,72.25,92.26,112.9
XS GIS Cut Line= 5
1428920.63248129506203.9951355761429034.97260666506222.395569384
1429155.96813136506200.0113973021429245.97110723506211.815066278
1429351.46639861506219.930088684
#Sta/Elev= 30
       0   66.63   24.31   68.54   40.51   68.78   48.62   68.42   56.72   67.54
   64.82   66.12   72.93   64.08   81.03   61.35   97.24   54.45  105.34   50.08
  115.81   43.77  132.08   36.14  140.22    31.9  148.35   28.25  164.63    22.1
  172.76   20.72  197.17   20.84  213.44   20.06  263.07   19.14  271.13   19.58
  287.27   19.32  311.48   19.77  345.68    20.2   353.7   21.08  361.73   23.09
   385.8   30.94  401.85   35.31  417.89   39.02  425.92   40.47  435.44   41.47
#Mann= 3 , 0 , 0
       0      .1       0  271.13    .045       0  311.48      .1       0
Bank Sta=271.13,311.48
XS Rating Curve= 0 ,0
Exp/Cntr=0.3,0.1

Type RM Length L Ch R = 1 ,1849.231,96.06,106.15,104.74
XS GIS Cut Line= 5
1428899.23833133506242.3570597171429036.46274389506274.953166515
1429129.40987617506275.9975162891429204.65826584 506309.93306458
 1429299.8253469506360.836386994
#Sta/Elev= 30
       0   58.94    8.22   58.96   24.67   60.25   49.34   61.56   57.56    61.8
   65.78   61.71      74   60.96   82.23   59.47   90.45   57.35  106.89   51.18
  115.12   47.55  123.34   43.44  141.04   33.55  165.04   22.53  173.04   20.91
  181.05   20.45  205.05   20.34  221.05   19.17  229.05   18.91  242.77   18.53
  277.88   18.34  295.43   18.51   304.2   18.89  316.54   19.54  343.76   20.18
  352.83      21   361.9   22.85  370.98   25.48  380.05   28.64  424.47   44.89
#Mann= 3 , 0 , 0
       0      .1       0  229.05    .045       0   304.2      .1       0
Bank Sta=229.05,304.2
XS Rating Curve= 0 ,0
Exp/Cntr=0.3,0.1

Type RM Length L Ch R = 1 ,1743.075,103.62,120.87,112.65
XS GIS Cut Line= 4
 1428870.4668882506300.6376752561429068.91607276506364.820125282
1429141.95127448506395.8047563141429274.74255037506462.200394258
#Sta/Elev= 30
       0   37.78   16.82   37.85   50.45   38.98   67.26   40.24   92.49   41.55
   109.3   41.24  117.71   40.48  126.12   38.95  134.53   36.87  142.94   33.83
  151.34   29.14  159.75   23.21  168.16   20.01  176.57   19.39  193.38   19.15
  208.57   19.24  217.26   18.91  234.64   18.45  252.02   18.87   269.4   18.22
  296.85   18.88  314.74    18.8  323.68   20.33  332.63   23.95  359.46   36.89
  377.35    45.3  404.18   58.81  413.13   62.86  431.01   68.69  436.37   70.12
#Mann= 3 , 0 , 0
       0      .1       0  217.26    .045       0  296.85      .1       0
Bank Sta=217.26,296.85
XS Rating Curve= 0 ,0
Exp/Cntr=0.3,0.1

Type RM Length L Ch R = 1 ,1622.203,74.87,88.78,93.03
XS GIS Cut Line= 5
1428737.52806646 506354.196823211429017.86520444506455.265738741
1429063.60442171506483.2994525281429150.65648033506515.021812871
1429290.08732003 506547.48190254
#Sta/Elev= 30
       0   28.44   34.02   26.29   68.03   25.71  102.05   23.79  110.55   23.18
  127.56   20.73  153.07   18.94  221.11   18.08  246.62   18.55  263.63   18.39
  316.77   18.81  360.16   18.16  377.19   18.38  402.73   17.58  419.76   17.84
   444.3   17.69  452.51   18.51  460.73   20.13  468.94   22.72  477.15    26.1
  485.37   30.13  493.58    34.7  510.01   44.53  526.44   53.73  534.65   57.89
  542.87    61.5  551.08   64.65  559.29   66.93  567.51   68.03  587.46   69.44
#Mann= 3 , 0 , 0
       0      .1       0  377.19    .045       0  452.51      .1       0
Bank Sta=377.19,452.51
XS Rating Curve= 0 ,0
Exp/Cntr=0.3,0.1

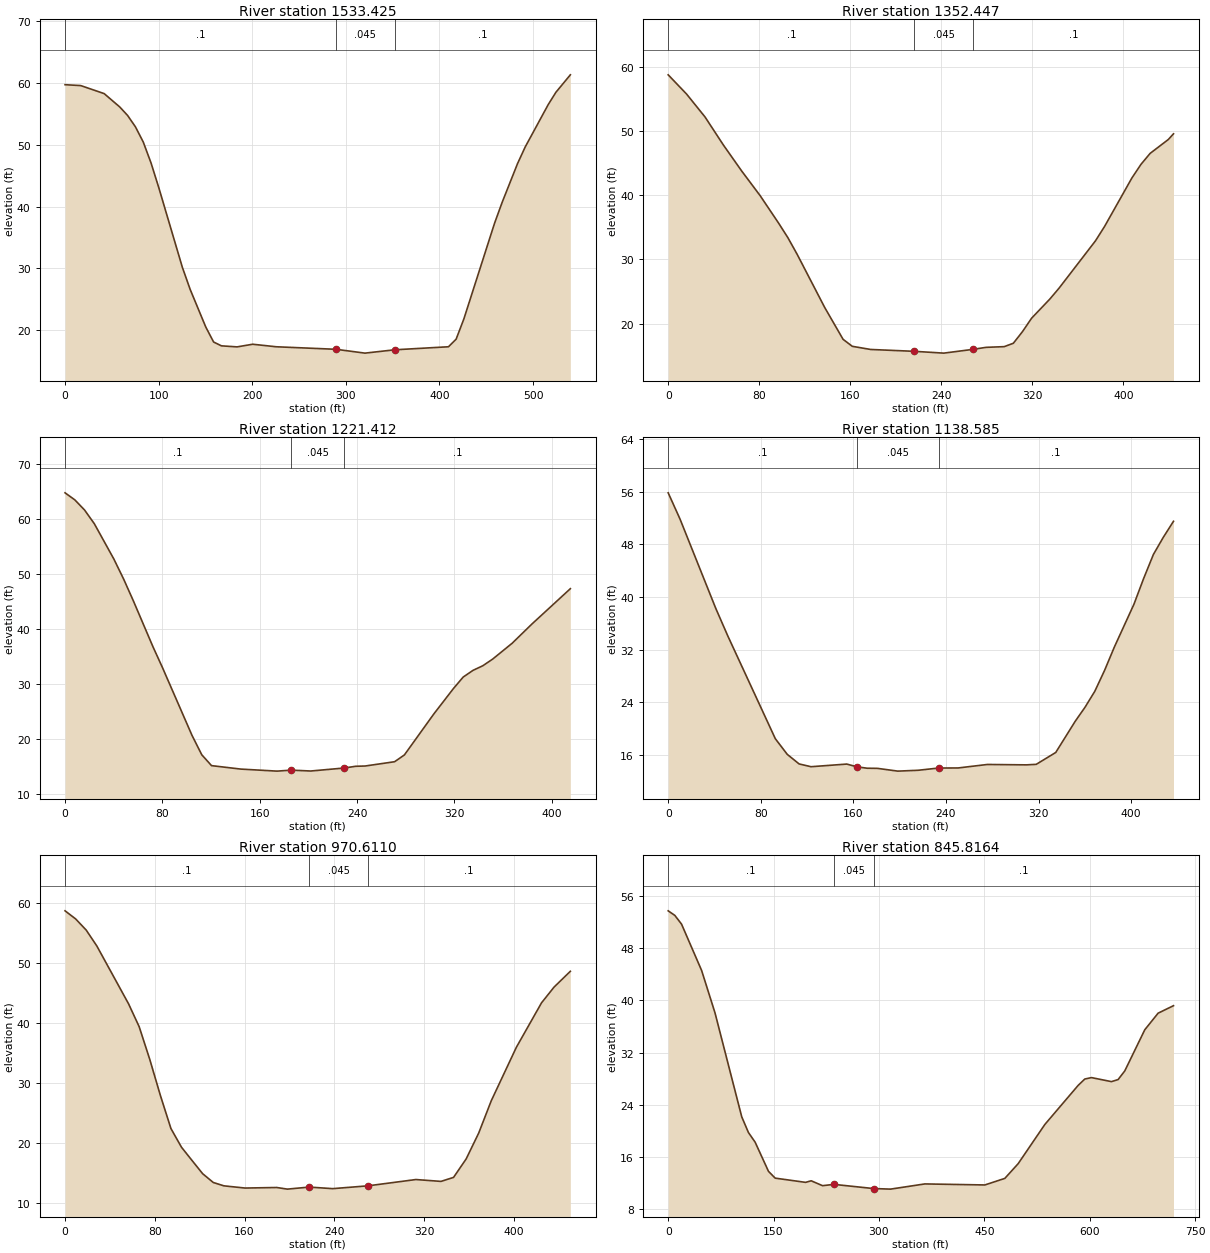
Type RM Length L Ch R = 1 ,1533.425,212.41,180.98,91.53
XS GIS Cut Line= 4
1428768.51269747506456.7411973631429021.55385099 506532.72731635
1429078.35900791 506588.794743941429269.43089934506631.583043933
#Sta/Elev= 30
       0   59.76   16.71   59.62   41.76   58.32   58.47   56.15   66.82   54.78
   75.18   52.94   83.53   50.48   91.88   47.08  100.23   43.04  125.29    30.2
  133.65   26.61  150.35   20.51  158.71   18.09  167.06   17.47  183.76    17.3
  200.47   17.73  225.53   17.32  289.45   16.91  320.41   16.29  352.22   16.83
   409.6   17.32   417.8   18.55     426    21.8  458.79    37.3  466.99   40.72
  483.39   46.98  491.59   49.68  516.18   56.54  524.38   58.53  539.82   61.36
#Mann= 3 , 0 , 0
       0      .1       0  289.45    .045       0  352.22      .1       0
Bank Sta=289.45,352.22
XS Rating Curve= 0 ,0
Exp/Cntr=0.3,0.1

Type RM Length L Ch R = 1 ,1352.447,133.1,131.04,122.26
XS GIS Cut Line= 4
1428818.67829064506745.1933577511429015.65201651506715.684185326
1429090.16267686506686.1750129011429254.67631309506695.027764633
#Sta/Elev= 30
       0   58.75   16.18   55.75   32.36   52.19   48.54   47.81   64.71   43.74
   80.89   39.91   97.07   35.64  105.16   33.39  113.25   30.82  137.52   22.52
   153.7   17.55  161.79   16.46  177.96   15.97  216.38   15.68  242.19    15.4
  268.01   15.99  279.31    16.3  295.34   16.41  303.35   16.94  311.36   18.75
  319.37   20.84  335.39   23.82  343.41    25.5  375.45   32.88  383.46   35.12
   407.5   42.68  415.51   44.81  423.52   46.51  439.54   48.68  444.06   49.56
#Mann= 3 , 0 , 0
       0      .1       0  216.38    .045       0  268.01      .1       0
Bank Sta=216.38,268.01
XS Rating Curve= 0 ,0
Exp/Cntr=0.3,0.1

Type RM Length L Ch R = 1 ,1221.412,95.52,82.83,98.85
XS GIS Cut Line= 4
1428901.30397338506854.3772957181429065.81760959 506841.09816812
1429136.63962345 506800.523056031429304.10417692506780.604364648
#Sta/Elev= 30
       0   64.83    8.03   63.55   16.05    61.7   24.08    59.2   40.13   52.78
   48.16   49.13   56.18   45.16   72.23   36.84   80.26   32.94  104.34   20.71
  112.36   17.18  120.39    15.2  144.47   14.57  174.27    14.2   185.9   14.38
  201.93   14.22  229.59   14.77  238.81   15.08  246.67   15.13  270.84   15.91
   278.9   17.14  303.07   24.59  319.18   29.21  327.23   31.31  335.29   32.53
  343.35   33.37   351.4   34.57  367.52   37.47  383.63   40.94  415.32   47.39
#Mann= 3 , 0 , 0
       0      .1       0   185.9    .045       0  229.59      .1       0
Bank Sta=185.9,229.59
XS Rating Curve= 0 ,0
Exp/Cntr=0.3,0.1

Type RM Length L Ch R = 1 ,1138.585,176.15,167.97,127.39
XS GIS Cut Line= 4
1428973.60144579507015.2022853791429100.49088724506912.657911226
1429172.05063035506879.4600922471429356.48295796506817.490830168
#Sta/Elev= 30
       0   55.82   10.29   51.81   41.14   38.27   51.43   34.13   92.57    18.5
  102.86   16.13  113.14   14.67  123.43   14.25  154.29   14.65  163.14   14.23
  171.96   14.02  180.78      14  198.42   13.58  216.06   13.71   233.7   14.05
  250.47   14.06  275.79   14.59  309.55   14.53  317.99   14.61  334.86   16.41
  351.74   21.16  360.18   23.28  368.62    25.7  377.06   28.87   385.5   32.41
  402.38   38.89  410.82   42.82  419.26   46.47   427.7   49.04   436.6    51.5
#Mann= 3 , 0 , 0
       0      .1       0  163.14    .045       0   233.7      .1       0
Bank Sta=163.14,233.7
XS Rating Curve= 0 ,0
Exp/Cntr=0.3,0.1

Type RM Length L Ch R = 1 ,970.6110,76.82,124.79,185.99
XS GIS Cut Line= 4
1429070.98171479507128.812599197 1429246.5612907507018.890931949
1429300.41553035506955.4462112491429414.76357348506843.311356038
#Sta/Elev= 30
       0   58.68    9.44   57.33   18.88   55.46   28.32   52.82   56.63   43.16
   66.07   39.35   75.51    33.9   84.95    27.9   94.38   22.36  103.82   19.23
  113.26   17.01   122.7   14.81  132.14   13.35  141.58   12.79  160.45   12.42
  188.77   12.51  198.21   12.24  217.64   12.58  238.63   12.32  270.11   12.79
  312.78   13.84  335.19   13.53  346.39    14.2   357.6   17.27   368.8   21.59
  380.01   26.99  402.42   35.92  424.83   43.33  436.03   45.96  450.52   48.59
#Mann= 3 , 0 , 0
       0      .1       0  217.64    .045       0  270.11      .1       0
Bank Sta=217.64,270.11
XS Rating Curve= 0 ,0
Exp/Cntr=0.3,0.1

Type RM Length L Ch R = 1 ,845.8164,167.93,169.99,158.5
XS GIS Cut Line= 4
1429085.11527462507203.3799779861429235.89547542507106.166427493
1429401.55530128507085.3349523841429716.01137786506884.956001356
#Sta/Elev= 30
       0   53.78    9.52   53.07   19.04   51.73   47.59   44.61   66.63    38.1
   104.7   22.12  114.22   19.71  123.74   18.23  142.78   13.74   152.3    12.7
  195.53   12.05  203.59   12.29  219.72   11.54  235.84   11.74  292.28    11.1
  316.47   11.01  365.34   11.81  450.71   11.65  479.17   12.66  498.15   14.92
  536.09   20.94  583.52   26.95  593.01   27.93  602.49   28.15  630.95   27.53
  640.44   27.85  649.92   29.18  678.38    35.5  697.35   38.05  719.24    39.2
#Mann= 3 , 0 , 0
       0      .1       0  235.84    .045       0  292.28      .1       0
Bank Sta=235.84,292.28
XS Rating Curve= 0 ,0
Exp/Cntr=0.3,0.1

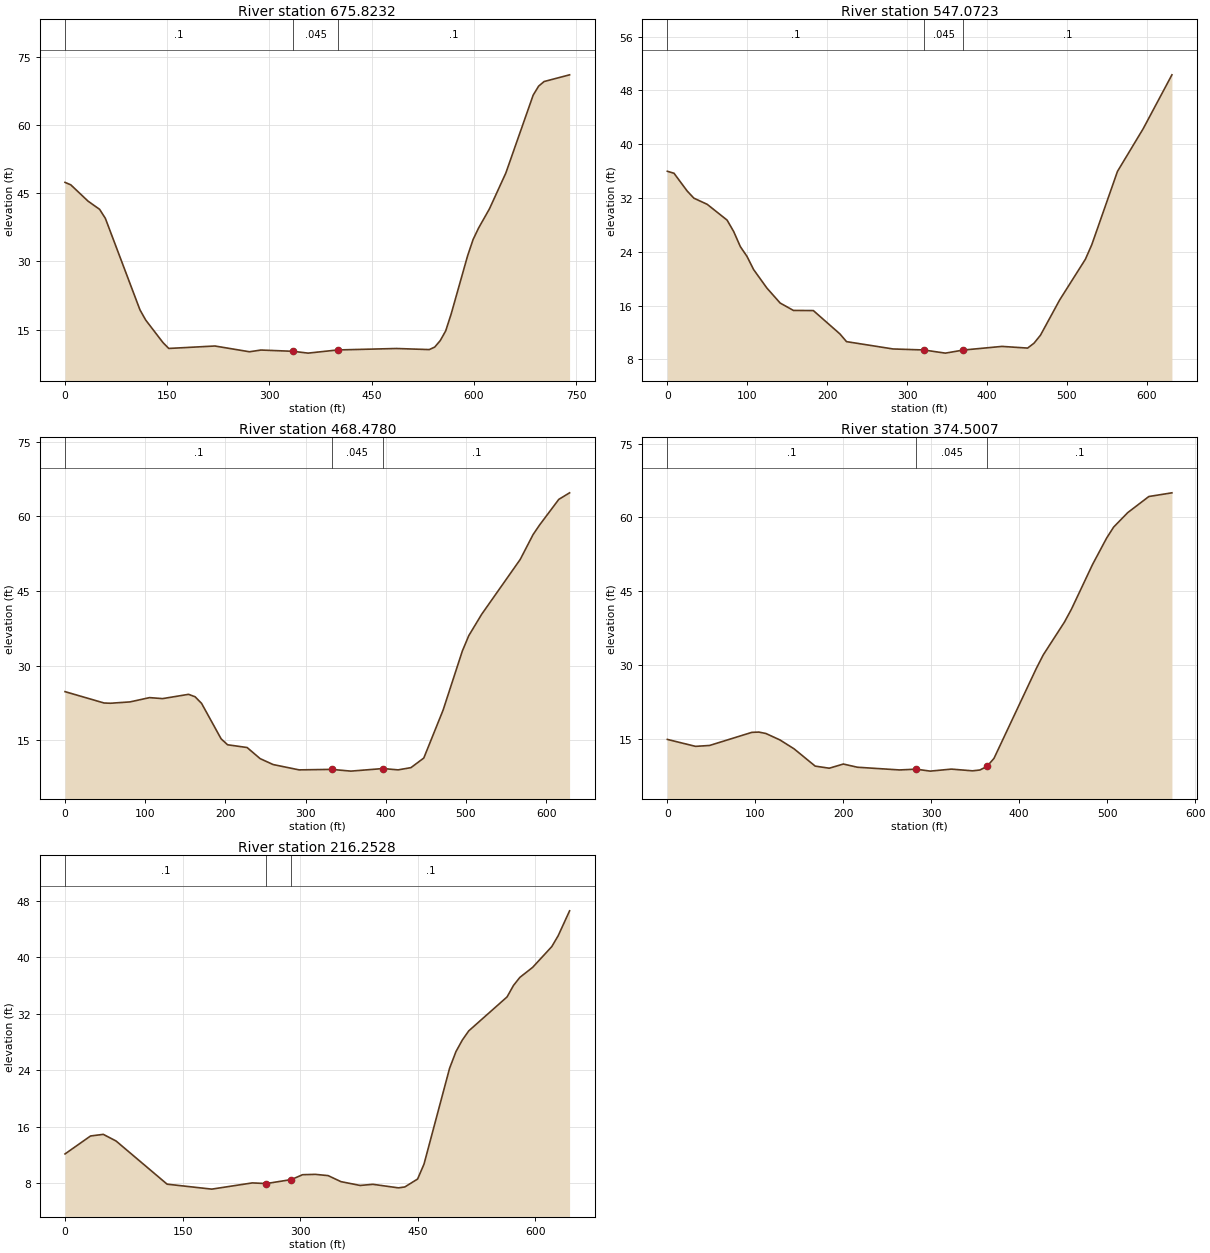
Type RM Length L Ch R = 1 ,675.8232,126.35,128.75,134.13
XS GIS Cut Line= 4
 1429099.0029247 507318.44907856 1429405.5232013507213.299728051
1429466.03367655507157.7491277611429799.33727829507182.548502877
#Sta/Elev= 30
       0   47.44    8.46    46.9   33.83    43.3   50.75    41.5    59.2   39.51
  109.95   19.35  118.41   17.09  143.78   12.12  152.24   10.83   219.9   11.37
  270.64    10.1  287.56   10.48  334.91    10.2  356.63     9.8  400.07    10.5
  486.42   10.82  534.55   10.58  542.57   11.14  550.59   12.56  558.62    14.7
  566.64   18.43  590.71   31.23  598.73   34.81  606.75   37.34  622.79    41.6
  646.86    49.5  686.97   66.67  694.99   68.66  703.01   69.67  740.42   71.15
#Mann= 3 , 0 , 0
       0      .1       0  334.91    .045       0  400.07      .1       0
Bank Sta=334.91,400.07
XS Rating Curve= 0 ,0
Exp/Cntr=0.3,0.1

Type RM Length L Ch R = 1 ,547.0723,66.87,78.59,80.31
XS GIS Cut Line= 4
1429163.48130004507378.9595538821429452.14602648 507298.60957846
1429522.57625185507290.6737784451429782.47370321507313.489203542
#Sta/Elev= 30
       0   35.98     8.3   35.69   24.91   33.03   33.22   31.98   49.82   31.07
   74.74   28.72   83.04   27.01   91.35   24.77   99.65   23.32  107.95   21.36
  124.56   18.61  141.17   16.38  157.78   15.28  182.69   15.26  215.91   11.79
  224.21   10.64  282.34    9.55  320.69     9.4  347.94    8.93  370.51    9.39
   418.7    9.93  450.82    9.68  458.85   10.41  466.88   11.59  490.98   16.85
   523.1   22.89  531.13   25.06  563.25   35.96  595.38    42.3  631.41   50.33
#Mann= 3 , 0 , 0
       0      .1       0  320.69    .045       0  370.51      .1       0
Bank Sta=320.69,370.51
XS Rating Curve= 0 ,0
Exp/Cntr=0.3,0.1

Type RM Length L Ch R = 1 ,468.4780,91.96,93.98,90.39
XS GIS Cut Line= 4
1429149.87997423507419.8949941691429462.04730403507367.867105871
1429552.79362081507372.7069094331429774.21463384507387.226320148
#Sta/Elev= 30
       0   24.81   48.66   22.53   56.77   22.48    81.1   22.75  105.43   23.61
  121.66   23.41   154.1   24.27  162.21   23.78  170.32   22.45  194.65   15.34
  202.76   14.14  227.09   13.59  243.31   11.36  259.53   10.17  291.97     9.1
   332.5     9.2  356.53    8.85  396.59    9.37  415.37     9.1   431.4    9.55
  447.43   11.48  471.49    21.1  495.54   32.99  503.55   36.06  519.59   40.34
  567.69   51.36  583.73   56.35  591.74   58.25   615.8   63.42  629.24   64.73
#Mann= 3 , 0 , 0
       0      .1       0   332.5    .045       0  396.59      .1       0
Bank Sta=332.5,396.59
XS Rating Curve= 0 ,0
Exp/Cntr=0.3,0.1

Type RM Length L Ch R = 1 ,374.5007,129.93,158.25,178.95
XS GIS Cut Line= 4
1429187.28870016507459.3095293051429470.00157657507466.253354341
1429542.41575195507461.2934793081429760.65025309507465.261379331
#Sta/Elev= 30
       0   14.93   32.01   13.52   48.01    13.7   96.03   16.36  104.03   16.42
  112.03   16.13  128.04   14.82  144.04   13.02  168.05    9.51  184.06    9.08
  200.06    9.93  216.07    9.28  264.08    8.73   282.8    8.89  298.84    8.49
  322.89     8.9  346.95    8.55  355.38    8.72  363.38    9.44  371.38   11.09
  419.39   29.31  427.39    32.1   451.4   38.74   459.4   41.37   483.4   50.45
  499.41   55.81  507.41   58.05  523.41   60.98  547.41   64.25  573.65      65
#Mann= 3 , 0 , 0
       0      .1       0   282.8    .045       0  363.38      .1       0
Bank Sta=282.8,363.38
XS Rating Curve= 0 ,0
Exp/Cntr=0.3,0.1

Type RM Length L Ch R = 1 ,216.2528,216.01,216.25,228.91
XS GIS Cut Line= 4
1429192.87523939507550.6787110871429427.67755999507594.704146206
1429484.74756841507624.054436266 1429819.0147609507689.277303085
#Sta/Elev= 30
       0   12.16   32.56    14.7   48.84   14.93   65.12   13.99  130.23    7.88
  187.21    7.18  238.89    8.06  256.89    7.97  288.61    8.53  303.07    9.22
  319.37    9.27  335.67    9.09  351.97    8.24  376.43     7.7  392.73    7.86
  425.33    7.36  433.48    7.49  449.78    8.61  457.94   10.72  490.54   24.27
  498.69   26.64  506.84   28.28  514.99   29.57   563.9   34.38  572.05      36
   580.2   37.14   596.5   38.56  620.95    41.5   629.1   43.04  643.64   46.56
#Mann= 3 , 0 , 0
       0      .1       0  256.89    .045       0  288.61      .1       0
Bank Sta=256.89,288.61
XS Rating Curve= 0 ,0
Exp/Cntr=0.3,0.1

Chan Stop Cuts=-1
Use User Specified Reach Order=0