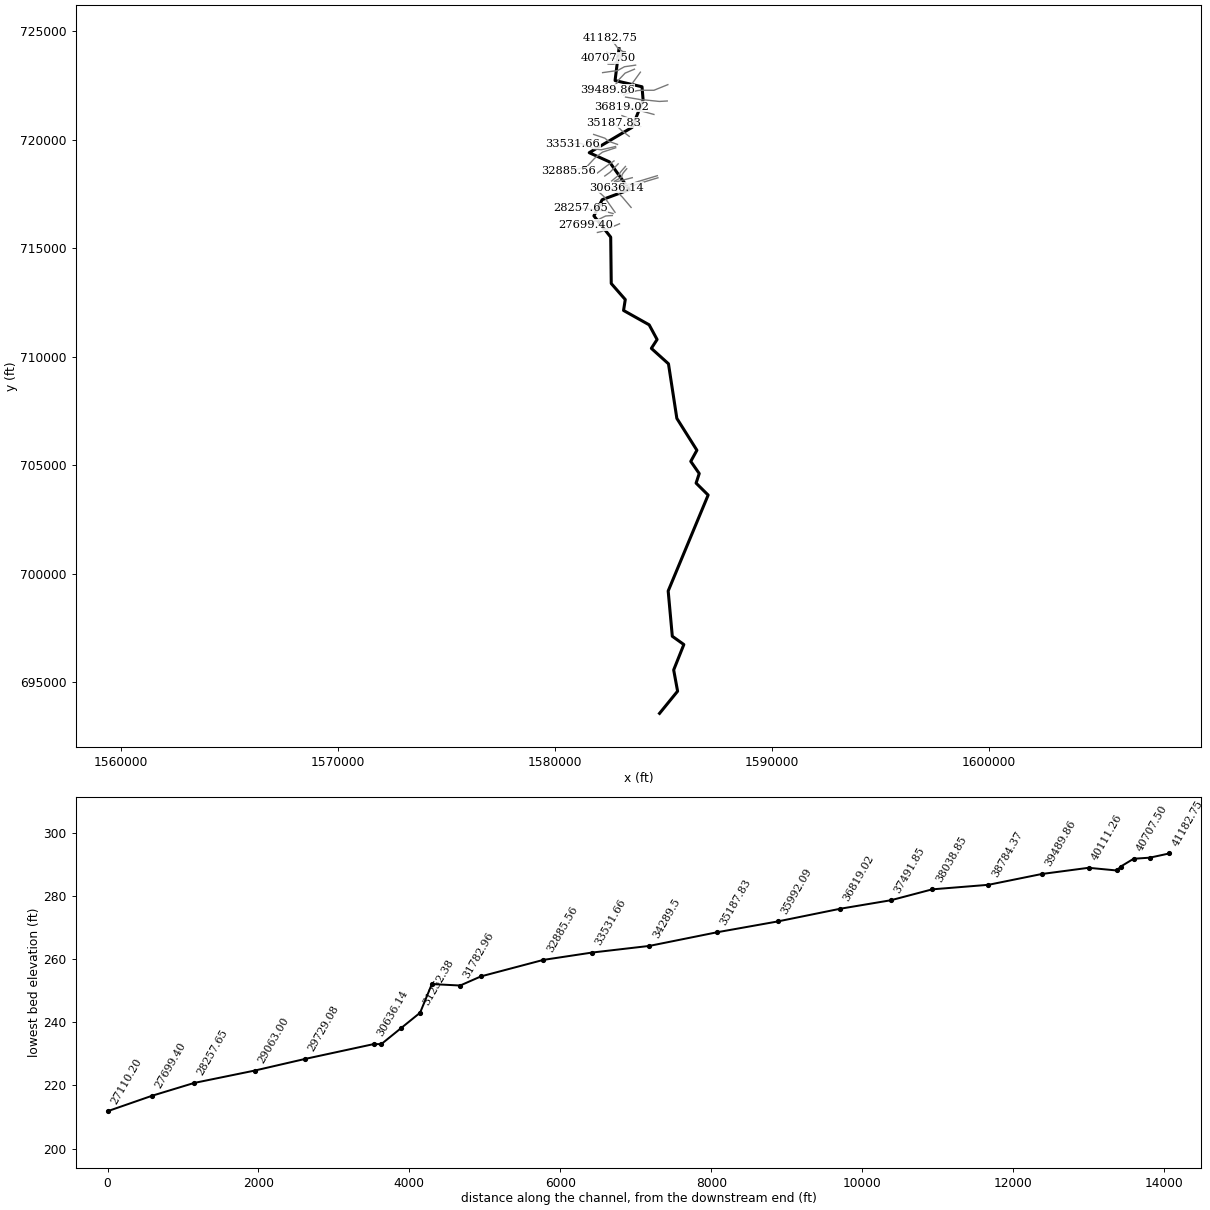
--- PrincipioCreek.prj (project) ---

Proj Title=PrincipioCreek
Current Plan=p01
Default Exp/Contr=0.3,0.1
English Units
Geom File=g01
Flow File=f01
Plan File=p01
Y Axis Title=Elevation
X Axis Title(PF)=Main Channel Distance
X Axis Title(XS)=Station
BEGIN DESCRIPTION:
Principio Creek - Georeferenced HEC-RAS model.  This was formerly an approximate method stream.  Projection:  MD Stateplane.  Horizontal datum:  NAD83.  Vertrial datum: NAVD88.  Units:Feet.  Created by: Aaron W. Buesing, USACE- St Paul District as part of FEMA Map Modernization study for Cecil County, MD.
END DESCRIPTION:
DSS Export Rating Curves= 0
DSS Export Rating Curve Sorted= 0
DSS Export Volume Flow Curves= 0
DXF OffsetX= 0
DXF OffsetY= 0
DXF ScaleX= 1
DXF ScaleY= 10

--- PrincipioCreek.p01 (plan) ---

Plan Title=PrincipioCreek_100yr
Program Version=4.00
Short Identifier=PrincipioCr100
Geom File=g01
Flow File=f01
Subcritical Flow
K Sum by GR= 0
Std Step Tol= 0.01
Critical Tol= 0.01
Num of Std Step Trials= 20
Max Error Tol= 0.3
Flow Tol Ratio= 0.001
Split Flow NTrial= 30
Split Flow Tol= 0.02
Split Flow Ratio= 0.02
Log Output Level= 0
Friction Slope Method= 1
Unsteady Friction Slope Method= 2
Unsteady Bridges Friction Slope Method= 1
Secant Critical Depth
Global Vel Dist= 0 , 0 , 0
Global Log Level= 0
CheckData=True
Encroach Param=-1 ,0,0, 0
Computation Interval=1HOUR
Output Interval=1HOUR
Run HTab= 0
Run UNet= 0
Run PostProcess= 0
Run WQNet= 0
UNET Theta= 1
UNET Theta Warmup= 1
UNET ZTol= 0.02
UNET ZSATol= 0.05
UNET MxIter= 20
UNET MaxInSteps= 0
UNET DtIC= 0
UNET DtMin= 0
UNET MaxCRTS= 20
UNET WFStab= 2
UNET SFStab= 1
UNET WFX= 1
UNET SFX= 1
UNET DSS MLevel= 4
UNET DZMax Abort= 100
UNET Convert EG Bridges= 0
UNET Use Existing IB Tables=-1
UNET Froude Reduction=False
UNET Froude Limit= 1
UNET Froude Power= 10
UNET Time Slicing=0,0, 5
Instantaneous Interval=1HOUR
Write IC File= 0
Echo Input=False
Echo Output=False
Write Detailed= 0
Detailed Automatic Start=False, 10
WQ ULTIMATE=-1
WQ Max Comp Step=1HOUR
WQ Output Interval=15MIN
WQ Output Selected Increments= 0
WQ Output face flow=0
WQ Output face velocity=0
WQ Output face area=0
WQ Output face dispersion=0
WQ Output cell volume=0
WQ Output cell surface area=0
WQ Output cell continuity=0
WQ Output face conc=0
WQ Output face dconc_dx=0
WQ Output face courant=0
WQ Output face peclet=0
WQ Output face adv mass=0
WQ Output face disp mass=0
WQ Output cell mass=0
WQ Output cell source sink temp=0
WQ Output cell source sink nsm=0
WQ Output MaxMinRange=-1
WQ Daily Max Min Mean=-1
WQ Daily Range=0
WQ Daily Time=0
WQ Create Restart=0
WQ Fixed Restart=0
WQ System Summary=False
Sorting and Armoring Iterations= 10
XS Update Threshold= 0.02
Hydraulics Update Threshold= 0.02
Energy Slope Method= 1
Volume Change Method= 0
XS Weighting Method= 0
Number of US Weighted Cross Sections= 1
Number of DS Weighted Cross Sections= 1
Upstream XS Weight=0.25
Main XS Weight=0.5
Downstream XS Weight=0.25
Number of DS XS's Weighted with US Boundary= 1
Upstream Boundary Weight= 1
Weight of XSs Associated with US Boundary= 0
Number of US XS's Weighted with DS Boundary= 1
Downstream Boundary Weight= 0.5
Weight of XSs Associated with DS Boundary= 0.5
Sediment Output Level= 4
Mass or Volume Output= 0
Output Increment Type= 1
Profile and TS Output Increment= 10
XS Output Flag= 0
XS Output Increment= 10
Disregard all LS=0
Disregard all Conn=0
Disregard all Breaches=0
Disregard all Pumps=0

--- PrincipioCreek.f01 (steady flow) ---

Flow Title=PrincipioCreek_100yr
Program Version=4.00
Number of Profiles= 2
Profile Names=100CUR,100ULT
River Rch & RM=PrincipioCreek,Reach1          ,41182.75
    3610    3680
River Rch & RM=PrincipioCreek,Reach1          ,40111.26
    3860    3890
River Rch & RM=PrincipioCreek,Reach1          ,36819.02
    4650    4750
River Rch & RM=PrincipioCreek,Reach1          ,33531.66
    4730    4830
River Rch & RM=PrincipioCreek,Reach1          ,32885.56
    5110    5240
River Rch & RM=PrincipioCreek,Reach1          ,29729.08
    5310    5450
River Rch & RM=PrincipioCreek,Reach1          ,27699.40
    5700    5840
River Rch & RM=PrincipioCreek,Reach1          ,23353.77
    5820    6040
River Rch & RM=PrincipioCreek,Reach1          ,20659.51
    6030    6250
River Rch & RM=PrincipioCreek,Reach1          ,17392.61
    6290    6450
River Rch & RM=PrincipioCreek,Reach1          ,11673.68
    6660    6840
River Rch & RM=PrincipioCreek,Reach1          ,8267.967
    6950    7140
River Rch & RM=PrincipioCreek,Reach1          ,6684.306
    7130    7330
River Rch & RM=PrincipioCreek,Reach1          ,1360.015
    7870    8100
River Rch & RM=PrincipioCreek,Reach1          ,569.5728
    8020    8260
Boundary for River Rch & Prof#=PrincipioCreek,Reach1          , 1
Up Type= 0
Dn Type= 3
Dn Slope=0.0008
Boundary for River Rch & Prof#=PrincipioCreek,Reach1          , 2
Up Type= 0
Dn Type= 3
Dn Slope=0.0008
DSS Import GetInterval= 0
DSS Import GetPeak= 0
DSS Import FillOption= 0

--- PrincipioCreek.g01 (geometry) ---

Geom Title=PrincipioCreek
Program Version=4.00

River Reach=PrincipioCreek  ,Reach1
Reach XY= 30
1582943.94373508724199.2401055251582762.72408514722729.886905506
1584004.90241294722443.7506161031584054.32595389721833.239824086
 1583551.8532881720575.8008941261581571.79016544719405.069930658
1582499.99894668718984.1027533861583418.40972766717702.819132641
1582169.20805453717238.931511953 1581787.0860462716492.375920534
1582561.12806305715513.2695630041582586.27337334713376.004897133
1583232.68126348712636.2992350461583153.77701394712133.739861324
1584334.04585372711471.6378292591584699.51993246710794.535318986
1584435.06063469710386.5743366631585223.66958985 709675.56901148
1585609.95358056707159.0437002331586534.26050326705690.210747972
1586251.59253255 705177.766666071586641.77838171 704617.19966273
1586496.97607771 704175.856113331587052.34060304703625.000402272
1585210.57668695699204.1947310721585400.46713355697117.133977816
1585932.42050792696736.0524651111585463.76394905695564.627837926
1585644.37664324694584.8278166351584812.50134546693562.861592516

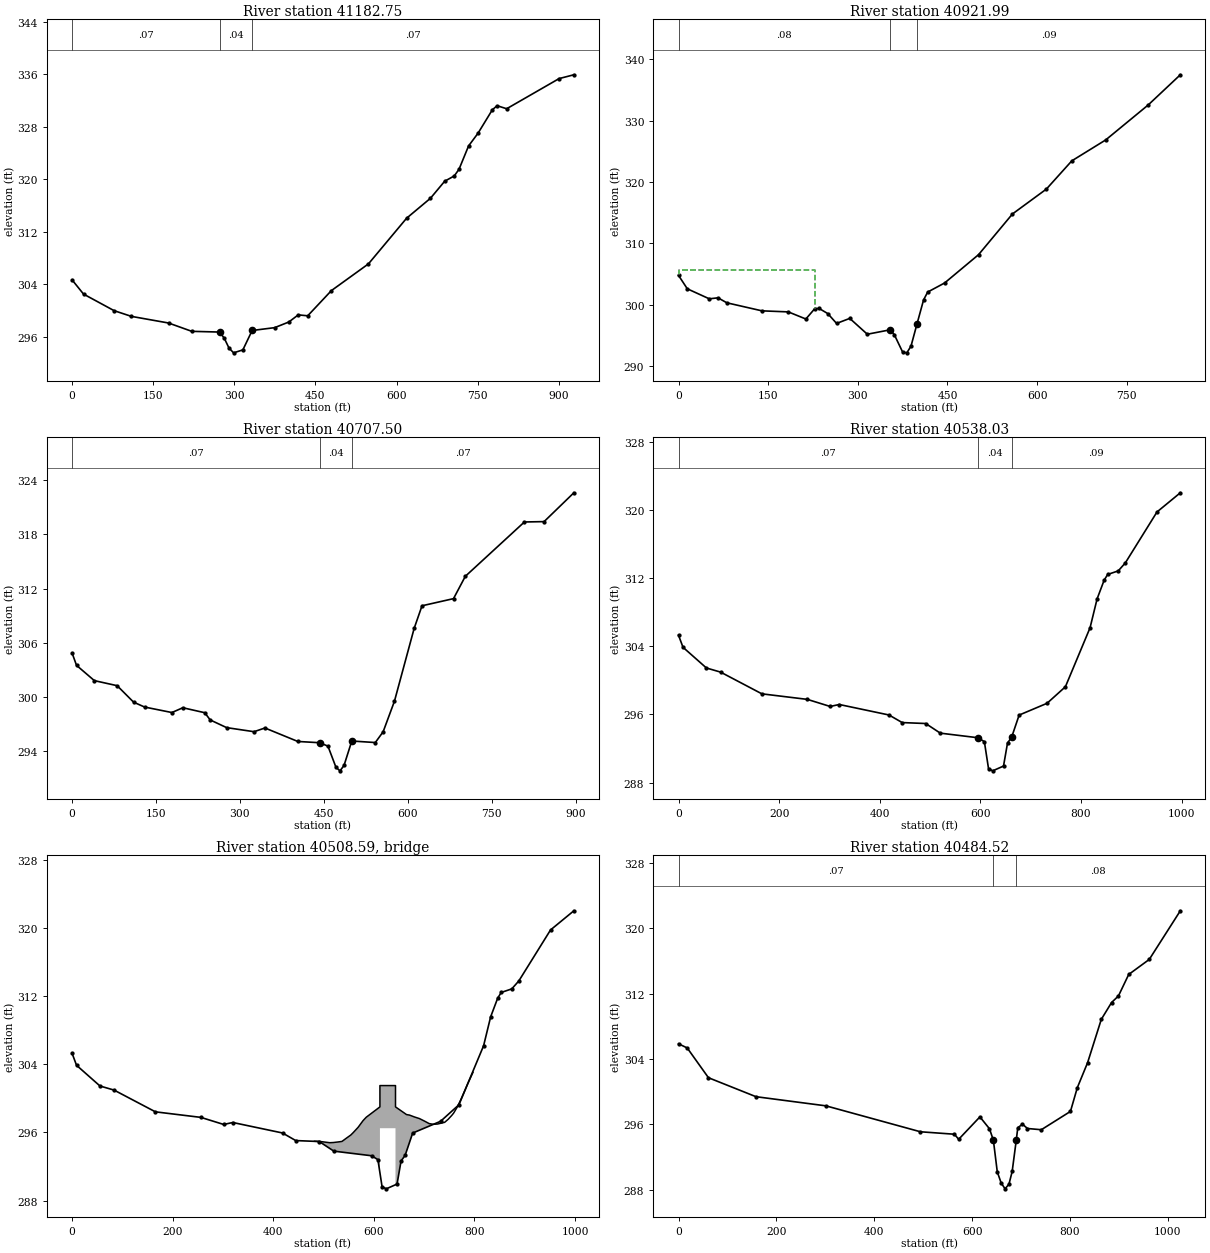
Type RM Length L Ch R = 1 ,41182.75,213.89,260.76,293.27
XS GIS Cut Line= 5
1583202.04618326724057.1697234061583110.43634972724070.587325305
1582887.73790246724228.7981409881582788.92702253724360.545980886
1582547.38931602724676.191847339
#Sta/Elev= 30
       0  304.67   21.22   302.5   77.82  299.97  109.76   299.1  178.45  298.09
  221.39  296.82  272.91  296.71  281.49  295.76  290.08  294.29  298.67  293.54
  315.84  293.99  333.01  296.95  374.51  297.38  400.76  298.24  418.26  299.33
  435.76  299.19  479.51  303.03  548.08  307.11  618.59  314.07  662.66  317.11
  689.11  319.72  706.73  320.52  715.55  321.54  733.18  325.09  750.81  327.05
  777.25  330.62  786.06  331.23  803.69  330.77  900.65  335.37  927.91  335.95
#Mann= 3 , 0 , 0
       0     .07       0  272.91     .04       0  333.01     .07       0
Bank Sta=272.91,333.01
XS Rating Curve= 0 ,0
Exp/Cntr=0.3,0.1

Type RM Length L Ch R = 1 ,40921.99,177.62,214.49,223.9
XS GIS Cut Line= 4
1583206.21026659724054.8563437761582882.24840917723951.578727841
1582805.39550251723954.3234744971582388.19400947724022.942141116
#Sta/Elev= 30
       0   304.8   14.69  302.62   51.43  300.99   66.12  301.15   80.82  300.34
  139.59  299.03  183.68  298.86  213.07   297.7  227.76  299.36  235.11  299.43
   249.8  298.58   264.5  296.98  286.54   297.8  315.93  295.22  354.03  295.94
  361.04  295.16  375.05  292.31  382.05  292.19  389.06  293.29     399  296.88
  410.07  300.81  416.93  302.09   445.3  303.57  502.06  308.18  558.81  314.81
  615.56  318.86  658.13  323.46  714.88  326.87  785.82  332.55  839.73  337.48
#Mann= 3 , 0 , 0
       0     .08       0  354.03     .04       0     399     .09       0
#XS Ineff= 2 , 0
          228.61  305.71
Permanent Ineff=
       F       F
Bank Sta=354.03,399
XS Rating Curve= 0 ,0
Exp/Cntr=0.3,0.1

Type RM Length L Ch R = 1 ,40707.50,59.55,169.47,199.98
XS GIS Cut Line= 6
1583207.93550324724053.9914877411583162.93206254 724029.53875117
 1582872.3700045723745.7965400221582837.70462711723737.707951948
1582754.50772128723735.3969268051582435.58624895723768.906791642
#Sta/Elev= 30
       0  304.88    7.97  303.51   39.83  301.82   80.57  301.26  109.92  299.44
  129.49   298.9  178.41  298.29  197.98  298.82  237.11  298.27   246.9  297.47
  276.25  296.62  325.17  296.17  344.74  296.58  403.44  295.09  442.58  294.95
  457.34  294.57  471.72  292.22   478.9  291.84  486.09  292.44  499.94  295.14
  541.96  294.97  555.96  296.16  576.17  299.54  611.36  307.59  625.44   310.1
  681.74  310.89  702.86  313.36  808.44  319.37  843.63  319.41  896.84   322.6
#Mann= 3 , 0 , 0
       0     .07       0  442.58     .04       0  499.94     .07       0
Bank Sta=442.58,499.94
XS Rating Curve= 0 ,0
Exp/Cntr=0.5,0.3

Type RM Length L Ch R = 1 ,40538.03,68.76,53.51,54.5
BEGIN DESCRIPTION:
Center of channel lowered 2.5 ft based on bridge survey info.
END DESCRIPTION:
XS GIS Cut Line= 6
1583210.83236243724054.1784748291583124.90221094723972.367671549
1582824.81747328723615.5219942931582707.61969461723528.714399815
1582672.52058716723520.6796627191582444.14542773723527.242167309
#Sta/Elev= 30
       0  305.29    8.88  303.88   55.49  301.45   83.54  300.97  165.72  298.42
  256.09  297.77  301.43  296.94  319.57  297.17  418.41  295.94  444.65  295.05
  491.36  294.94  520.39  293.81  595.45  293.27  608.01  292.81  616.26  289.65
  624.52  289.39  646.06  289.95  654.04  292.66  662.03   293.3   677.1  295.93
  732.58  297.31  769.09  299.25  818.11  306.17  832.12  309.56  846.12  311.75
  853.13  312.42  874.13  312.84  888.14  313.77  951.17  319.75  997.56     322
#Mann= 3 , 0 , 0
       0     .07       0  595.45     .04       0  662.03     .09       0
Bank Sta=595.45,662.03
XS Rating Curve= 0 ,0
Exp/Cntr=0.5,0.3

Type RM Length L Ch R = 3 ,40508.59,,,
BEGIN DESCRIPTION:
Principio Road, MDE Bridge #: CE032907PF-3
Top of road obtained from DEM.
Opening from MDE2 bridge/culvert surveys.
END DESCRIPTION:
Bridge Culvert--1,0,-1,-1, 0
Deck Dist Width WeirC Skew NumUp NumDn MinLoCord MaxHiCord MaxSubmerge Is_Ogee
16.8,20,2.6,0, 35, 32, , , 0.98, 0, 2,2,,
  482.02  493.68  503.01  512.33  519.04  527.79  536.54  545.29  554.04  558.68
  568.58  578.48  584.84     612     612     643     643   664.9  670.77  680.67
  690.57  700.47  710.02  717.99  726.57  733.63  740.68  747.74  754.79  758.53
  765.53  772.54  779.54  786.54   797.1
  294.97  294.94  294.87   294.8  294.82  294.88  294.95  295.33   295.7  295.97
   296.6  297.39  297.79     299   301.5   301.5     299   298.1  298.04  297.82
  297.63  297.34  297.04  296.96  296.99  297.09  297.19  297.55     298  298.27
  298.96  299.81  300.75  301.71  303.06
                                                                                
                                   296.5   296.5
                                                                                
                                        
   522.3  532.68  542.01  551.33  558.04  566.79  575.54  584.29  593.04  597.68
  607.58  617.48  623.84     651     651     682     682   703.9  709.77  719.67
  729.57  739.47  749.02  756.99  765.57  772.63  779.68  786.74  793.79  797.53
  804.53  814.98
  294.96  294.94  294.87   294.8  294.82  294.88  294.95  295.33   295.7  295.97
   296.6  297.39  297.79     299   301.5   301.5     299   298.1  298.04  297.82
  297.63  297.34  297.04  296.96  296.99  297.09  297.19  297.55     298  298.27
  298.96   300.5
                                                                                
                                   296.5   296.5
                                                                                
                
BR Coef=-1 , 0 , 0 ,, 0 ,,,0.8,-1,,0,
WSPro=,,,, 1 ,,,, 0 ,,,, 0 ,,,,-1 ,-1 ,-1 , 0 , 0 , 0 , 0 , 0
BC Design=,, 0 ,, 0 ,,,,,,
BC Use User HTab Curves=0
BC User HTab FreeFlow(D)= 0

Type RM Length L Ch R = 1 ,40484.52,459.3,373.26,327.85
BEGIN DESCRIPTION:
Center of channel lowered 2.5 ft based on bridge survey info.
END DESCRIPTION:
XS GIS Cut Line= 6
1583235.45812412 724022.657499881583107.70904613723892.162243262
1582855.11184582723589.2478243111582731.83077537723496.356938139
1582674.43801785 723480.608052791582442.99647671 723487.25867179
#Sta/Elev= 30
       0  305.87   17.77  305.36   61.17  301.72   158.3   299.4  301.32  298.28
  494.33  295.11  563.78  294.81  572.53  294.19  615.92  296.93  635.44  295.48
  643.43  294.08  651.41  290.21  659.39  288.84  667.38  288.13  675.36  288.71
  681.86  290.26  690.23  294.09  693.31   295.6  702.88  296.04  713.11  295.51
  741.43  295.36  800.97   297.6  814.98   300.5  835.99  303.56     864  308.86
  885.01  310.92  899.01  311.72  920.02  314.35  962.04  316.19 1025.51  322.14
#Mann= 3 , 0 , 0
       0     .07       0  643.43     .04       0  690.23     .08       0
Bank Sta=643.43,690.23
XS Rating Curve= 0 ,0
Exp/Cntr=0.5,0.3

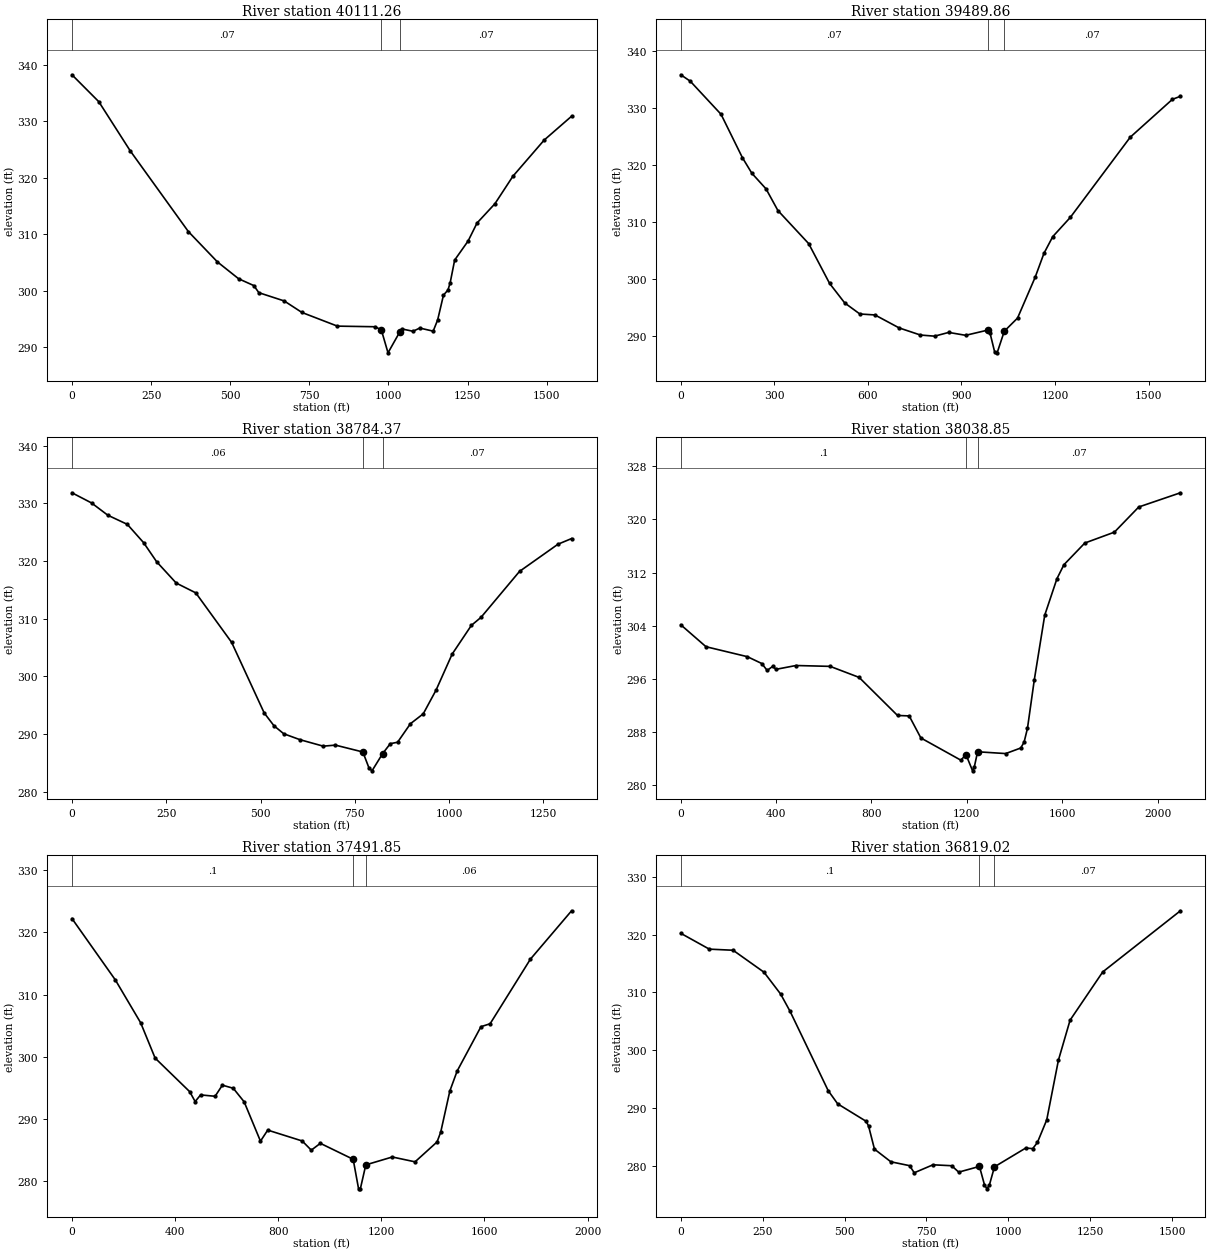
Type RM Length L Ch R = 1 ,40111.26,378.97,621.41,619.23
XS GIS Cut Line= 6
1583708.41715527723441.0558481811583195.14952897723366.947688222
1582893.22739583723199.5181416721582783.43752922 723169.32592836
1582725.79784924723172.0706750151582187.82750295723095.217768401
#Sta/Elev= 30
       0  338.22   84.87  333.45  183.89  324.77  367.77  310.46  459.72  305.08
  526.59   302.1  574.62  300.89  590.63  299.63  670.67  298.17   726.7  296.13
  838.76  293.71  958.21   293.6  977.69  293.03  998.72  288.98  1035.4  292.63
 1042.47  293.21 1077.81   292.8 1099.01  293.37 1141.42  292.82 1155.56   294.8
 1173.97   299.2 1188.12   300.1 1195.19   301.4 1209.33  305.41 1251.77  308.78
 1280.06  311.97 1336.63  315.39 1393.21  320.24 1492.22  326.66 1578.83  330.88
#Mann= 3 , 0 , 0
       0     .07       0  977.69     .04       0  1035.4     .07       0
Bank Sta=977.69,1035.4
XS Rating Curve= 0 ,0
Exp/Cntr=0.3,0.1

Type RM Length L Ch R = 1 ,39489.86,608.04,705.49,631.77
XS GIS Cut Line= 6
1583656.26696864723254.4130749551583225.34174225723073.259795085
1582912.44062243722743.8901953251582860.29043582722625.866088718
1582670.90291592722455.6917954981582410.15198281722315.709715605
#Sta/Elev= 30
       0  335.89   30.37  334.76  129.09  328.94  197.43  321.33   227.8  318.58
  273.36  315.83  311.33  312.03  410.04  306.21  477.15  299.21  525.63  295.78
   574.1  293.84  622.58  293.67  700.14  291.39  768.38  290.14  813.72  289.94
  859.06   290.6  913.47  290.09  983.74     291  991.39  290.52 1006.69   287.1
 1014.35  287.01 1037.31  290.81 1079.78  293.12 1136.24  300.29 1164.47   304.5
 1192.71  307.44 1249.17  310.83 1441.22  324.92 1576.29  331.57 1602.11  332.11
#Mann= 3 , 0 , 0
       0     .07       0  983.74     .04       0 1037.31     .07       0
Bank Sta=983.74,1037.31
XS Rating Curve= 0 ,0
Exp/Cntr=0.3,0.1

Type RM Length L Ch R = 1 ,38784.37,765.66,745.52,468.63
XS GIS Cut Line= 4
1583929.92897116723117.3028835061583544.25851557722583.992956668
1583441.81480081722406.2229810361583062.17044611722144.087593272
#Sta/Elev= 30
       0  331.82   51.83  330.06   95.02  327.93  146.86  326.34  190.05  323.16
   224.6  319.85  276.44  316.16  328.27  314.46  423.29  305.88  509.68  293.63
  535.59  291.41  561.51  290.02   604.7  288.99  666.23  287.87  698.55  288.05
  771.26  286.86  787.42   284.1  795.49  283.59  823.68  286.58  843.97   288.3
  863.32  288.55  897.35  291.76  931.38  293.48   965.4   297.6 1007.94  303.83
 1058.97  308.82 1084.49  310.21 1186.57  318.18 1288.65   322.9 1324.68  323.88
#Mann= 3 , 0 , 0
       0     .06       0  771.26     .04       0  823.68     .07       0
Bank Sta=771.26,823.68
XS Rating Curve= 0 ,0
Exp/Cntr=0.3,0.1

Type RM Length L Ch R = 1 ,38038.85,451.28,546.99,416.73
XS GIS Cut Line= 5
1585195.41015346 722541.810250581584553.63041101722282.687913254
1583960.05947548722282.687913254 1583785.3025503722267.622661084
1583176.66636258722086.839635015
#Sta/Elev= 30
       0  304.14  105.69  300.84  279.31  299.34  339.71  298.31  362.35  297.27
     385  297.87   400.1  297.44  483.14  298.01  626.57  297.88  748.12  296.22
  909.12  290.49  958.12  290.42 1007.12   287.1 1175.12  283.75 1196.12  284.61
 1224.12  282.15 1231.12  282.71 1245.12  285.02 1362.97  284.75 1426.21  285.59
 1440.26  286.49 1454.31  288.55    1483  295.86 1526.81   305.6 1577.93  311.08
 1607.14  313.18 1694.77  316.45  1818.9  318.09 1921.14  321.88 2096.01  324.02
#Mann= 3 , 0 , 0
       0      .1       0 1196.12     .04       0 1245.12     .07       0
Bank Sta=1196.12,1245.12
XS Rating Curve= 0 ,0
Exp/Cntr=0.3,0.1

Type RM Length L Ch R = 1 ,37491.85,566.69,672.83,542.97
XS GIS Cut Line= 6
1585168.29269956721788.5476420371584803.71359704721767.456288993
 1584137.8294511721836.756448999 1583987.1769294721839.769499421
1583851.58965984721866.886953354 1583245.9665226721969.330668092
#Sta/Elev= 30
       0  322.24  168.28  312.35  266.44  305.45  322.54  299.76  456.68  294.35
  477.79  292.76  498.91  293.83  555.21  293.61  583.36   295.4  625.59   294.9
  667.81  292.72  731.15  286.38  759.31  288.16  893.02  286.41  928.21  284.93
   963.4  286.03 1090.68  283.46 1111.68   278.7 1118.68  278.73 1139.69  282.56
 1242.46  283.83 1330.72  283.05 1415.92  286.25 1430.11  287.81 1465.61  294.46
 1494.01  297.68  1586.3  304.82  1621.8  305.29 1777.99  315.69 1937.85  323.49
#Mann= 3 , 0 , 0
       0      .1       0 1090.68     .04       0 1139.69     .06       0
#XS Ineff= 2 , 0
          888.13  286.37
Permanent Ineff=
       F       F
Bank Sta=1090.68,1139.69
XS Rating Curve= 0 ,0
Exp/Cntr=0.3,0.1

Type RM Length L Ch R = 1 ,36819.02,670.57,826.94,729.17
XS GIS Cut Line= 5
1584553.29954551721168.161432266 1583989.8100055721322.620494023
1583683.75223507721385.5482598991583566.47776228721437.034613803
1583074.49704713721531.426262632
#Sta/Elev= 30
       0  320.22    87.1  317.48  159.68  317.29  254.04  313.49  304.85  309.71
  333.88   306.7  450.01     293  479.04  290.71  566.14  287.68   573.4  286.87
  591.42  282.87  641.45  280.68  698.62  280.01  712.91  278.78  770.08  280.16
  827.25     280  848.69  278.89  912.03  279.88  927.32   276.7  934.96     276
   942.6  276.71  957.89  279.81 1053.32  283.06 1074.71  282.96 1088.96  284.02
 1117.47  287.93 1153.11  298.25 1188.75  305.19 1288.54  313.54 1525.77  324.12
#Mann= 3 , 0 , 0
       0      .1       0  912.03     .04       0  957.89     .07       0
Bank Sta=912.03,957.89
XS Rating Curve= 0 ,0
Exp/Cntr=0.3,0.1

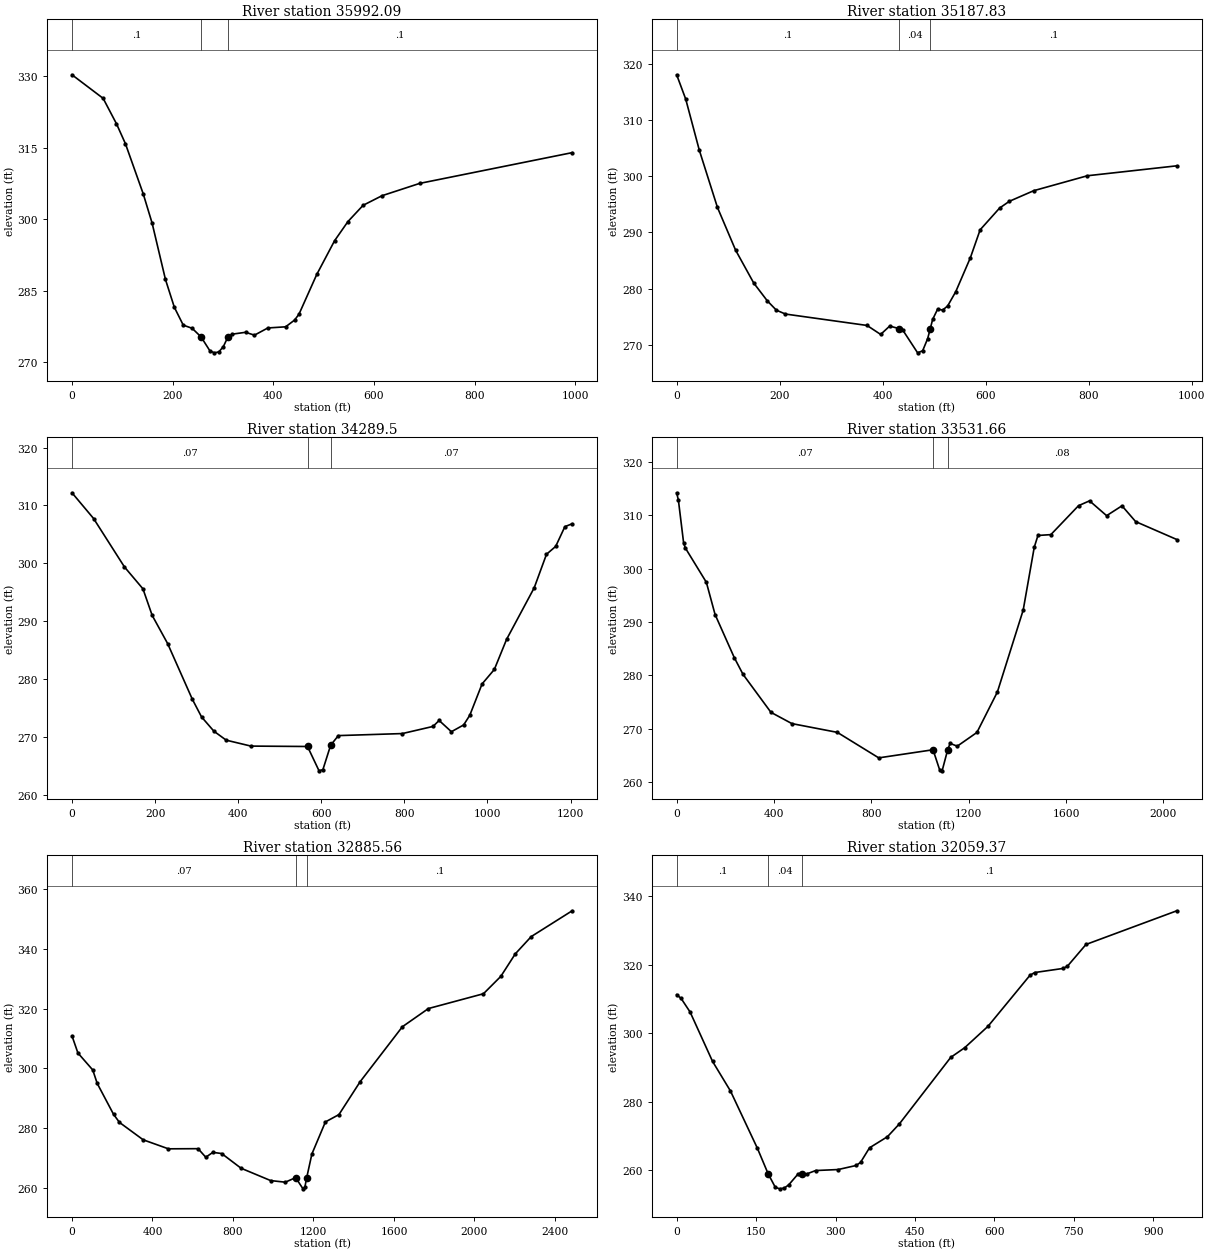
Type RM Length L Ch R = 1 ,35992.09,741.66,804.26,716.21
XS GIS Cut Line= 3
1583926.88223961720613.2529512491583474.94646643720962.216016635
1583080.21775308721113.814725384
#Sta/Elev= 30
       0  330.33   61.91  325.38   88.44  320.04  106.13  315.88   141.5  305.36
  159.19  299.21  185.72  287.38  203.41  281.53   221.1  277.79  238.79  277.13
  256.47  275.32  274.16  272.38     283  271.98  291.85  272.18  300.69  273.28
  309.54  275.24  318.38   275.9  344.91  276.29   362.6  275.69  389.13   277.2
  424.51  277.44   442.2  278.85  451.04  280.09  486.41  288.44  521.79  295.51
  548.32  299.53  578.48  302.94  615.97  304.95  690.96  307.54  993.82  313.99
#Mann= 3 , 0 , 0
       0      .1       0  256.47     .04       0  309.54      .1       0
Bank Sta=256.47,309.54
XS Rating Curve= 0 ,0
Exp/Cntr=0.3,0.1

Type RM Length L Ch R = 1 ,35187.83,831.44,898.34,886.11
XS GIS Cut Line= 4
1583414.87905353720158.4568250481583065.91598818720424.469653606
1582994.40716325720498.8388314691582676.90798084720787.734483957
#Sta/Elev= 30
       0  318.09    17.6  313.75   44.01  304.64   79.22  294.45  114.42  286.85
  149.63  280.99  176.04  277.81  193.64  276.15  211.25  275.46  369.68  273.43
  396.09  271.83  413.69  273.32  431.29  272.88  438.79  272.64  467.92  268.55
  477.64  268.92  487.35  271.07  492.52  272.88  497.06   274.5  506.77  276.34
  516.48  276.17  526.19   276.9  541.96  279.45  570.36   285.5  589.28  290.47
  627.14  294.35  646.07  295.55  693.39  297.44  797.49   300.1  971.23  301.87
#Mann= 3 , 0 , 0
       0      .1       0  431.29     .04       0  492.52      .1       0
Bank Sta=431.29,492.52
XS Rating Curve= 0 ,0
Exp/Cntr=0.3,0.1

Type RM Length L Ch R = 1 ,34289.5 ,654.21,757.84,742.38
XS GIS Cut Line= 4
1582874.27233745719786.6109357031582453.80044724719935.349291444
1582296.48103248720072.6462352131581775.89678745720247.127767891
#Sta/Elev= 30
       0  312.19   51.98  307.75  126.23   299.4  170.78  295.62  193.05  291.03
  230.18  286.18  289.58  276.58  311.85  273.52  341.55  271.06  371.25  269.51
  430.65  268.49  566.89  268.42  594.66  264.22  603.95  264.43  622.53  268.63
  641.11   270.3  795.08  270.65  868.91  271.88  883.67  272.91   913.2  270.97
  942.73  272.14   957.5  273.81  987.03  279.21 1016.56  281.71 1046.09  286.91
 1112.54   295.8 1142.07  301.58 1164.22  302.94 1186.36  306.35 1203.85  306.84
#Mann= 3 , 0 , 0
       0     .07       0  566.89     .04       0  622.53     .07       0
#XS Ineff= 2 , 0
                          884.27           272.6
Permanent Ineff=
       F       F
Bank Sta=566.89,622.53
XS Rating Curve= 0 ,0
Exp/Cntr=0.3,0.1

Type RM Length L Ch R = 1 ,33531.66,346.24,646.1,714.79
XS GIS Cut Line= 6
1582785.60139461719689.3589338961582113.41844083719537.760225147
1581761.59502241719586.3862260731581712.96902154719629.291520998
1581178.08301148719835.2369366291580806.23712213719809.493759662
#Sta/Elev= 30
       0  314.22    7.18  312.82    28.7  304.78   35.88  303.86  121.99  297.45
  157.87  291.41   236.8  283.33  272.68   280.2  387.49  273.08   473.6  270.97
  660.18  269.33   830.4  264.55 1053.57  266.07 1081.57  262.19 1090.91  262.12
 1113.71  266.06 1123.76  267.26 1153.13  266.74 1233.87  269.31 1317.96  276.89
 1424.07  292.24 1469.55  304.02 1484.71  306.22 1537.77  306.38 1651.47   311.8
 1696.74  312.71 1766.91  309.93 1830.06  311.78 1886.19  308.82 2055.44  305.46
#Mann= 3 , 0 , 0
       0     .07       0 1053.57     .04       0 1113.71     .08       0
Bank Sta=1053.57,1113.71
XS Rating Curve= 0 ,0
Exp/Cntr=0.3,0.1

Type RM Length L Ch R = 1 ,32885.56,724.27,826.19,759.32
XS GIS Cut Line= 6
1582791.32210062719632.151873976 1582184.9272657719431.927164331
1581964.68008509719266.0266906321581813.08137636719140.171158865
1581452.67689897718751.1631515321580631.75558946718556.659147874
#Sta/Elev= 30
       0  310.86   29.49  305.14   103.2  299.48  125.32  294.99  206.41  284.69
  235.89  281.97  353.84  276.16  479.16  273.15   626.6   273.2  664.89  270.34
  699.94  271.97  743.76  271.58  840.16  266.67  987.12  262.55  1059.9  262.01
 1111.37  263.53 1147.97  259.79 1157.12  260.32 1166.28   263.5 1192.02  271.41
 1259.28  282.13 1326.54  284.58 1432.22  295.59 1641.76  313.91 1771.25  319.99
 2044.61  324.93 2130.94  330.73 2202.88  338.25 2282.01  344.01 2485.41  352.63
#Mann= 3 , 0 , 0
       0     .07       0 1111.37     .04       0 1166.28      .1       0
Bank Sta=1111.37,1166.28
XS Rating Curve= 0 ,0
Exp/Cntr=0.3,0.1

Type RM Length L Ch R = 1 ,32059.37,267.98,276.41,287.87
XS GIS Cut Line= 3
1582714.09256975719025.7570390551582373.71056335718794.068446472
1581950.37832013718470.848558053
#Sta/Elev= 30
       0  311.23    8.47  310.11    25.4  306.15   67.74  291.76  101.61  283.11
  152.42  266.41  172.66  258.98  186.29     255  194.76  254.57  203.23   254.8
  211.69  255.75  228.63   258.8   237.1  258.99  245.56  258.92   262.5  259.91
  304.84   260.2  338.71  261.38  347.18  262.28  364.11  266.54  397.98  269.78
  420.56  273.53  517.44  292.92  543.86  295.75  587.89     302  667.16  316.89
  675.96  317.68  728.81  318.86  737.61  319.49  772.84  325.87  944.37   335.7
#Mann= 3 , 0 , 0
       0      .1       0  172.66     .04       0   237.1      .1       0
Bank Sta=172.66,237.1
XS Rating Curve= 0 ,0
Exp/Cntr=0.3,0.1

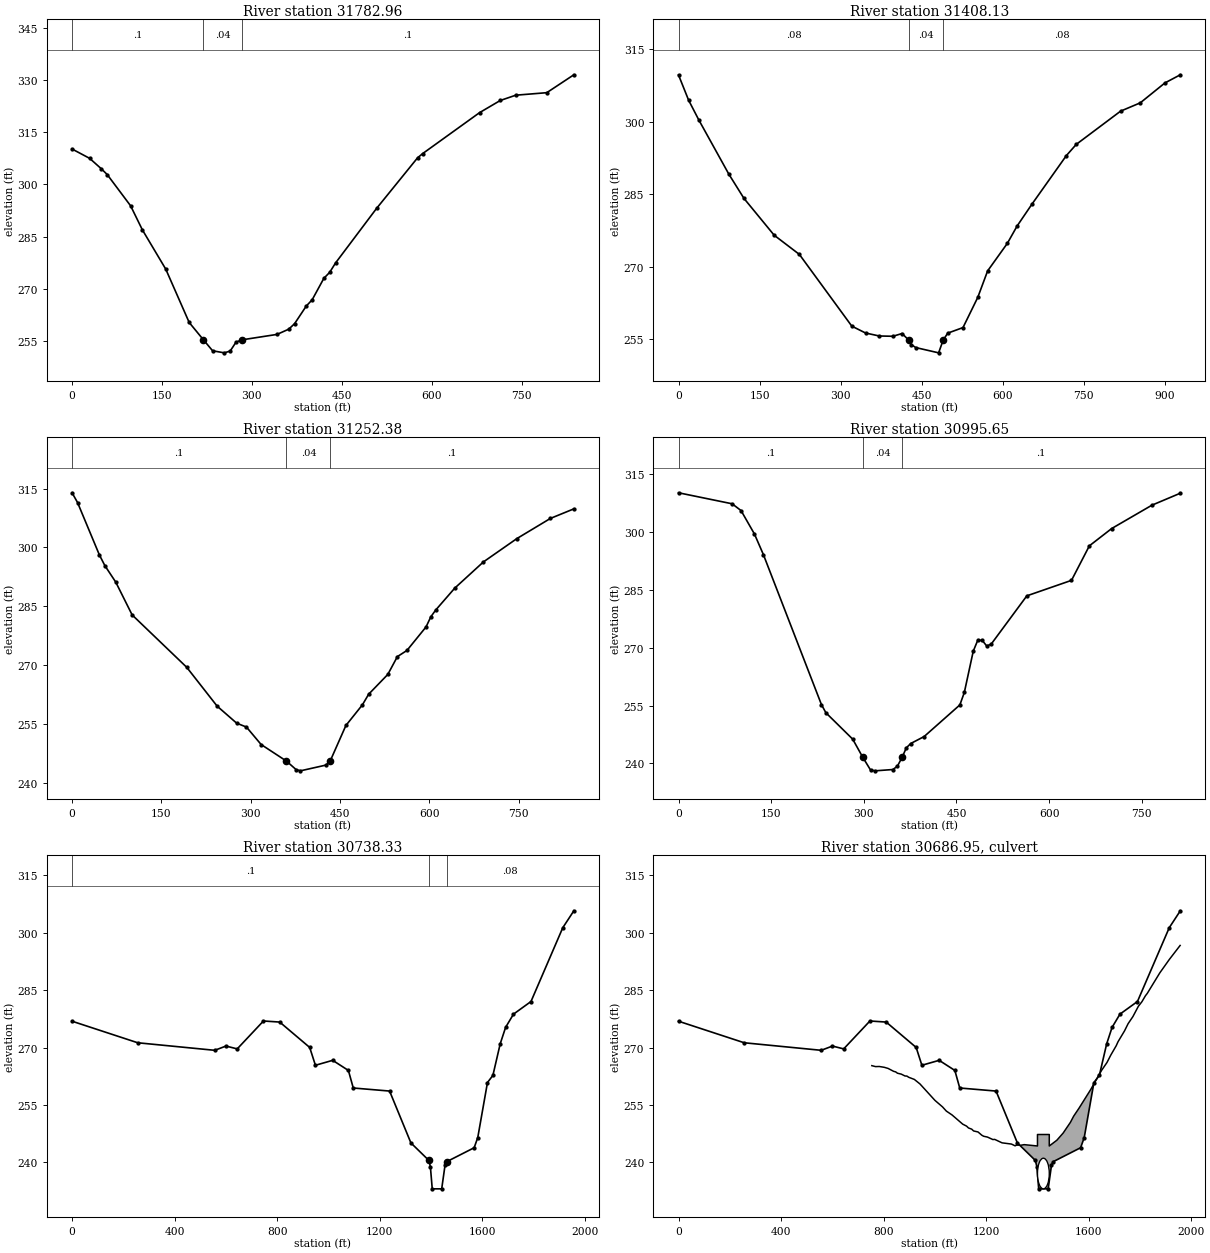
Type RM Length L Ch R = 1 ,31782.96,364.27,374.83,377.45
XS GIS Cut Line= 3
 1582905.7362204718891.3204483091582527.58901307718502.953046158
1582287.89997351718330.691261277
#Sta/Elev= 30
       0  310.18   29.31   307.5   48.85   304.5   58.62  302.85    97.7  293.87
  117.24  286.99  156.32   275.7   195.4  260.39  219.22   255.4  234.48  252.26
  254.02  251.67  263.79  252.18  273.56  254.74  283.33   255.4  341.95  256.96
  361.49  258.46  371.26  260.04   390.8  265.11  400.57  266.89  420.11  273.06
  429.88  274.79  439.65  277.48  508.05  293.13  576.54  307.67  585.16  308.89
  679.98  320.63  714.46  324.11  740.32  325.63  792.04  326.35  837.23  331.49
#Mann= 3 , 0 , 0
       0      .1       0  219.22     .04       0  283.33      .1       0
Bank Sta=219.22,283.33
XS Rating Curve= 0 ,0
Exp/Cntr=0.3,0.1

Type RM Length L Ch R = 1 ,31408.13,149.44,155.75,164.01
XS GIS Cut Line= 4
1583240.39752086718771.1856225131583034.45210522718536.636676908
1582914.31727943718359.2947912221582605.39915597718101.863021687
#Sta/Elev= 30
       0  309.65   18.63  304.44   37.26   300.4   93.15  289.11   121.1   284.1
  176.99  276.48  223.57  272.51  320.59  257.66  345.95  256.24  371.32  255.62
  396.68  255.56  413.59  256.13  425.84  254.78   430.5  253.85  438.96  253.22
  481.23  252.13  489.69  254.78  498.14  256.21  526.33  257.36  553.67  263.61
  571.89  269.09  608.34  274.79  626.57  278.41   653.9  282.91  717.68  292.98
  735.91  295.29  817.92  302.17  854.36  303.89  899.92  308.01  928.45   309.7
#Mann= 3 , 0 , 0
       0     .08       0  425.84     .04       0  489.69     .08       0
Bank Sta=425.84,489.69
XS Rating Curve= 0 ,0
Exp/Cntr=0.3,0.1

Type RM Length L Ch R = 1 ,31252.38,293.29,256.73,191.94
XS GIS Cut Line= 6
1583300.46493375718665.3525616971583143.14551899718479.429617018
1583088.79881211718390.7586741751583068.77634113718299.227378353
1583031.59175222718256.3220834141582731.25468773718087.561256737
#Sta/Elev= 30
       0  313.94    9.17  311.46   45.85   298.1   55.02  295.38   73.36  291.16
  100.87   282.8  192.56  269.44  243.55  259.55  276.39   255.2  292.81  254.21
  317.44  249.76  360.01  245.53  376.21  243.36  383.38  243.05  426.37  244.52
  433.54   245.6  459.77  254.61  487.56  259.89  498.02  262.59  530.14  267.63
   546.2  272.17  562.26  273.74  594.38  279.75  602.41  282.33  610.43  284.02
  642.55  289.63  690.73  296.32  746.93  302.27  803.14   307.4  842.53  309.84
#Mann= 3 , 0 , 0
       0      .1       0  360.01     .04       0  433.54      .1       0
Bank Sta=360.01,433.54
XS Rating Curve= 0 ,0
Exp/Cntr=0.3,0.1

Type RM Length L Ch R = 1 ,30995.65,269.95,257.31,248.2
XS GIS Cut Line= 2
1583555.03635025718253.4617304061582768.43927664718050.376667783
#Sta/Elev= 30
       0  310.09   86.75  307.24  101.21  305.48   122.9  299.41  137.36  294.09
  231.35  255.24  238.57  253.12  281.95  246.29  298.22  241.61  310.87  238.29
   318.1  238.08  347.02  238.42  354.25  239.27  362.08   241.6  368.71  244.02
  375.94  245.16  397.62  246.96  455.46  255.15  462.69  258.38  477.15  269.07
  484.38  271.88  491.61  271.89  498.84  270.43  506.07  270.87   563.9   283.4
   636.2  287.41  665.12  296.35  701.27  300.83  766.33  306.87  812.39  309.98
#Mann= 3 , 0 , 0
       0      .1       0  298.22     .04       0  362.08      .1       0
Bank Sta=298.22,362.08
XS Rating Curve= 0 ,0
Exp/Cntr=0.5,0.3

Type RM Length L Ch R = 1 ,30738.33,104.3,102.2,107.47
BEGIN DESCRIPTION:
Center of channel lowered to culvert invert based on survey info. and photos.
END DESCRIPTION:
XS GIS Cut Line= 6
1584710.48517971718344.7782733141583801.85121493718070.505452573
1583543.35808486717976.9180854261583103.03972511717908.963770255
1582963.82578823717896.6946585331582816.37260322 717895.68149744
#Sta/Elev= 30
       0   276.9  256.12  271.27  556.44   269.3  600.29  270.41  644.14  269.67
  746.47  276.96  809.92  276.68  926.81  270.05  949.13  265.39 1016.49  266.68
 1077.73  264.04 1096.76  259.45 1238.45  258.65 1321.59   245.1 1391.72  240.52
 1397.58  238.87 1404.77   233.1 1441.68   233.1 1454.54  239.21 1460.83  240.18
 1568.25  243.84 1582.35   246.5 1620.17  260.88 1641.35  262.74 1669.88     271
 1690.97   275.3 1721.69  278.75 1789.93  282.05 1913.97  301.34 1957.14  305.76
#Mann= 3 , 0 , 0
       0      .1       0 1391.72     .04       0 1460.83     .08       0
Bank Sta=1391.72,1460.83
XS Rating Curve= 0 ,0
Exp/Cntr=0.5,0.3

Type RM Length L Ch R = 2 ,30686.95,,,
BEGIN DESCRIPTION:
Theodore Road, MDE Bridge #: CE032907PF-2
Top of road obtained from DEM.
Opening from MDE2 bridge/culvert surveys.
END DESCRIPTION:
Bridge Culvert--1,0,-1,-1, 0
Deck Dist Width WeirC Skew NumUp NumDn MinLoCord MaxHiCord MaxSubmerge Is_Ogee
35.6,31,2.6,0, 60, 60, , , 0.98, 0, 2,2,,
  753.88  768.49  783.11  802.86  817.47  839.39   846.7     854  868.61  883.22
  890.53  897.83  919.75  941.66 1000.01 1029.52 1044.49 1066.95 1108.45 1123.41
 1130.89 1143.35 1150.78 1168.15 1182.81 1190.14  1204.8    1226 1233.16 1261.83
 1298.42 1312.62 1319.72 1333.92 1348.11    1400    1400    1446    1446 1475.63
 1500.01 1528.35 1540.98 1562.12 1607.58 1649.94 1671.12 1686.04 1707.13 1714.16
 1739.38 1753.41 1772.27 1793.38 1807.46 1821.12 1828.12 1877.14 1914.35 1956.36
  265.29  265.04  265.07  264.85  264.56  263.79  263.67  263.31  263.08  262.59
  262.57  262.25  261.69  260.51  256.22  254.52  253.42   252.4     250  249.49
  249.01   248.7  248.23  247.96  247.11  246.84  246.63  245.98  246.02  245.12
   244.8  244.34  244.57  244.48  244.65   244.3   247.3   247.3   244.3  245.81
  247.67  250.47  252.08  254.19  259.05  264.05  266.12  268.06   270.5  271.54
  274.36  276.25  278.12  280.79  282.01  283.56  284.16  289.54  293.05   296.7
                                                                                
                                                                                
                                                                                
                                                                                
                                                                                
                                                                                
  270.76  307.35   329.3  351.26  403.06  512.69  541.92  571.16  585.78  651.56
  666.17  717.33  731.95  746.57  817.47     854  890.53  919.75  941.66 1000.01
 1029.52 1044.49 1066.95 1108.45 1123.41 1130.89 1143.35 1150.78 1168.15 1190.14
  1204.8    1226 1233.16 1261.83 1298.42 1312.62 1319.72 1348.11 1389.95    1395
    1395    1441    1441 1454.48 1475.63 1500.01 1528.35 1540.98 1607.58 1649.94
 1671.12 1707.13 1714.16 1739.38 1753.41 1772.27 1793.38 1807.46 1877.14 1907.74
  269.88  269.69  269.24  268.42  267.57  266.21  266.34     266  266.23  265.84
  265.46  265.48  265.24  265.44  264.56  263.31  262.57  261.69  260.51  256.22
  254.52  253.42   252.4     250  249.49  249.01   248.7  248.23  247.96  246.84
  246.63  245.98  246.02  245.12   244.8  244.34  244.57  244.65  244.25   244.3
   247.3   247.3   244.3  244.68  245.81  247.67  250.47  252.08  259.05  264.05
  266.12   270.5  271.54  274.36  276.25  278.12  280.79  282.01  289.54  292.52
                                                                                
                                                                                
                                                                                
                                                                                
                                                                                
                                                                                
BR Coef=-1 , 0 , 0 ,, 0 ,,,0.8,0,,0,
WSPro=,,,, 1 ,,,, 0 ,,,, 0 ,,,,-1 ,-1 ,-1 , 0 , 0 , 0 , 0 , 0
Culvert=9,8,46,31,0.017,0.7,1,60,1,233.1,1423,233.1,1418,Culvert #1  , 0 ,35.6
Culvert Bottom n=0.017
BC Design=,, 0 ,, 0 ,,,,,,
BC Use User HTab Curves=0
BC User HTab FreeFlow(D)= 0

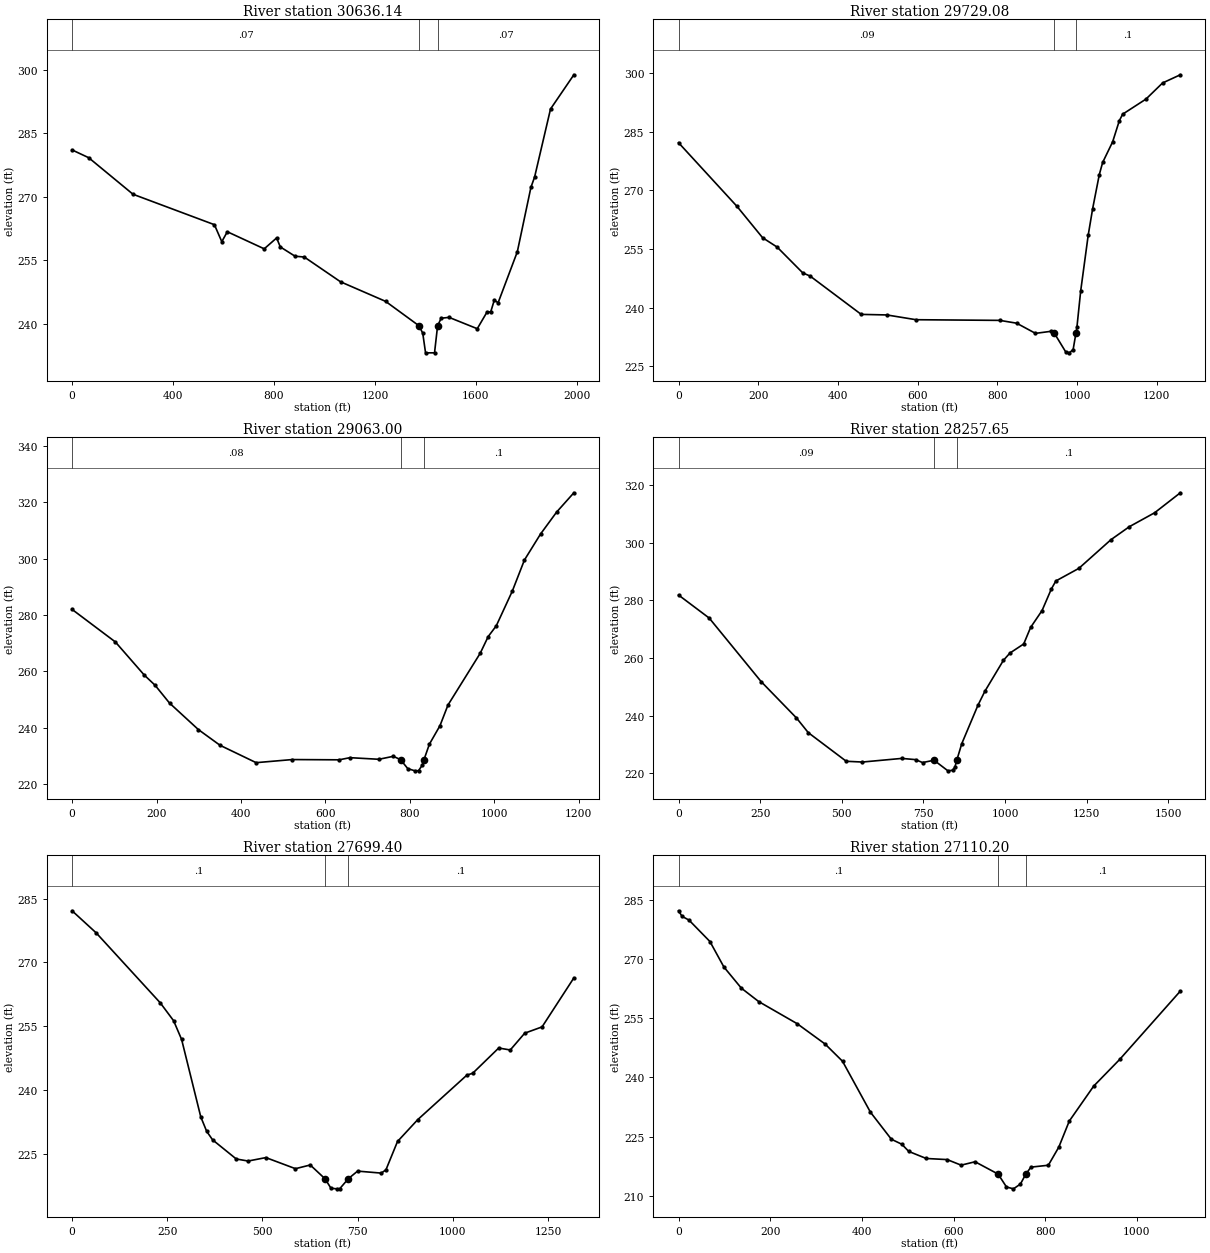
Type RM Length L Ch R = 1 ,30636.14,943.99,907.06,624.64
BEGIN DESCRIPTION:
Center of channel lowered to culvert invert based on survey info. and photos.
END DESCRIPTION:
XS GIS Cut Line= 6
 1584739.6357089718249.1213517191583833.88868755717975.708601967
1583568.92274219717880.1489035931583114.34487911717809.588846862
1582970.46653371717796.8491646051582815.00286871717795.690878734
#Sta/Elev= 30
       0  281.11   65.86  279.27  241.49  270.62  563.95  263.42  593.19   259.4
  615.11  261.75  761.29  257.71  810.41  260.28  825.03  258.16  883.47  255.96
  919.99  255.77 1063.65  249.91 1242.21  245.28 1374.63   239.5 1389.41  237.74
  1400.5   233.1 1436.08   233.1 1448.13  239.46 1462.23  241.29 1493.76  241.49
 1605.33  238.81 1644.41  242.79 1658.53  242.76 1672.65  245.53 1688.13  244.97
 1764.08  257.01 1817.94  272.25 1832.59   274.7 1895.62  290.79 1988.09  298.89
#Mann= 3 , 0 , 0
       0     .07       0 1374.63     .04       0 1448.13     .07       0
Bank Sta=1374.63,1448.13
XS Rating Curve= 0 ,0
Exp/Cntr=0.5,0.3

Type RM Length L Ch R = 1 ,29729.08,642.48,666.08,630.31
XS GIS Cut Line= 5
1583501.94134529716882.3687450891583094.09117901717364.749906152
 1582951.2401056717501.3900633751582810.45933752717656.662969306
1582626.20215584717776.740683198
#Sta/Elev= 30
       0  282.14  146.67  265.86  210.83  257.85   247.5  255.44  311.67  248.85
     330  248.05  458.33  238.24   522.5   238.1  595.83  236.88  806.05  236.71
  848.27  235.99  895.51  233.39  933.31   233.9  942.76  233.44   971.1  228.69
  980.55  228.41     990  229.26  996.99  233.44  999.45  234.93  1008.9  244.22
  1027.8  258.51 1038.96  265.29 1055.67  274.01 1064.03  277.09 1089.09  282.37
  1105.8  287.75 1114.16  289.43 1172.65  293.29 1214.42  297.42 1258.89  299.51
#Mann= 3 , 0 , 0
       0     .09       0  942.76     .04       0  996.99      .1       0
Bank Sta=942.76,996.99
XS Rating Curve= 0 ,0
Exp/Cntr=0.3,0.1

Type RM Length L Ch R = 1 ,29063.00,565.84,805.35,747.31
XS GIS Cut Line= 3
1582761.16151989716657.6205243021582260.89926645717371.109311983
1582027.88389169717586.272585273
#Sta/Elev= 30
       0     282  102.59  270.45  170.98  258.71  196.63  255.09  230.83  248.77
  299.22  239.36  350.52  233.79  436.01  227.63   521.5  228.73  632.64  228.64
  658.29   229.4  726.68  228.83  760.88  229.88  777.98  228.71  795.08  225.53
  812.17  224.73  820.72  224.79  829.27   226.7   833.6  228.71  846.37  234.19
  871.39  240.73  890.45  248.09  966.67  266.42  985.73  272.38 1004.78  276.17
 1042.89  288.53 1071.48  299.52 1109.59  308.73  1147.7  316.52 1188.56  323.37
#Mann= 3 , 0 , 0
       0     .08       0  777.98     .04       0   833.6      .1       0
Bank Sta=777.98,833.6
XS Rating Curve= 0 ,0
Exp/Cntr=0.3,0.1

Type RM Length L Ch R = 1 ,28257.65,366.75,558.24,552.2
XS GIS Cut Line= 4
1582670.95029384716602.9470539841582241.76355186 716712.29399462
1581675.89313398716794.3042000981581156.49516596716843.510323405
#Sta/Elev= 30
       0   281.9   93.91  273.89  252.83  251.82  361.18  239.16   397.3  234.06
  513.63  224.11  563.14  223.85  683.38  225.11  725.82  224.69  747.04  223.67
  782.41  224.47  824.85  220.79  838.99  220.98  846.07  222.04  852.55  224.72
  867.28  230.25   916.8   243.6  938.02  248.46   994.6  259.18 1014.68  261.73
 1056.87  264.89 1077.96  270.63 1113.12  276.52 1141.24  283.94 1155.31  286.79
 1225.62  291.16 1324.06  301.14 1380.31  305.65 1457.66  310.49  1536.4  317.44
#Mann= 3 , 0 , 0
       0     .09       0  782.41     .04       0  852.55      .1       0
Bank Sta=782.41,852.55
XS Rating Curve= 0 ,0
Exp/Cntr=0.3,0.1

Type RM Length L Ch R = 1 ,27699.40,574.62,589.2,586.33
XS GIS Cut Line= 4
1582635.41253817 716510.002154411582329.24110435716488.132766292
1581869.98395365716266.705211505 1581407.9931294716072.614391834
#Sta/Elev= 30
       0  282.13   63.16  276.95  231.59  260.48  266.68  256.27  287.73  251.86
  338.04  233.65  353.58  230.25  369.12  228.25  431.29  223.75  462.37  223.27
     509  224.08  586.71  221.47  625.57  222.34  664.42  219.09  679.97  216.87
  695.51  216.73  703.28  216.79   725.9  219.14  749.91   220.9  812.07  220.43
  824.39  221.21  854.76  227.87  907.91  233.01 1036.99  243.48 1052.17  243.91
 1120.51  249.85 1150.88  249.39 1188.84  253.34  1234.4  254.82 1317.91  266.34
#Mann= 3 , 0 , 0
       0      .1       0  664.42     .04       0   725.9      .1       0
Bank Sta=664.42,725.9
XS Rating Curve= 0 ,0
Exp/Cntr=0.3,0.1

Type RM Length L Ch R = 1 ,27110.20,517.2,482.98,417.29
XS GIS Cut Line= 3
1582966.18703358716127.2878621821582127.11986801 715768.77734597
1581949.26048563715728.171528816
#Sta/Elev= 30
       0  282.17    7.61  280.77   22.84  279.81   68.51  274.39   98.96  267.95
  137.02   262.6  175.08  259.19  258.81  253.61  319.71  248.47  357.77  244.11
  418.67  231.23  464.34  224.38  487.18  223.11   502.4  221.29  540.47  219.51
  586.14  219.23  616.59  217.82  647.04  218.68  697.33  215.56  715.55   212.3
  730.77  211.83  745.99  213.04  757.33  215.47  768.83  217.32  806.89   217.8
  829.73  222.38  852.56  228.97  905.85  237.82  962.71  244.58 1094.88  261.85
#Mann= 3 , 0 , 0
       0      .1       0  697.33     .04       0  757.33      .1       0
Bank Sta=697.33,757.33
XS Rating Curve= 0 ,0
Exp/Cntr=0.3,0.1