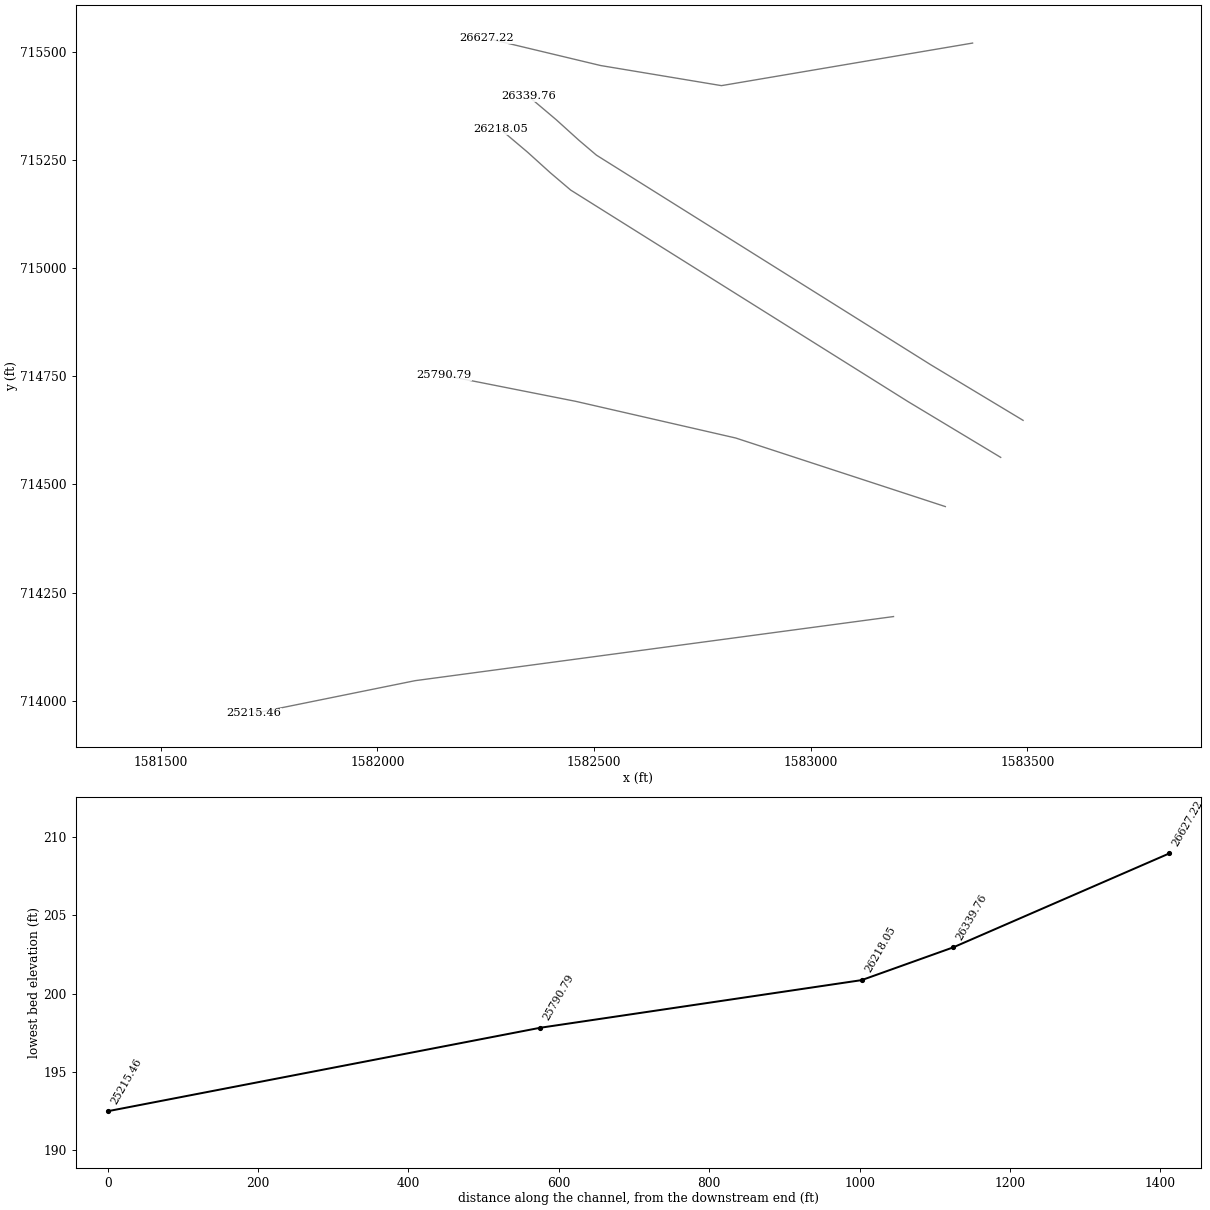
HEC-RAS study PrincipioCreek.prj: PrincipioCreek

--- PrincipioCreek.g01 (geometry) --- (continued)

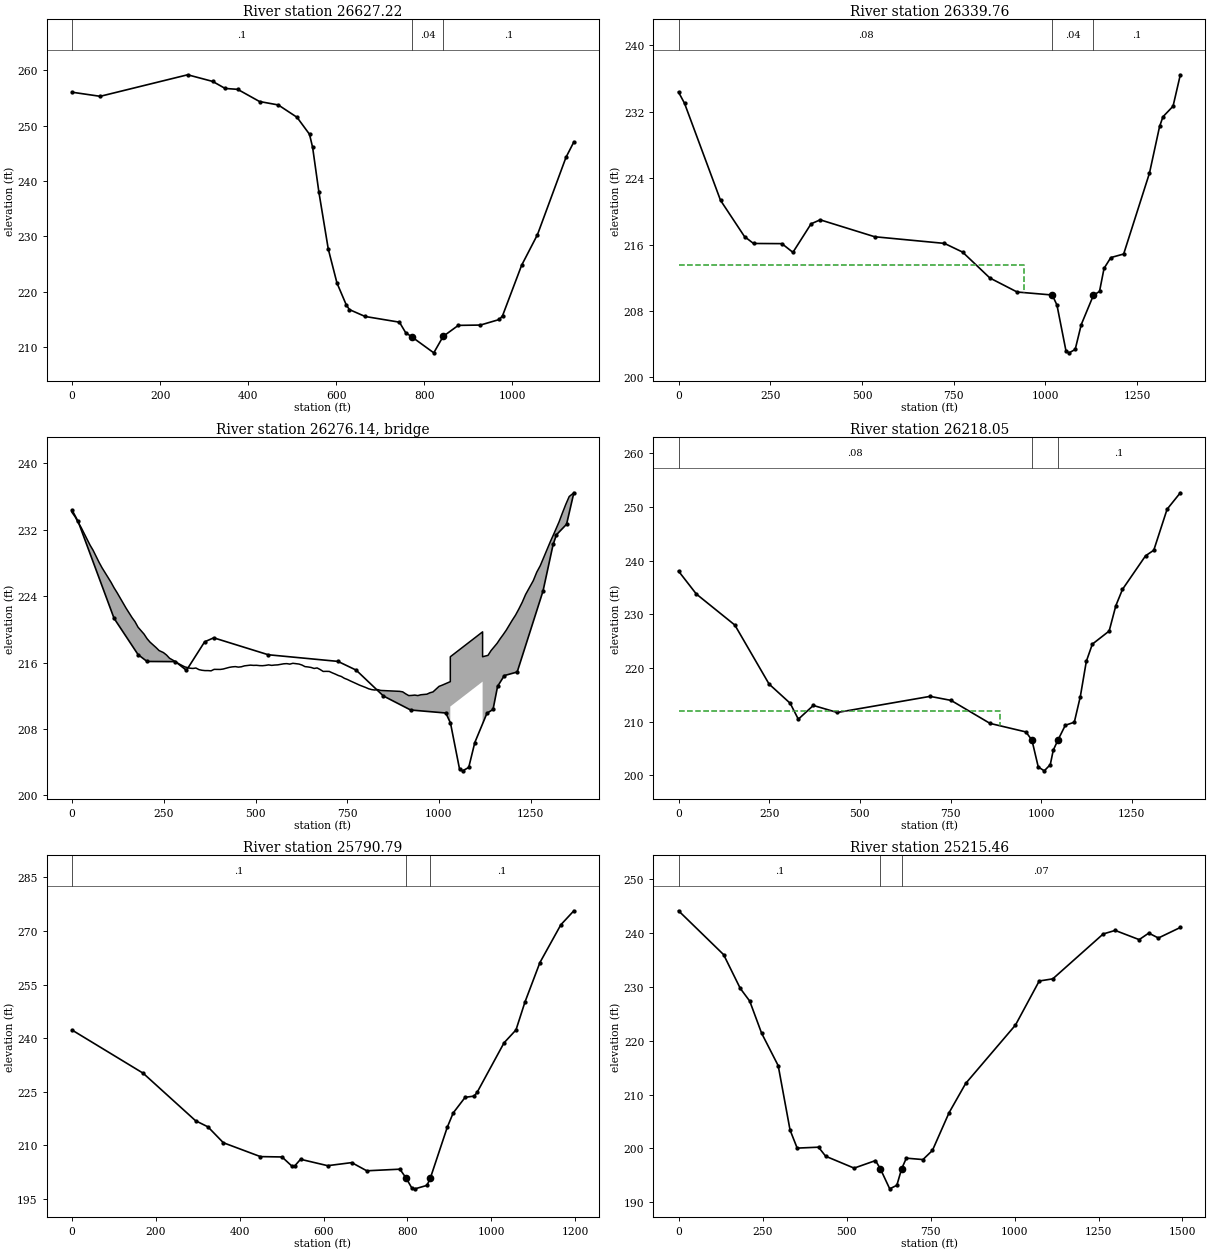
Type RM Length L Ch R = 1 ,26627.22,285.6,287.46,227.09
XS GIS Cut Line= 4
1583373.50438751715520.4123415951582793.96560211715422.000095025
1582515.13090345715468.4725447741582252.69824588715531.347035661
#Sta/Elev= 30
       0  256.03    63.9  255.29  262.71  259.18  319.51  257.98  347.91  256.71
  376.31  256.55  426.01  254.35  468.61  253.73  511.22   251.5  539.62  248.43
  546.72  246.05  560.92  237.99  582.22  227.71  602.03  221.56  623.32  217.58
  630.41  216.76   665.9  215.52  743.96  214.49  758.15  212.59  772.35  211.82
  822.02  208.95  843.31  211.92  877.71  213.91   928.1  213.97  971.29  214.98
  978.49  215.69 1021.68  224.77 1057.67   230.3 1122.45  244.26 1140.38  247.05
#Mann= 3 , 0 , 0
       0      .1       0  772.35     .04       0  843.31      .1       0
Bank Sta=772.35,843.31
XS Rating Curve= 0 ,0
Exp/Cntr=0.5,0.3

Type RM Length L Ch R = 1 ,26339.76,150.74,121.71,154.56
BEGIN DESCRIPTION:
Center of channel lowered 1.5 ft based on bridge survey info.
END DESCRIPTION:
XS GIS Cut Line= 6
1583490.02182344714648.186561391 1583277.2135504714776.521321461
1582505.48309743715261.2657621351582464.78755799715295.932332754
 1582412.6166335715343.2122330671582348.45914631715397.499337614
#Sta/Elev= 30
       0  234.37   16.35  233.02  114.44  221.33  179.84  216.96  204.36  216.13
   281.7  216.11  311.79  215.06  361.34   218.5  386.12  218.98  534.77  216.94
  724.72  216.14  774.27  215.09   848.6  211.97  922.93  210.28 1018.71  209.92
 1031.47  208.71 1056.32  203.13 1064.61  202.95 1081.18  203.36 1097.75  206.36
  1130.9  209.89 1147.47  210.35 1159.85  213.13 1178.25  214.43 1213.31  214.86
 1283.72  224.62 1311.23  230.23  1320.4   231.4 1347.91  232.67 1367.76  236.46
#Mann= 3 , 0 , 0
       0     .08       0 1018.71     .04       0  1130.9      .1       0
#XS Ineff= 2 , 0
       0  941.83   213.5               0
Permanent Ineff=
       F       F
Bank Sta=1018.71,1130.9
XS Rating Curve= 0 ,0
Exp/Cntr=0.5,0.3

Type RM Length L Ch R = 3 ,26276.14,,,
BEGIN DESCRIPTION:
Belvidere Road, MDE Bridge #: CE032907PF-1
Top of road obtained from DEM.
Opening from MDE2 bridge/culvert surveys.
END DESCRIPTION:
Bridge Culvert--1,0,-1,-1, 0
Deck Dist Width WeirC Skew NumUp NumDn MinLoCord MaxHiCord MaxSubmerge Is_Ogee
45.4,31,2.6,0, 149, 148, , , 0.98, 0, 2,2,,
       0    8.17   16.35   24.52    32.7   40.87   49.05   57.22   65.39   73.57
   81.74   89.92   98.09  106.27  114.44  122.62  130.79  138.96  147.14  155.31
  163.49  171.66  179.84  188.01  196.18  204.36  212.53  220.71  228.88  237.06
  249.11  257.41  265.71     274   282.3   290.6  298.89  307.19  312.81  321.07
  329.33  337.58  345.84   354.1  362.36  370.62  378.88  387.14  395.39  403.65
  411.91  420.17  428.43  436.69  444.95  453.21  461.46  469.72  477.98  486.24
   494.5  502.76  511.02  519.27  527.53  535.79  544.05  552.31  560.57  568.83
  577.09  585.34   593.6  601.86  610.12  618.38  626.64   634.9  643.15  651.41
  659.67  667.93  676.19  684.45  692.71  700.97  709.22  717.48  725.74     734
  742.26  750.52  758.78  767.03  775.29  783.55  791.81  800.07  808.33  816.59
  824.85   833.1  841.36  884.62  892.88  901.14   909.4  917.66  925.91  934.17
  942.43  950.69  958.95  967.21  975.47  983.73  991.98 1000.24  1008.5    1031
    1031    1119    1119 1133.72    1142 1150.29 1158.57 1166.86 1175.15 1183.43
 1191.72 1199.48 1208.68 1217.87 1227.07 1236.26 1245.46 1257.24 1266.68 1276.13
 1285.58 1295.03 1304.47 1313.92 1327.56 1336.73  1345.9 1355.07 1367.76
  234.08  233.57   232.9   232.3  231.59   230.9  230.15  229.54  228.81  228.08
  227.42  226.84  226.25  225.67  225.01  224.43  223.81   223.2  222.56     222
  221.42  220.92  220.26  219.84  219.43  218.88  218.46  218.13  217.81  217.45
   217.2  216.91  216.52  216.31   216.1  215.86  215.67  215.48  215.41  215.32
  215.29  215.34  215.15  215.07  215.03  215.03     215  215.18  215.17  215.17
  215.22  215.32  215.42  215.48  215.51  215.45  215.49   215.6  215.64  215.69
  215.66  215.67  215.63  215.62  215.66  215.72  215.66   215.7  215.72  215.78
  215.85  215.87  215.81  215.91  215.87  215.82   215.7  215.51  215.47  215.41
  215.29  215.35  215.16  214.93  214.94  214.93  214.76  214.61  214.44  214.32
   214.1  213.96  213.78  213.62  213.45  213.28  213.14     213  212.84  212.74
  212.69  212.74  212.64  212.54  212.53  212.47  212.23  212.02  212.04  212.08
  212.02  212.12  212.15  212.19  212.36  212.46  212.79  213.13  213.27   213.7
   216.7   219.7   216.7  216.87  217.44  217.87  218.32  218.87  219.37   219.9
  220.52  221.08  221.71  222.46  223.27  224.21  224.94  225.88   226.9  227.67
  228.67  229.67  230.66  231.58  232.97  234.05  235.08  236.01  236.46
                                                                                
                                                                                
                                                                                
                                                                                
                                                                                
                                                                                
                                                                                
                                                                                
                                                                                
                                                                                
                                                                                
                                                                                
   210.7   213.7
                                                                                
                                                                        
       0    8.17   16.35   24.52    32.7   40.87   49.05   57.22   65.39   73.57
   81.74   89.92   98.09  106.27  114.44  122.62  130.79  138.96  147.14  155.31
  163.49  171.66  179.84  188.01  196.18  204.36  212.53  220.71  228.88  237.06
  249.11  257.41  265.71     274   282.3   290.6  298.89  307.19  312.81  321.07
  329.33  337.58  345.84   354.1  362.36  370.62  378.88  387.14  395.39  403.65
  411.91  420.17  428.43  436.69  444.95  453.21  461.46  469.72  477.98  486.24
   494.5  502.76  511.02  519.27  527.53  535.79  544.05  552.31  560.57  568.83
  577.09  585.34   593.6  601.86  610.12  618.38  626.64   634.9  643.15  651.41
  659.67  667.93  676.19  684.45  692.71  700.97  709.22  717.48  725.74     734
  742.26  750.52  758.78  767.03  775.29  783.55  791.81  800.07  808.33  816.59
  824.85   833.1  841.36  849.62  857.88  866.14   874.4  882.66  890.91  899.17
  907.43  915.69  923.95  932.21  940.47   948.5     966     966    1054    1054
 1073.72    1082 1090.29 1098.57 1106.86 1115.15 1123.43 1131.72 1139.48 1148.68
 1157.87 1167.07 1176.26 1185.46 1197.24 1206.68 1216.13 1225.58 1235.03 1244.47
 1253.92 1267.56 1276.73  1285.9 1295.07 1304.24 1313.41 1322.58
  234.08  233.57   232.9   232.3  231.59   230.9  230.15  229.54  228.81  228.08
  227.42  226.84  226.25  225.67  225.01  224.43  223.81   223.2  222.56     222
  221.42  220.92  220.26  219.84  219.43  218.88  218.46  218.13  217.81  217.45
   217.2  216.91  216.52  216.31   216.1  215.86  215.67  215.48  215.41  215.32
  215.29  215.34  215.15  215.07  215.03  215.03     215  215.18  215.17  215.17
  215.22  215.32  215.42  215.48  215.51  215.45  215.49   215.6  215.64  215.69
  215.66  215.67  215.63  215.62  215.66  215.72  215.66   215.7  215.72  215.78
  215.85  215.87  215.81  215.91  215.87  215.82   215.7  215.51  215.47  215.41
  215.29  215.35  215.16  214.93  214.94  214.93  214.76  214.61  214.44  214.32
   214.1  213.96  213.78  213.62  213.45  213.28  213.14     213  212.84  212.74
  212.69  212.74  212.64  212.54  212.53  212.47  212.23  212.02  212.04  212.08
  212.02  212.12  212.15  212.19  212.36  213.27   213.7   216.7   219.7   216.7
  216.87  217.44  217.87  218.32  218.87  219.37   219.9  220.52  221.08  221.71
  222.46  223.27  224.21  224.94  225.88   226.9  227.67  228.67  229.67  230.66
  231.58  232.97  234.05  235.08  236.01  237.15  238.16  239.16
                                                                                
                                                                                
                                                                                
                                                                                
                                                                                
                                                                                
                                                                                
                                                                                
                                                                                
                                                                                
                                                                                
                                                           210.7   213.7
                                                                                
                                                                                
                                                                
BR Coef=-1 , 0 , 0 ,, 0 ,,,0.8,-1,,0,
WSPro=,,,, 1 ,,,, 0 ,,,, 0 ,,,,-1 ,-1 ,-1 , 0 , 0 , 0 , 0 , 0
BC Design=,, 0 ,, 0 ,,,,,,
BC Use User HTab Curves=0
BC User HTab FreeFlow(D)= 0

Type RM Length L Ch R = 1 ,26218.05,400.25,427.26,441.46
BEGIN DESCRIPTION:
Center of channel lowered 1.5 ft based on bridge survey info.
END DESCRIPTION:
XS GIS Cut Line= 6
1583438.38011466714562.552841842 1583224.5412942714691.509077102
1582446.01207922715180.5622009491582398.77272148715220.803135306
1582346.72450866715267.9718282221582283.86492218715321.160709038
#Sta/Elev= 30
       0  238.03   49.05  233.77  155.31  227.99  249.71  217.01  307.79  213.44
  330.34  210.47  371.64  213.03  437.71  211.72  693.73  214.72  751.54  213.97
   858.9  209.69     958   208.1  974.52  206.58  991.97  201.58 1008.54  200.86
 1025.11  202.01  1033.4  204.71 1045.84  206.53 1066.54  209.34  1091.4  209.91
 1107.97  214.68 1124.54  221.24 1141.11  224.44  1187.5  226.88 1205.89  231.59
 1224.28  234.64 1287.84  240.88 1310.57  241.92 1347.25  249.55 1383.75  252.61
#Mann= 3 , 0 , 0
       0     .08       0  974.52     .04       0 1045.84      .1       0
#XS Ineff= 2 , 0
       0  886.02     212               0
Permanent Ineff=
       F       F
Bank Sta=974.52,1045.84
XS Rating Curve= 0 ,0
Exp/Cntr=0.5,0.3

Type RM Length L Ch R = 1 ,25790.79,528.12,575.33,587.85
XS GIS Cut Line= 4
1583310.62989663714448.8123232871582826.76968428714607.365387201
1582457.72375964714692.1092662221582154.28599933714752.250083596
#Sta/Elev= 30
       0  242.25  169.42  230.19  294.65  216.88  324.11  215.17  360.95  210.72
  449.34  206.84   500.9  206.74  523.54  204.28  530.72  204.16  545.09  206.09
  609.73   204.3  667.18  205.16  703.09  202.87   782.1  203.32  796.46  200.92
  810.83  198.01  818.01  197.82  846.74  198.79  855.07  200.93  894.96  214.99
  909.24  219.05  937.78  223.43  959.19  223.77  966.32  224.81 1030.55  238.67
 1059.09  242.29  1080.5  250.09 1116.18  261.14 1166.14  271.72 1197.17  275.63
#Mann= 3 , 0 , 0
       0      .1       0  796.46     .04       0  855.07      .1       0
#XS Ineff= 2 , 0
           545.1  205.99
Permanent Ineff=
       F       F
Bank Sta=796.46,855.07
XS Rating Curve= 0 ,0
Exp/Cntr=0.3,0.1

Type RM Length L Ch R = 1 ,25215.46,608.73,607.05,597.65
XS GIS Cut Line= 3
1583191.04188633714194.5364146981582087.04579008714046.328719586
1581715.01422891713970.712548628
#Sta/Elev= 30
       0  244.16  134.19  236.01  183.63  229.75  211.88  227.38   247.2  221.42
  296.64  215.38  331.95  203.41  353.14  200.06  416.71  200.23  437.89  198.55
  522.65  196.34  586.21  197.74  600.34  196.26  628.59  192.49  649.78  193.15
   663.9  196.19  678.03  198.19  727.47  197.93  755.72  199.63  805.16  206.63
   854.6  212.07 1002.92  222.93 1073.55  231.11  1113.9  231.51  1263.9  239.85
 1299.62  240.51 1371.05   238.8 1399.62  240.01  1428.2   239.1 1493.54  241.06
#Mann= 3 , 0 , 0
       0      .1       0  600.34     .04       0   663.9     .07       0
#XS Ineff= 2 , 0
          416.83  200.19
Permanent Ineff=
       F       F
Bank Sta=600.34,663.9
XS Rating Curve= 0 ,0
Exp/Cntr=0.3,0.1