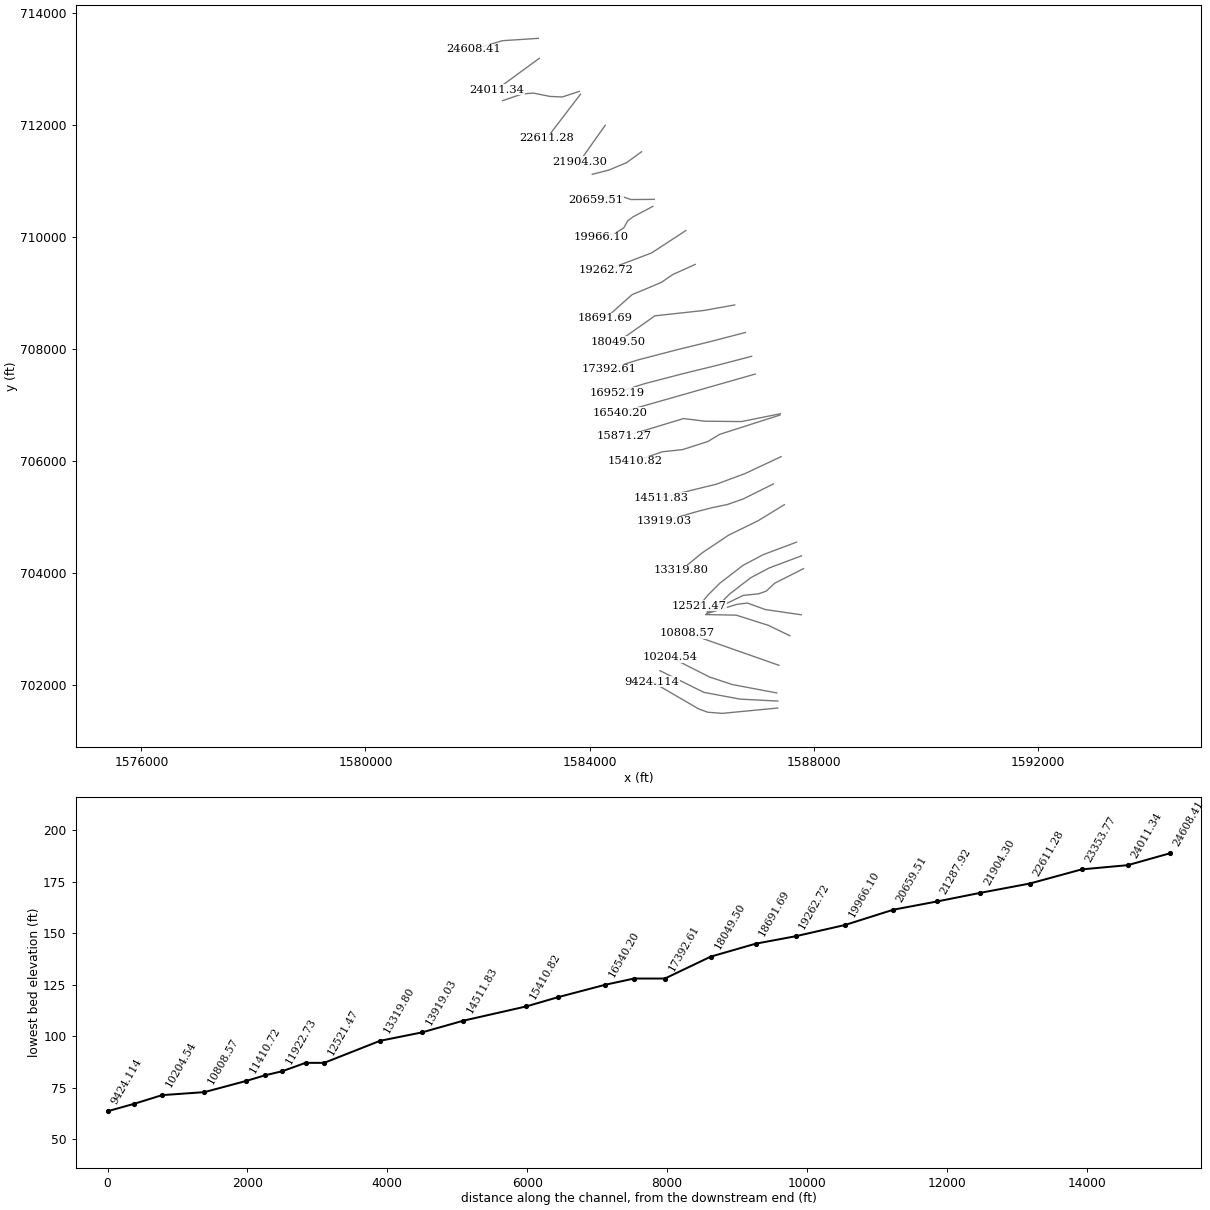
HEC-RAS study PrincipioCreek.prj: PrincipioCreek

--- PrincipioCreek.g01 (geometry) --- (continued)

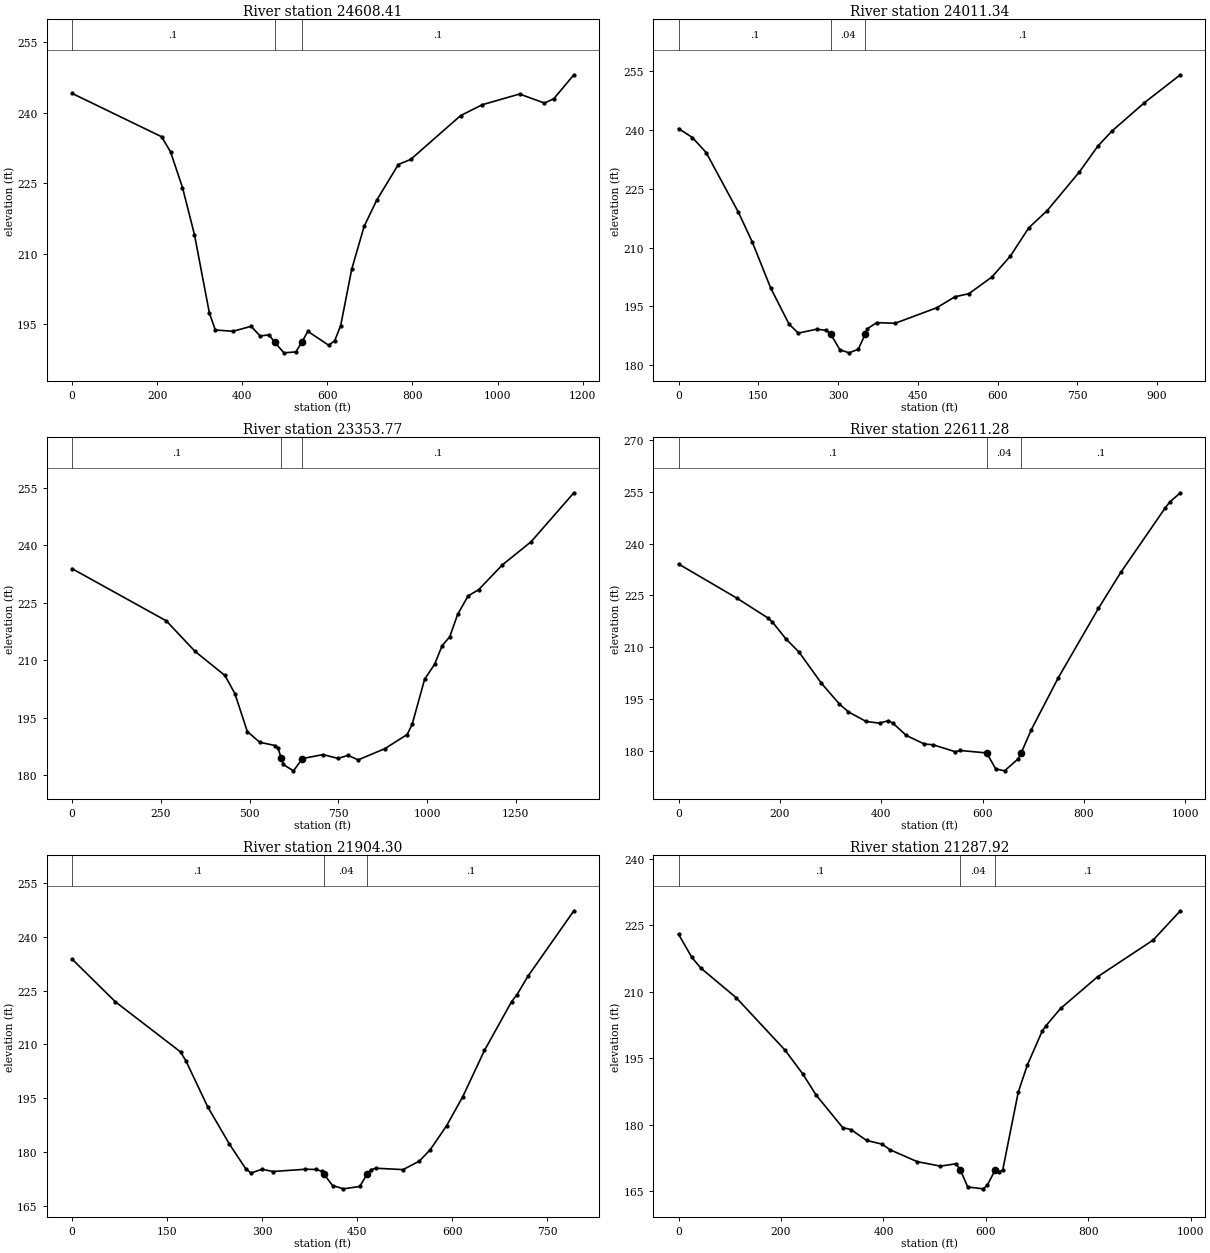
Type RM Length L Ch R = 1 ,24608.41,538.32,597.06,626.22
XS GIS Cut Line= 3
1583085.17924698713541.2126974761582443.95411709713498.867641732
1581929.76415446713344.610652953
#Sta/Elev= 30
       0  244.13  210.46  234.89   231.5  231.65  259.56  224.07  287.63  214.05
   322.7  197.35  336.73  193.71  378.82  193.45  420.92   194.5  441.96  192.44
  463.01  192.69  475.82  191.14  498.08  188.85  526.14  189.05  540.19191.1443
   554.2  193.43  603.31  190.46  617.34  191.44  631.37  194.65  657.24  206.64
  686.47  215.79   715.7  221.31  766.86  228.97   796.1  230.07  913.03  239.38
  964.18  241.71 1051.88  243.99 1110.35  242.06 1132.27  242.98 1179.45  248.09
#Mann= 3 , 0 , 0
       0      .1       0  475.82     .04       0  540.19      .1       0
Bank Sta=475.82,540.19
XS Rating Curve= 0 ,0
Exp/Cntr=0.3,0.1

Type RM Length L Ch R = 1 ,24011.34,678.57,657.58,500.53
XS GIS Cut Line= 2
1583103.32712798713184.3043704931582341.11612454712627.769352108
#Sta/Elev= 30
       0  240.42      26  238.12      52  234.27  112.68  219.01  138.68  211.43
  173.35  199.68  208.02  190.43  225.35  188.17  260.02  189.17  277.36  188.88
  286.02  187.97  303.36  183.93  320.69  183.13  338.03  184.04  351.38  187.99
  355.36   189.3   372.7  190.84  407.37  190.68  485.37  194.63  520.04  197.46
  546.05  198.23  589.38  202.49  624.05  207.83  658.72  215.05  693.39  219.46
  754.06  229.35  788.73  235.94  814.73  239.71   875.4  246.92  943.77  254.14
#Mann= 3 , 0 , 0
       0      .1       0  286.02     .04       0  351.38      .1       0
Bank Sta=286.02,351.38
XS Rating Curve= 0 ,0
Exp/Cntr=0.3,0.1

Type RM Length L Ch R = 1 ,23353.77,523.92,742.49,786.05
XS GIS Cut Line= 6
1583817.14378196 712594.49823688 1583514.6790981712494.684891179
1583296.90452568712503.7588316951582994.43984178712564.251768485
1582791.78850356712546.1038874541582446.97876394712428.142660722
#Sta/Elev= 30
       0  233.84  265.37  220.23  346.53  212.25  430.61  205.97  458.63  201.25
  493.66  191.34  528.69  188.55  572.81  187.67  580.08  187.05  589.14  184.41
  594.61  182.75  623.68  181.09  649.07   184.3  706.84  185.32  749.26  184.34
  777.53  185.13   805.8  183.95  880.74  186.86  943.99  190.57  958.04  193.24
  993.18     205  1021.3  208.91 1042.38  213.75 1063.85  216.06 1086.05   221.9
 1115.64  226.73 1145.24  228.35 1211.82   234.8  1293.2  240.88 1413.49  253.64
#Mann= 3 , 0 , 0
       0      .1       0  589.14     .04       0  649.07      .1       0
Bank Sta=589.14,649.07
XS Rating Curve= 0 ,0
Exp/Cntr=0.3,0.1

Type RM Length L Ch R = 1 ,22611.28,702.95,706.98,707.78
XS GIS Cut Line= 2
1583838.31630987712543.0792406051583236.41158888711756.671062484
#Sta/Elev= 30
       0  234.13   114.6  224.28   176.3   218.5  185.12  217.35  211.56  212.49
  238.01  208.56  282.08  199.55  317.34  193.59  334.97  191.31  370.23   188.5
  396.68  188.02  414.31  188.74  423.12  188.01  449.57  184.45  484.83  181.99
  502.46  181.75  546.53  179.72  555.35   180.1  608.24  179.39  625.87  174.76
   643.5   174.2  669.94  177.63  676.25  179.39  696.39  186.17  749.28  201.12
  828.61  221.25  872.69  231.67  960.84  250.45  969.66   252.1  990.32  254.76
#Mann= 3 , 0 , 0
       0      .1       0  608.24     .04       0  676.25      .1       0
Bank Sta=608.24,676.25
XS Rating Curve= 0 ,0
Exp/Cntr=0.3,0.1

Type RM Length L Ch R = 1 ,21904.30,642.39,616.38,549.42
XS GIS Cut Line= 2
1584279.91474834711989.5688690691583823.19307567711342.294445515
#Sta/Elev= 30
       0  233.83   68.54  221.88  171.34   207.9  179.91  205.35  214.18  192.56
  248.45  182.17  274.15  175.29  282.72  174.09  299.85  175.16  316.98  174.52
  368.39  175.15  385.52  175.09  394.09  174.58  397.22  173.88  411.22  170.61
  428.36  169.68  454.06  170.34   466.2  173.87  471.19  174.98  479.76  175.43
   522.6  175.05   548.3  177.43  565.43  180.61  591.13  187.26  616.84  195.43
   651.1  208.34  693.94  221.97  702.51  223.91  719.64  229.03  792.19  247.32
#Mann= 3 , 0 , 0
       0      .1       0  397.22     .04       0   466.2      .1       0
Bank Sta=397.22,466.2
XS Rating Curve= 0 ,0
Exp/Cntr=0.3,0.1

Type RM Length L Ch R = 1 ,21287.92,668.82,628.41,533.65
XS GIS Cut Line= 4
1584928.70149535711516.2116387781584662.53257349711322.634241089
1584344.94465542 711189.549780161584048.52926521711113.933609173
#Sta/Elev= 30
       0  222.95   25.97  217.74   43.28  215.34  112.52  208.64  207.73  196.82
  242.35  191.45  268.32   186.7  320.25  179.34  336.71  178.86  367.07  176.41
  397.43  175.59   412.6  174.33  465.73  171.64  511.27  170.62  541.63  171.16
  549.92  169.81   564.4  165.92  594.76   165.5  602.35  166.27  617.53  169.64
  625.12  169.32  632.71  169.74  663.07  187.33  680.69  193.42  709.58  201.04
  716.81  202.26   745.7  206.21  817.95  213.36  926.31  221.64  979.37  228.25
#Mann= 3 , 0 , 0
       0      .1       0  549.92     .04       0  617.53      .1       0
Bank Sta=549.92,617.53
XS Rating Curve= 0 ,0
Exp/Cntr=0.3,0.1

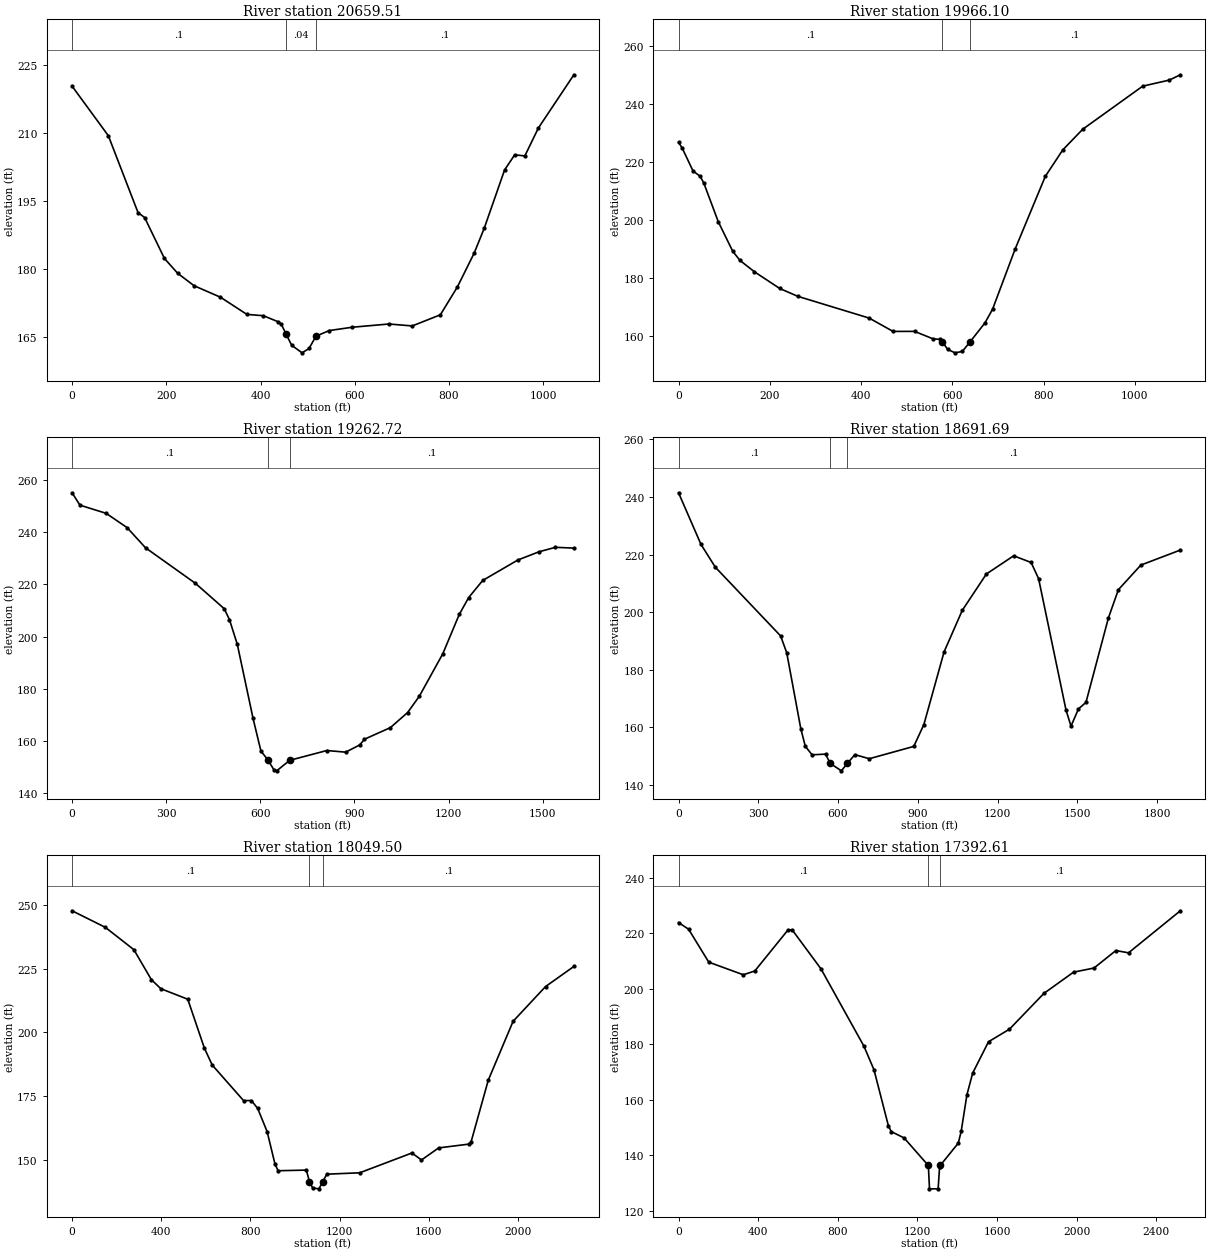
Type RM Length L Ch R = 1 ,20659.51,426.34,693.41,688.75
XS GIS Cut Line= 5
1585155.55000827710666.2858770041584741.17339128710663.261230201
1584623.21216458710702.5816390811584417.53617953710726.778813779
1584105.99755511710657.211936504
#Sta/Elev= 30
       0  220.37      77  209.42     140  192.44     154  191.35  196.01  182.32
  224.01  179.05  259.01  176.29  315.01  173.75  371.01  169.96  406.01  169.67
  436.52  168.37   443.9  167.81  454.56  165.56  466.04  163.15  488.17  161.47
  502.93  162.43  517.69  165.14  545.78  166.39  595.12  167.13  672.65  167.84
  721.98  167.41  781.69  169.87  817.55  175.97  853.41  183.48  874.93  189.02
  917.96  201.85  939.48  205.21     961  204.95  989.69  211.12 1065.04  222.88
#Mann= 3 , 0 , 0
       0      .1       0  454.56     .04       0  517.69      .1       0
Bank Sta=454.56,517.69
XS Rating Curve= 0 ,0
Exp/Cntr=0.3,0.1

Type RM Length L Ch R = 1 ,19966.10,737.01,703.38,656.78
XS GIS Cut Line= 6
1585131.35283357710542.2753566211584777.46915339710354.747252584
1584683.70510139710285.1803753081584611.11357723710158.145208046
1584465.93052898710067.4058028761584211.86019452709991.789631918
#Sta/Elev= 30
       0  226.65    7.92  224.73   31.69  216.81   47.53  214.91   55.45  212.59
   87.14  199.25  118.83  189.07  134.68  185.91  166.36  181.99  221.82  176.23
  261.43  173.52  417.93  166.01  470.23  161.41  517.25  161.43  557.56  158.87
  573.69  158.65  578.31   157.8  589.81  155.23  605.94  154.02  622.06  154.51
  638.47   157.7  671.82   164.4  688.33  169.07  737.86  189.87   803.9  214.92
  842.08  224.03   885.9  231.18 1017.36  246.05 1075.79  248.15 1099.86  249.98
#Mann= 3 , 0 , 0
       0      .1       0  578.31     .04       0  638.47      .1       0
Bank Sta=578.31,638.47
XS Rating Curve= 0 ,0
Exp/Cntr=0.3,0.1

Type RM Length L Ch R = 1 ,19262.72,556.49,571.03,557.14
XS GIS Cut Line= 4
1585719.04171437 710109.750858621585108.06305289709710.497475877
1584790.47513476709589.5116023421584294.46135037709403.184630126
#Sta/Elev= 30
       0  255.03   25.09  250.29  108.71  247.16   175.6  241.67  234.14  233.97
  393.02  220.38     485  210.65  501.72  206.47  526.81  196.96  576.98  168.62
  602.07  156.12  623.67  152.85  643.88  148.88  652.24  148.57  694.05  152.61
  812.26  156.35  872.19  155.72  917.13   158.5  932.11  160.68 1014.51   165.1
 1069.71   170.9  1107.1  177.16 1181.88  193.42 1234.22  208.43 1264.13  214.89
    1309  221.46 1421.16   229.3 1488.46  232.44  1540.8  234.15 1599.57  233.85
#Mann= 3 , 0 , 0
       0      .1       0  623.67     .04       0  694.05      .1       0
Bank Sta=623.67,694.05
XS Rating Curve= 0 ,0
Exp/Cntr=0.3,0.1

Type RM Length L Ch R = 1 ,18691.69,669.3,642.19,577.24
XS GIS Cut Line= 6
1585885.39729053709504.821490839 1585489.1685546709326.367327333
1585280.46792269709184.2089259031584923.55959573709032.976583943
1584760.22866642708966.4343534861584285.35911269708542.983796015
#Sta/Elev= 30
       0  241.49   84.45  223.57  138.19  215.67  383.86   191.8  406.89  185.96
  459.97  159.54  476.91  153.44  502.32  150.52  553.14  150.75  570.08  147.58
  612.42  144.95  635.24  147.58  663.24  150.57  717.49  149.16  884.74  153.43
  922.75  161.01  998.78  186.26  1067.2  200.67 1157.85  213.29 1260.45  219.61
  1326.1  217.29 1354.24  211.68 1457.41  166.04 1476.16  160.48  1504.3  166.46
 1532.44  168.72 1616.85  198.04 1654.36  207.84 1738.77  216.38 1887.32   221.6
#Mann= 3 , 0 , 0
       0      .1       0  570.08     .04       0  635.24      .1       0
Bank Sta=570.08,635.24
XS Rating Curve= 0 ,0
Exp/Cntr=0.3,0.1

Type RM Length L Ch R = 1 ,18049.50,648.1,656.89,659.57
XS GIS Cut Line= 4
1586591.65232745708781.9308962971586042.17666385 708683.30189234
1585166.31933285708587.3175273091584502.42747462708119.393747717
#Sta/Elev= 30
       0   247.7  149.35   241.2  277.36  232.44  355.59  220.72  398.27  217.14
  519.17  213.01  593.47  193.88  628.68  187.23  769.52  173.26  804.73  173.29
  832.89  170.18  875.14  161.13  910.35  148.45  924.44  145.76 1051.19  146.01
 1065.28  141.46 1079.36  139.02 1107.53  138.66 1125.16  141.45 1142.74  144.41
 1290.62  144.95    1525  152.72 1567.82  149.98 1644.89  154.71 1781.92  156.21
 1790.48   157.1 1867.56  181.27 1978.89  204.35 2124.48  217.98 2251.58  225.86
#Mann= 3 , 0 , 0
       0      .1       0 1065.28     .04       0 1125.16      .1       0
Bank Sta=1065.28,1125.16
XS Rating Curve= 0 ,0
Exp/Cntr=0.5,0.3

Type RM Length L Ch R = 1 ,17392.61,440.89,440.42,440.66
BEGIN DESCRIPTION:
Center of channel lowered to culvert invert based on survey info. and photos.
END DESCRIPTION:
XS GIS Cut Line= 6
1586784.30009413708290.6847084161586140.57131782708123.547258064
1585568.70947021707983.5810715411584868.32236286707801.396114782
1584597.93846875707715.9512597471584352.21266764 707629.94722937
#Sta/Elev= 30
       0  223.84   50.62  221.43  151.87  209.58  325.44  205.04   383.3  206.41
  549.64  221.14  571.34  221.18  715.52  207.19  931.72  179.32  982.16  170.84
 1054.23  150.76 1068.64  148.62  1133.5  146.31 1255.24   136.4 1261.05     128
 1304.44     128 1311.67  135.79 1314.92   136.4 1405.68  144.45 1420.14  148.65
 1449.06  161.83 1477.99  169.65 1557.54  180.93 1662.78  185.46 1836.41  198.36
 1984.85  205.98 2087.63  207.46 2197.75  213.77 2261.08  212.93 2521.41  228.07
#Mann= 3 , 0 , 0
       0      .1       0 1255.24     .04       0 1314.92      .1       0
Bank Sta=1255.24,1314.92
XS Rating Curve= 0 ,0
Exp/Cntr=0.5,0.3

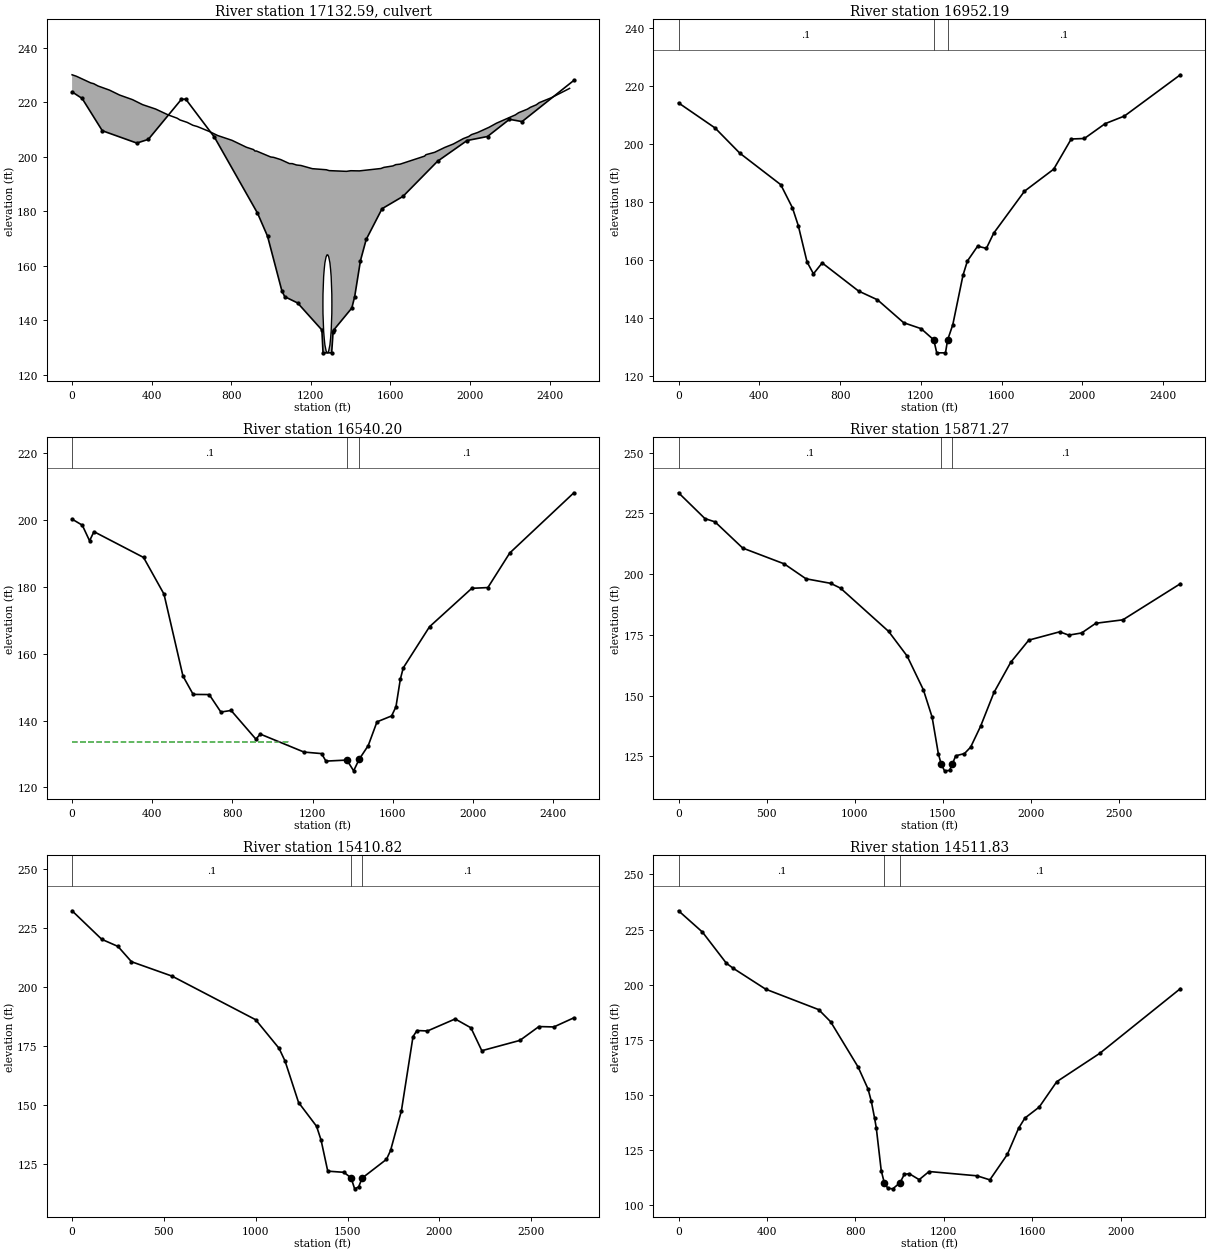
Type RM Length L Ch R = 2 ,17132.59,,,
BEGIN DESCRIPTION:
JFK Memorial Hwy, MDE Bridge #: CE032907FS-3
Top of road obtained from DEM.
Opening from MDE2 bridge/culvert surveys.
END DESCRIPTION:
Bridge Culvert--1,0,-1,-1, 0
Deck Dist Width WeirC Skew NumUp NumDn MinLoCord MaxHiCord MaxSubmerge Is_Ogee
140.2,160,2.6,0, 60, 60, , , 0.98, 0, 2,2,,
       0    21.7   94.02  108.48  130.18  188.03  238.66  303.75  354.37  419.46
  484.55  527.94  542.41  578.57   607.5  629.19  688.51  731.75  803.82  875.88
  911.92  919.12  926.33   998.4 1012.81 1048.84 1092.08  1106.5 1128.12 1149.74
 1207.39 1277.37 1291.84 1378.62 1400.31  1443.7 1552.17 1566.63 1612.04 1626.51
 1648.21 1771.19 1778.43 1821.83 1872.47 1915.88 1966.52 1992.62  2007.3 2036.66
 2095.39  2132.1 2227.54 2243.56 2288.06 2302.89 2332.56 2347.39 2406.72 2499.92
  230.13  229.59  227.14  226.87  226.02   224.5  222.69     221  219.16  217.56
  215.34  214.18  213.53  212.64  211.57  211.12  209.34  207.82  206.05  203.52
  202.65  202.11  202.14  199.93   199.8  198.97  197.52   197.5  196.99  196.82
  195.64  195.25  194.93  194.66  194.89  194.83  195.71  196.12  196.65  197.13
   197.3  200.25  200.79  201.65  203.44  204.71  206.71  207.44  208.17  208.89
  210.85  212.33   215.4  216.19  217.51  218.18   219.1  219.89  221.65  225.12
                                                                                
                                                                                
                                                                                
                                                                                
                                                                                
                                                                                
       0    21.7   94.02  108.48  130.18  188.03  238.66  303.75  354.37  419.46
  484.55  527.94  542.41  578.57   607.5  688.51  731.75  803.82  875.88  911.92
  919.12  926.33   998.4 1048.84 1092.08  1106.5 1128.12 1149.74 1207.39 1277.37
 1291.84 1378.62 1400.31  1443.7 1552.17 1566.63 1612.04 1626.51 1648.21 1662.68
 1735.02 1742.26 1771.19 1778.43 1821.83 1915.88 1966.52 1992.62  2007.3 2036.66
 2095.39  2132.1 2227.54 2243.56 2332.56 2347.39 2406.72 2451.22 2466.05 2485.04
  230.13  229.59  227.14  226.87  226.02   224.5  222.69     221  219.16  217.56
  215.34  214.18  213.53  212.64  211.57  209.34  207.82  206.05  203.52  202.65
  202.11  202.14  199.93  198.97  197.52   197.5  196.99  196.82  195.64  195.25
  194.93  194.66  194.89  194.83  195.71  196.12  196.65  197.13   197.3  197.78
  199.29  199.64  200.25  200.79  201.65  204.71  206.71  207.44  208.17  208.89
  210.85  212.33   215.4  216.19   219.1  219.89  221.65  223.34   223.8  223.84
                                                                                
                                                                                
                                                                                
                                                                                
                                                                                
                                                                                
BR Coef=-1 , 0 , 0 ,, 0 ,,,0.8,-1,,0,
WSPro=,,,, 1 ,,,, 0 ,,,, 0 ,,,,-1 ,-1 ,-1 , 0 , 0 , 0 , 0 , 0
Culvert=9,36,45,275,0.017,0.7,1,60,1,128,1283,128,1300,Culvert #1  , 0 ,82.7
Culvert Bottom n=0.017
BC Design=,, 0 ,, 0 ,,,,,,
BC Use User HTab Curves=0
BC User HTab FreeFlow(D)= 0

Type RM Length L Ch R = 1 ,16952.19,363.33,411.99,388.85
BEGIN DESCRIPTION:
Center of channel lowered to culvert invert based on survey info. and photos.
END DESCRIPTION:
XS GIS Cut Line= 6
1586894.87519483707864.8054448811586248.16648431707696.894285753
 1585676.2284929707556.9094626611584990.22567827707378.471735969
1584736.93964124707298.4300279021584497.56685449707214.649552554
#Sta/Elev= 30
       0  214.15   180.8  205.51  303.75   196.8  506.25  185.96   564.1  177.99
  593.03  171.86  636.42  159.33  668.15  155.24  711.39  158.99  891.56   149.3
  985.24  146.28 1114.96  138.38 1201.44  136.33  1264.2  132.45 1278.67     128
 1322.06     128  1332.5  132.43 1358.21  137.69 1408.83  154.77 1430.53  159.65
 1481.15  164.76 1524.54  164.01 1560.69  169.23 1713.25  183.71 1857.93   191.3
 1944.75   201.7 2009.85  201.88 2112.63  206.99 2208.06  209.61 2485.04  223.84
#Mann= 3 , 0 , 0
       0      .1       0  1264.2     .04       0  1332.5      .1       0
Bank Sta=1264.2,1332.5
XS Rating Curve= 0 ,0
Exp/Cntr=0.5,0.3

Type RM Length L Ch R = 1 ,16540.20,638.63,668.93,548.6
XS GIS Cut Line= 2
 1586957.6345949707547.8749860081584550.01571108706861.280153543
#Sta/Elev= 30
       0  200.25   50.95  198.44   87.35  193.77  109.19   196.5  356.67  188.79
  458.58  177.83  553.21  153.33  604.16  147.83  684.23  147.78  742.47  142.55
  793.42  143.03  917.16  134.45     939  135.96 1157.37  130.58 1244.72  130.13
 1266.56  127.88 1371.22  128.19 1404.86  124.97 1432.31  128.42 1477.65  132.52
 1521.32  139.62 1594.11  141.39 1615.95  144.11 1637.79  152.37 1652.35  155.76
 1783.37  168.06 1994.46  179.56 2074.53  179.78 2183.72  190.12  2503.6  208.13
#Mann= 3 , 0 , 0
       0      .1       0 1371.22     .04       0 1432.31      .1       0
#XS Ineff= 2 , 0
         1077.35  133.61
Permanent Ineff=
       F       F
Bank Sta=1371.22,1432.31
XS Rating Curve= 0 ,0
Exp/Cntr=0.3,0.1

Type RM Length L Ch R = 1 ,15871.27,423.95,460.45,475.23
XS GIS Cut Line= 5
1587407.39183354706839.6444115941586712.06754483706699.625014842
1586052.85897928706706.9236132061585678.11790146706753.766247913
1584624.15862009706433.674910605
#Sta/Elev= 30
       0  233.47  149.95  222.84  207.08  221.49  364.17  210.71   599.8   204.2
  723.28  198.06  863.29  196.19  919.29   194.2 1192.31  176.39 1297.32  166.25
  1389.7  152.32 1439.08   141.1 1474.35  126.08 1490.76   121.7 1509.62  118.99
 1537.84  119.16 1553.33   121.7 1573.11  125.19 1622.49  126.09 1657.77  128.76
  1714.2  137.35 1790.08  151.25 1885.19  163.67 1987.61   172.8 2163.18  176.23
 2214.39  174.86 2287.55  175.75 2368.02  179.75 2521.65  181.16 2847.68  196.02
#Mann= 3 , 0 , 0
       0      .1       0 1490.76     .04       0 1553.33      .1       0
Bank Sta=1490.76,1553.33
XS Rating Curve= 0 ,0
Exp/Cntr=0.3,0.1

Type RM Length L Ch R = 1 ,15410.82,846.28,898.99,777.56
XS GIS Cut Line= 6
1587399.58472778706816.2230942251586326.10768189706472.710439563
1586111.41227275706343.8931940351585662.50368993706199.461736962
1585299.47327079706160.4262080341584811.52915899705992.573433578
#Sta/Elev= 30
       0  232.38  161.69  220.28  249.89  217.26  323.39  210.78  543.88  204.68
  999.56  186.17  1127.1  174.03 1159.75  168.61 1233.22  151.06 1331.18  140.98
 1355.67  135.12 1392.12  121.94 1479.97  121.45 1519.31  119.07 1538.54  114.44
 1560.51  115.29 1579.14  118.99 1711.92  126.96  1734.1  130.71 1793.24   147.6
 1856.25  178.98 1877.72  181.59 1934.97   181.4 2085.84   186.5 2171.69  182.74
 2230.87  173.03 2438.14   177.4 2541.78  183.27 2623.21  183.11 2732.07  186.98
#Mann= 3 , 0 , 0
       0      .1       0 1519.31     .04       0 1579.14      .1       0
Bank Sta=1519.31,1579.14
XS Rating Curve= 0 ,0
Exp/Cntr=0.3,0.1

Type RM Length L Ch R = 1 ,14511.83,560.92,592.81,392.6
XS GIS Cut Line= 4
  1587419.952237706073.7269678121586772.05777299705769.776478499
1586264.14050795705581.8070969581585279.95550628705340.680100262
#Sta/Elev= 30
       0  233.52  108.25  223.86   216.5  209.74  247.43  207.46  394.33  197.99
  634.03  188.73  688.15  183.24  812.68  162.69  857.47  152.75  872.39  147.14
  887.32  139.43  894.78  135.12  917.18  115.75  930.99  110.28  947.03  107.74
  969.42   107.5 1002.21  110.29 1021.67  114.07 1044.06  114.36 1088.85  111.66
 1133.63  115.35 1350.92   113.4 1408.58  111.57 1487.86   123.1 1538.31  134.87
 1567.14  139.56    1632  144.56 1711.28  156.05 1905.87   168.9 2270.53  198.22
#Mann= 3 , 0 , 0
       0      .1       0  930.99     .04       0 1002.21      .1       0
Bank Sta=930.99,1002.21
XS Rating Curve= 0 ,0
Exp/Cntr=0.3,0.1

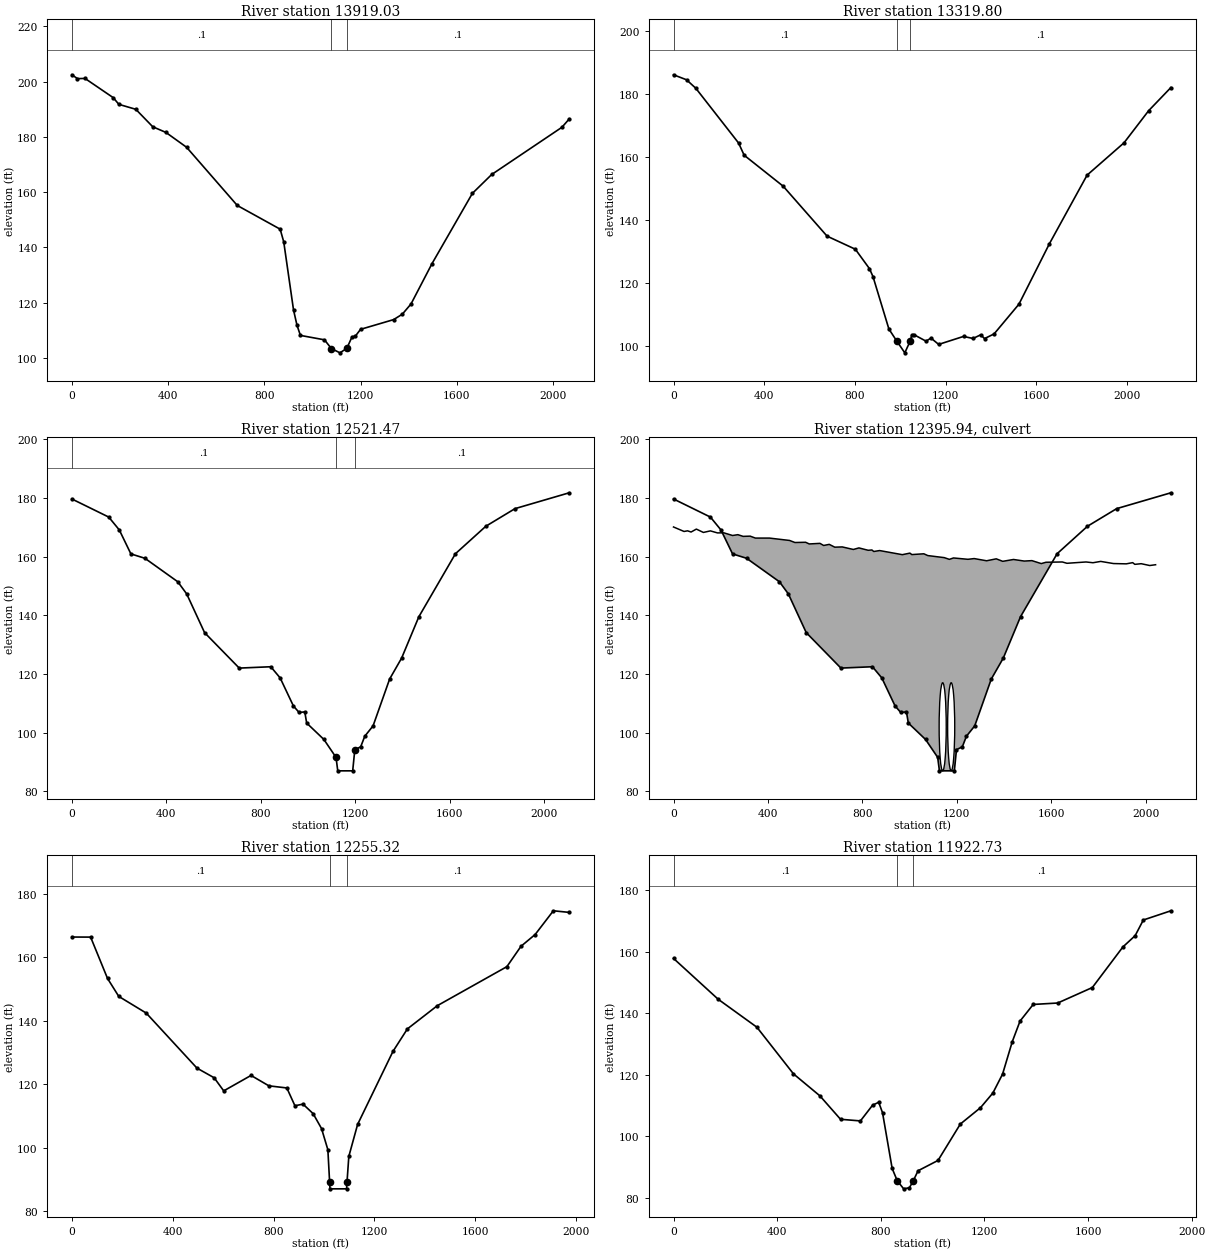
Type RM Length L Ch R = 1 ,13919.03,541.55,599.22,584.54
XS GIS Cut Line= 6
1587282.47814095705586.6039325891586739.88428867705317.258782908
1586462.73203322705219.6699605581586197.29043639705165.020220041
1585924.04173379 705094.756267951585334.60524683704922.999940604
#Sta/Elev= 30
       0  202.49   23.45   201.1   54.71  201.16  171.93   194.2  195.38  191.78
  265.71  189.99  336.05  183.67  390.75  181.62  476.72  176.24   687.4  155.16
  865.51  146.58  880.35  141.99  921.04  117.32  935.33  111.83  949.63  108.11
 1049.68  106.51 1078.27  103.35    1114   101.8 1142.59  103.46 1164.03  107.58
 1177.84  107.84 1199.52  110.31 1336.85  113.83 1372.99  115.79 1409.12  119.49
  1496.5  134.12 1664.19  159.55 1744.39  166.38 2036.04  183.47  2066.7  186.51
#Mann= 3 , 0 , 0
       0      .1       0 1078.27     .04       0 1142.59      .1       0
Bank Sta=1078.27,1142.59
XS Rating Curve= 0 ,0
Exp/Cntr=0.3,0.1

Type RM Length L Ch R = 1 ,13319.80,736.81,798.33,711.33
XS GIS Cut Line= 5
1587477.94279087705215.8667052391587006.01966275704927.913610116
1586482.10500358704671.9553033411586008.18220119704354.007094145
1585631.27526674704044.700539425
#Sta/Elev= 30
       0  186.17    57.4  184.58    98.4  181.88  287.01  164.47  311.61  160.58
  483.81  150.72  677.49  134.83  802.14  130.67  864.47  124.48  880.05  121.95
  950.16  105.28  984.32  101.52 1020.28   97.71 1043.65  101.39 1051.44  103.42
 1059.23  103.54 1113.77  101.43 1135.93   102.4 1169.65  100.39 1279.23  102.93
 1321.38  102.28  1355.1  103.45 1371.95  102.24  1414.1  103.73 1523.68  113.18
 1658.55  132.47 1824.34  154.24 1987.34  164.53    2096  174.75  2194.2  182.12
#Mann= 3 , 0 , 0
       0      .1       0  984.32     .04       0 1043.65      .1       0
Bank Sta=984.32,1043.65
XS Rating Curve= 0 ,0
Exp/Cntr=0.5,0.3

Type RM Length L Ch R = 1 ,12521.47,261.47,266.15,268.67
BEGIN DESCRIPTION:
Center of channel lowered to culvert invert based on survey info. and photos.
END DESCRIPTION:
XS GIS Cut Line= 6
 1587695.0474274704547.5154874921587097.88182919704322.845551357
1586740.96445616704133.5404543881586326.70073022703815.069383264
1586112.35594164703601.3744078581585961.70734903703416.117354885
#Sta/Elev= 30
       0  179.61  156.31  173.44  200.97  169.06  250.07   160.9  309.56   159.4
   448.6  151.41  486.44  147.26  562.12  134.08  708.92     122  842.56  122.46
  882.17  118.65  938.34   109.1  962.42  106.88  986.49  107.08  994.52  103.28
 1067.42   97.69 1118.84   91.58 1126.15      87 1189.41      87 1198.36    94.2
 1223.18   95.18  1240.7    98.8 1275.75  102.32 1345.85  118.27 1396.67  125.41
 1469.68   139.5 1624.59  160.96 1753.28  170.32 1876.89  176.32 2106.64  181.72
#Mann= 3 , 0 , 0
       0      .1       0 1118.84     .04       0 1198.36      .1       0
Bank Sta=1118.84,1198.36
XS Rating Curve= 0 ,0
Exp/Cntr=0.5,0.3

Type RM Length L Ch R = 2 ,12395.94,,,
BEGIN DESCRIPTION:
Chessie System RR, MDE Bridge #: CE033007FS-4
Top of road obtained from DEM.
Opening from MDE2 bridge/culvert surveys.
END DESCRIPTION:
Bridge Culvert--1,0,-1,-1, 0
Deck Dist Width WeirC Skew NumUp NumDn MinLoCord MaxHiCord MaxSubmerge Is_Ogee
112.1,42,2.6,0, 60, 60, , , 0.98, 0, 2,2,,
       0   44.66   59.55   74.43   96.76  126.54  156.31  186.09  213.03  250.21
  272.52  294.83  324.58  346.89  406.39  491.57  514.28  559.68  574.82  620.23
  635.91  659.49  683.08  714.52  761.69  785.27  824.58   840.3  848.16  872.82
  969.11 1001.21 1009.24 1060.14 1076.92  1146.7  1168.2 1185.72 1247.06 1273.35
 1325.92 1366.89 1394.26  1439.9 1485.53 1517.88 1557.47 1577.27 1646.57 1666.37
  1746.9 1776.46 1809.33 1863.47  1917.6 1944.67 1953.69 1980.76 2016.85 2041.66
  170.07  168.54  168.76  168.35  169.35  168.21  168.74  168.05  168.08  167.17
  167.45  166.87  166.95  166.29  166.29  165.48  164.78  164.86  164.29  164.49
  163.77  164.15  163.19  163.28  162.41  162.94  162.13  162.24  161.72  162.04
  160.64  161.17  160.67  160.94  160.33  159.63  159.04  159.52  159.06  159.31
  158.56  159.22  158.37     159  158.46  158.61   157.6  158.05  158.15   157.7
  158.15  157.89  158.34  157.61  157.51  157.92  157.34  157.56  156.94  157.21
                                                                                
                                                                                
                                                                                
                                                                                
                                                                                
                                                                                
       0   44.66   59.55   74.43   96.76  126.54  156.31  186.09  213.03  250.21
  272.52  294.83  324.58  346.89  406.39  491.57  514.28  559.68  574.82  620.23
  635.91  659.49  683.08  714.52  761.69  777.41  785.27  824.58   840.3  848.16
  872.82  969.11 1001.21 1009.24 1060.14 1076.92  1146.7  1168.2 1185.72 1247.06
 1273.35 1325.92 1366.89 1394.26  1439.9 1485.53 1517.88 1557.47 1577.27 1636.67
 1646.57 1666.37  1746.9 1776.46 1809.33 1863.47  1917.6 1944.67 1953.69 1971.73
  170.07  168.54  168.76  168.35  169.35  168.21  168.74  168.05  168.08  167.17
  167.45  166.87  166.95  166.29  166.29  165.48  164.78  164.86  164.29  164.49
  163.77  164.15  163.19  163.28  162.41  162.48  162.94  162.13  162.24  161.72
  162.04  160.64  161.17  160.67  160.94  160.33  159.63  159.04  159.52  159.06
  159.31  158.56  159.22  158.37     159  158.46  158.61   157.6  158.05  157.85
  158.15   157.7  158.15  157.89  158.34  157.61  157.51  157.92  157.34  157.42
                                                                                
                                                                                
                                                                                
                                                                                
                                                                                
                                                                                
BR Coef=-1 , 0 , 0 ,, 0 ,,,0.8,-1,,0,
WSPro=,,,, 1 ,,,, 0 ,,,, 0 ,,,,-1 ,-1 ,-1 , 0 , 0 , 0 , 0 , 0
Multiple Barrel Culv=9,30,30,170,0.017,0.7,1,60,1,87,87, 2,Culvert #1  , 0 ,48.1
    1140    1039    1176    1075
Culvert Bottom n=0.017
BC Design=,, 0 ,, 0 ,,,,,,
BC Use User HTab Curves=0
BC User HTab FreeFlow(D)= 0

Type RM Length L Ch R = 1 ,12255.32,364.83,332.58,299.63
BEGIN DESCRIPTION:
Center of channel lowered to culvert invert based on survey info. and photos.
END DESCRIPTION:
XS GIS Cut Line= 6
1587783.44419771704303.0037066041587206.64244996704086.442468628
1586876.36532438703911.3764358311586502.38292648703623.056053296
1586305.26463893703426.4991308151586103.22945213703313.301014245
#Sta/Elev= 30
       0   166.4   74.43  166.38  141.42  153.35  186.09  147.68     295  142.42
   496.3  125.06  564.41  122.02  602.25  117.89  710.58  122.76  781.33  119.48
  852.55  118.81  884.65   113.2  916.75  113.71  956.87  110.71  990.12  106.02
 1015.29   99.34 1022.31   89.01 1023.68      87 1089.29      87 1091.13   89.01
 1098.37   97.22 1133.27  107.32 1273.46  130.34 1330.62  137.43 1449.26  144.75
 1725.22  157.06 1781.16  163.48 1837.33   167.2 1909.55  174.68 1972.63  174.17
#Mann= 3 , 0 , 0
       0      .1       0 1022.31     .04       0 1091.13      .1       0
Bank Sta=1022.31,1091.13
XS Rating Curve= 0 ,0
Exp/Cntr=0.5,0.3

Type RM Length L Ch R = 1 ,11922.73,277.28,249.05,211.18
XS GIS Cut Line= 6
1587819.23446877 704074.161097691587304.74586312703813.486870855
1587153.82920547703672.8599852921587016.63224399703624.841048777
  1586745.668245703597.4016564641586100.84252594703285.278569028
#Sta/Elev= 30
       0  157.88  172.64  144.58  321.74  135.51  462.99  120.33     565  113.18
  644.61  105.56  721.41  105.03  768.33  110.15  791.89  111.09  806.72  107.69
   843.8   89.59  863.52   85.57   888.3   82.94  910.55   83.31  925.38   85.57
  943.83   88.82 1020.87   92.18 1106.95  104.01 1184.77  109.33 1232.55   114.1
 1270.01  120.26 1307.46  130.81 1337.42   137.5 1388.22  142.91 1482.66  143.37
 1616.44  148.41 1734.49  161.62  1781.7  165.28 1813.18  170.37 1919.73  173.37
#Mann= 3 , 0 , 0
       0      .1       0  863.52     .04       0  925.38      .1       0
Bank Sta=863.52,925.38
XS Rating Curve= 0 ,0
Exp/Cntr=0.3,0.1

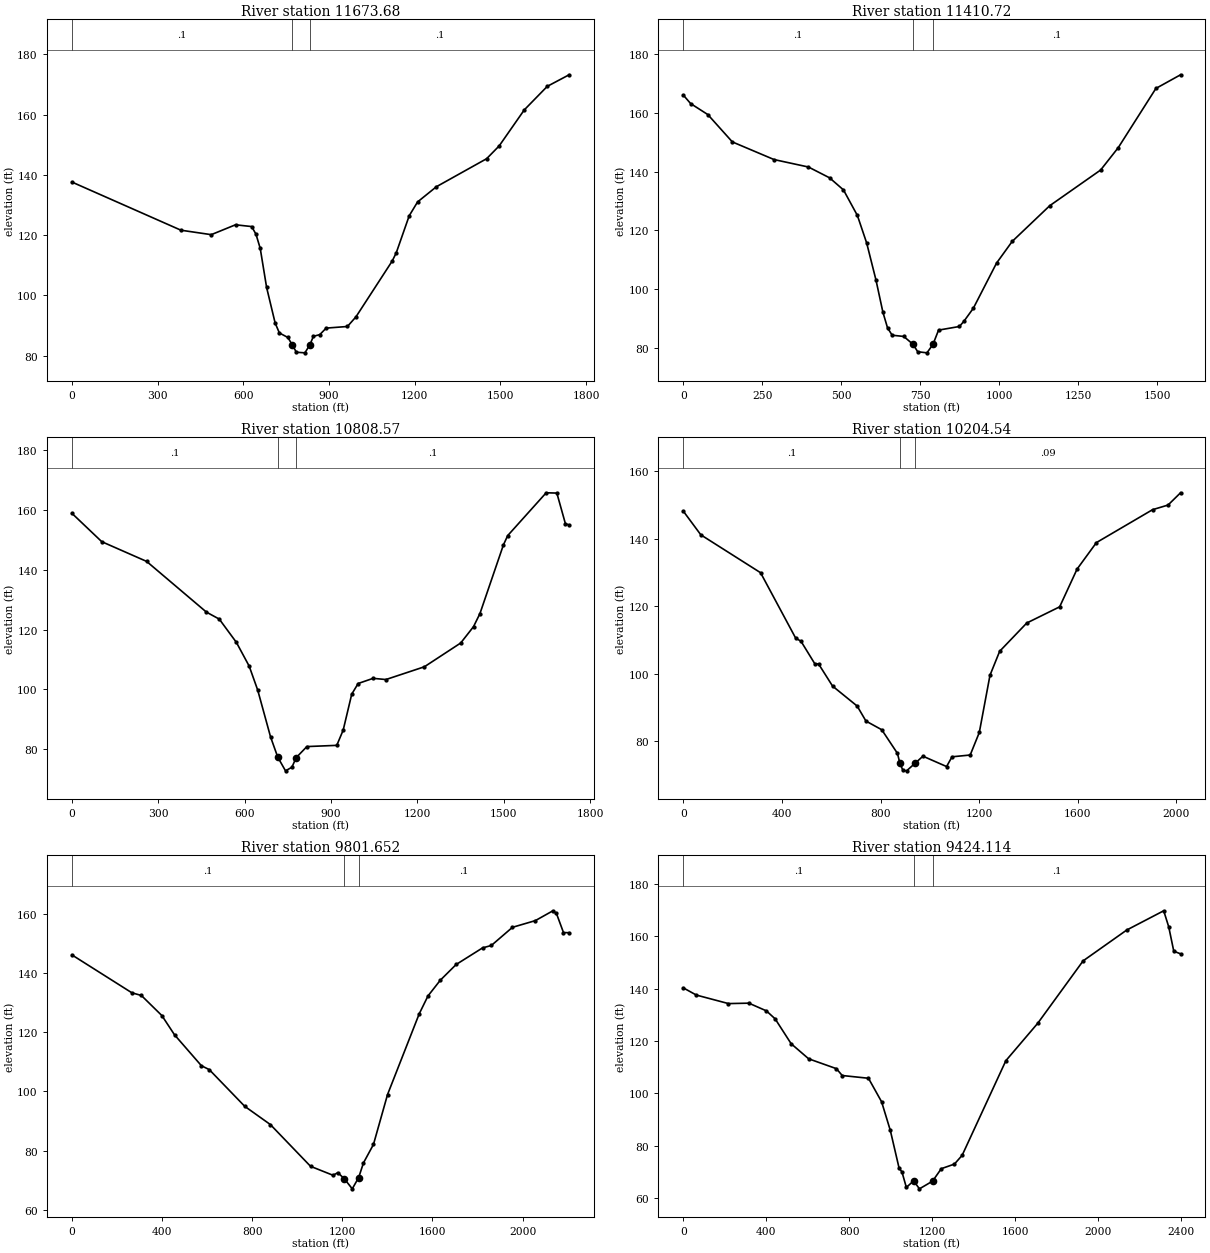
Type RM Length L Ch R = 1 ,11673.68,258.46,262.96,266.02
XS GIS Cut Line= 5
1587778.07538034703250.9793286621587140.10950935703343.587277681
1586817.69664979703460.204694971 1586625.6209037703436.195226684
1586090.55275382703271.558872879
#Sta/Elev= 30
       0  137.63  381.96  121.63  488.06  120.15  572.94  123.43  629.53  122.84
  644.65   120.3  659.54  115.58  681.87  102.61  711.65   90.83  726.53   87.51
  756.31   86.01  771.57   83.57  786.09   81.11  815.86   80.91  833.27   83.57
  845.64   86.39  867.97   86.96   890.3   89.12  964.74   89.66  994.56   92.85
 1121.54   111.4 1135.65  114.11 1181.08  126.43 1210.37  131.02 1276.29  136.07
 1452.06  145.37    1496  149.62 1583.89  161.58 1664.45   169.4  1740.9  173.24
#Mann= 3 , 0 , 0
       0      .1       0  771.57     .04       0  833.27      .1       0
Bank Sta=771.57,833.27
XS Rating Curve= 0 ,0
Exp/Cntr=0.3,0.1

Type RM Length L Ch R = 1 ,11410.72,603.46,602.15,600.89
XS GIS Cut Line= 4
1587575.70986213702877.117608562 1587191.5583699703062.333506584
1586618.76105563 703244.119480581586071.69329067703254.184732944
#Sta/Elev= 30
       0  166.17   23.31  163.26   77.71  159.51  155.42  150.18  287.53  144.16
  396.33  141.62  463.19  137.94  507.26  133.81  551.32  125.09   580.7  115.71
  610.07  103.13   632.1   92.11  646.79   86.75  661.48   84.25   698.2   83.83
  727.58   81.14  742.27   78.62  771.64   78.24  790.71   81.14  808.36   85.99
  874.46   87.23  889.15   89.08  918.52   93.46  991.96  108.85 1041.42  116.23
 1160.44  128.43 1321.47  140.59 1377.48  148.25  1496.5  168.42 1574.58  173.08
#Mann= 3 , 0 , 0
       0      .1       0  727.58     .04       0  790.71      .1       0
Bank Sta=727.58,790.71
XS Rating Curve= 0 ,0
Exp/Cntr=0.3,0.1

Type RM Length L Ch R = 1 ,10808.57,603.2,604.03,613.97
XS GIS Cut Line= 2
1587380.20419198702348.9093067651585750.99027407702921.706621051
#Sta/Elev= 30
       0  158.98  103.88  149.46   259.7  142.86  467.46  125.88  511.98  123.55
  571.34  115.77  615.86  107.81  645.54   99.77  690.06   84.13  715.14   77.33
     742   72.76  764.26   73.97   779.1   77.18   816.2   80.88  920.08   81.29
  942.34    86.4  972.02   98.43  994.28  101.99 1046.22  103.72 1090.74  103.32
 1224.31  107.59 1350.45  115.55 1394.97  121.02 1417.23  125.39 1498.85   148.4
 1513.69   151.5 1647.25  165.83 1684.35  165.73 1714.03  155.49 1726.98  155.05
#Mann= 3 , 0 , 0
       0      .1       0  715.14     .04       0   779.1      .1       0
Bank Sta=715.14,779.1
XS Rating Curve= 0 ,0
Exp/Cntr=0.3,0.1

Type RM Length L Ch R = 1 ,10204.54,332.35,402.9,343.39
XS GIS Cut Line= 4
1587342.47502756701855.0002453331586546.73265085702005.916902989
1586142.00161436702139.6839404551585445.72703476702492.966116354
#Sta/Elev= 30
       0  148.12   71.25   141.1  313.49   129.9  455.99  110.54  477.36  109.64
  534.36  102.87  548.61  102.94  605.61   96.36  705.35   90.46  740.98   86.02
   805.1   83.45  868.91   76.44  878.48   73.56  891.02   71.43  905.77    71.3
  940.51   73.56  972.12   75.63 1067.96   72.57 1090.08   75.45  1163.8   75.98
 1200.67   82.64 1244.04   99.57 1283.29  106.66 1393.18  115.02 1526.62  119.81
 1597.27  130.97 1675.76  138.81  1903.4  148.54 1966.19  149.91 2016.96  153.54
#Mann= 3 , 0 , 0
       0      .1       0  878.48     .04       0  940.51     .09       0
Bank Sta=878.48,940.51
XS Rating Curve= 0 ,0
Exp/Cntr=0.3,0.1

Type RM Length L Ch R = 1 ,9801.652,331.71,377.54,364.08
XS GIS Cut Line= 4
1587360.93938755701710.5335462991586687.35953638701745.242676154
1586042.53381732701865.2900174561585257.08121267 702252.87143372
#Sta/Elev= 30
       0  146.16  266.35  133.33  308.41  132.43  399.53  125.62   455.6  119.12
  574.76  108.68  609.81  107.35  767.04   94.95  880.96   88.77 1058.97   74.67
 1158.65   71.64 1180.01   72.52 1208.49   70.49  1244.1   67.05 1272.58   70.88
 1293.94   75.84 1338.18   82.06 1400.63   98.93 1541.13  126.22 1580.16  132.28
  1634.8  137.59 1705.06   142.9 1822.14  148.51 1861.17  149.33 1954.84  155.47
 2056.32  157.73 2134.38  161.06 2149.99  160.15 2181.21   153.7 2206.25  153.64
#Mann= 3 , 0 , 0
       0      .1       0 1208.49     .04       0 1272.58      .1       0
Bank Sta=1208.49,1272.58
XS Rating Curve= 0 ,0
Exp/Cntr=0.3,0.1

Type RM Length L Ch R = 1 ,9424.114,256.36,254.58,231.4
XS GIS Cut Line= 5
1587360.97470535701586.2759523241586367.03199039701490.638852581
1586110.86118758701511.1325168161585950.32748447701569.197898805
1585110.08725117702057.630229518
#Sta/Elev= 30
       0  140.26   63.29   137.5     218  134.25  316.45  134.41  400.84  131.47
  443.04  128.42  520.39   118.9  604.78  113.15  738.39  109.39  766.52  106.77
  893.11  105.72   956.4   96.74  998.53   85.78 1040.67   71.43 1054.71   69.91
 1075.78   64.02 1110.89   66.52 1138.98   63.47 1202.18   66.41 1244.32   71.17
 1307.63   72.93 1344.85   76.27 1555.78  112.44 1709.62  126.75 1928.24  150.57
 2138.75  162.36 2316.88  169.71 2341.17  163.55 2365.46  154.26 2398.12  153.26
#Mann= 3 , 0 , 0
       0      .1       0 1110.89     .04       0 1202.18      .1       0
Bank Sta=1110.89,1202.18
XS Rating Curve= 0 ,0
Exp/Cntr=0.3,0.1