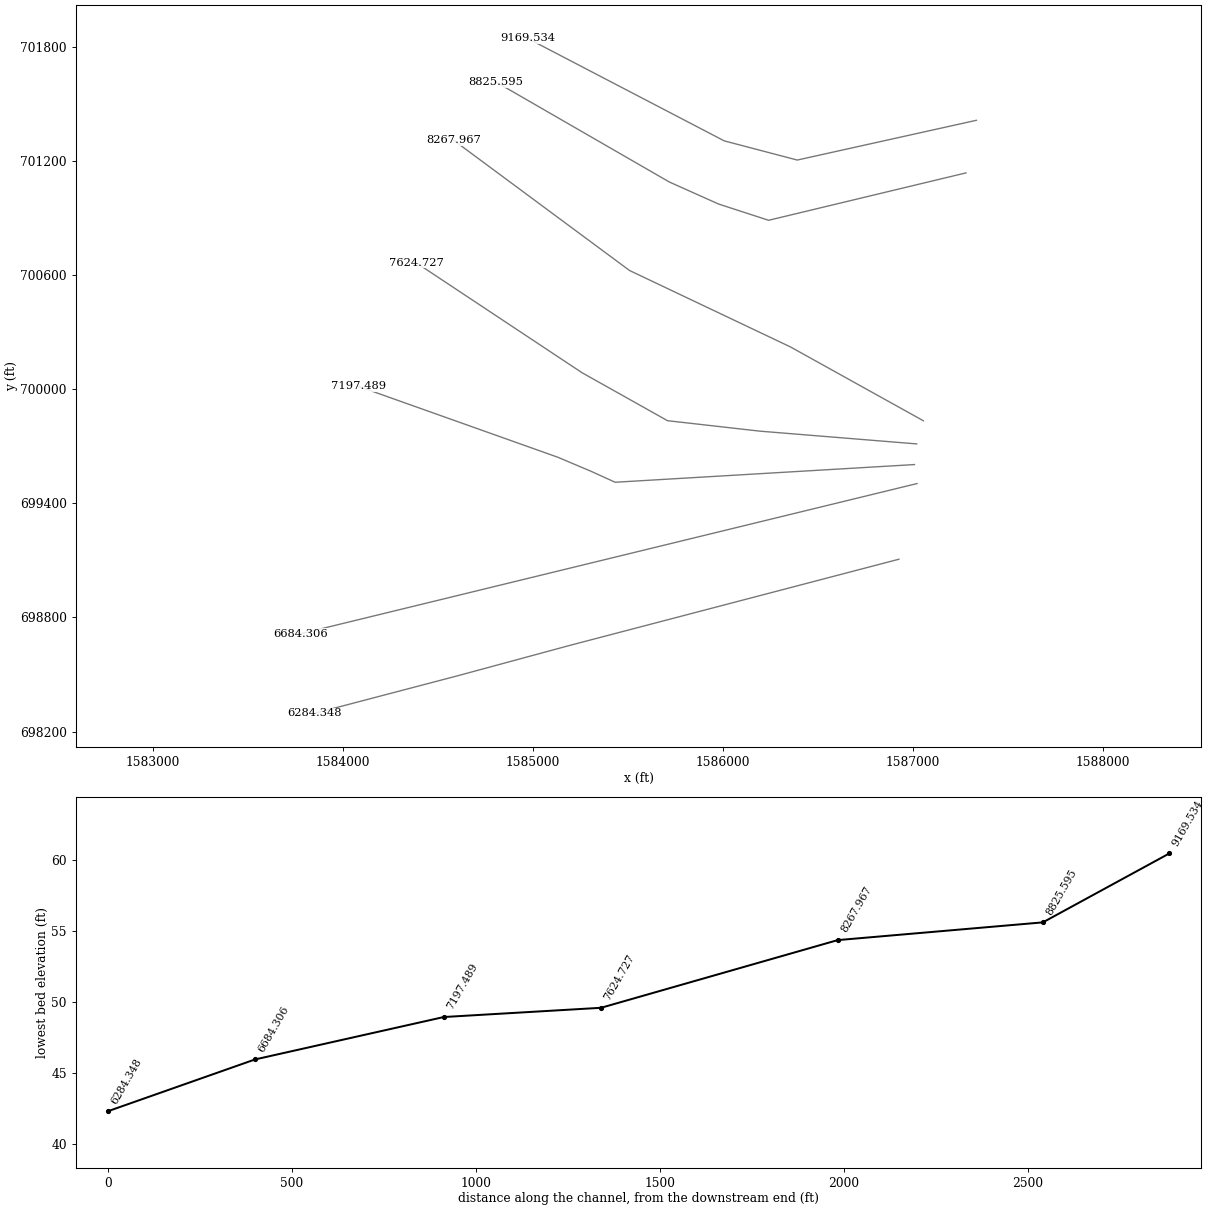
HEC-RAS study PrincipioCreek.prj: PrincipioCreek

--- PrincipioCreek.g01 (geometry) --- (continued)

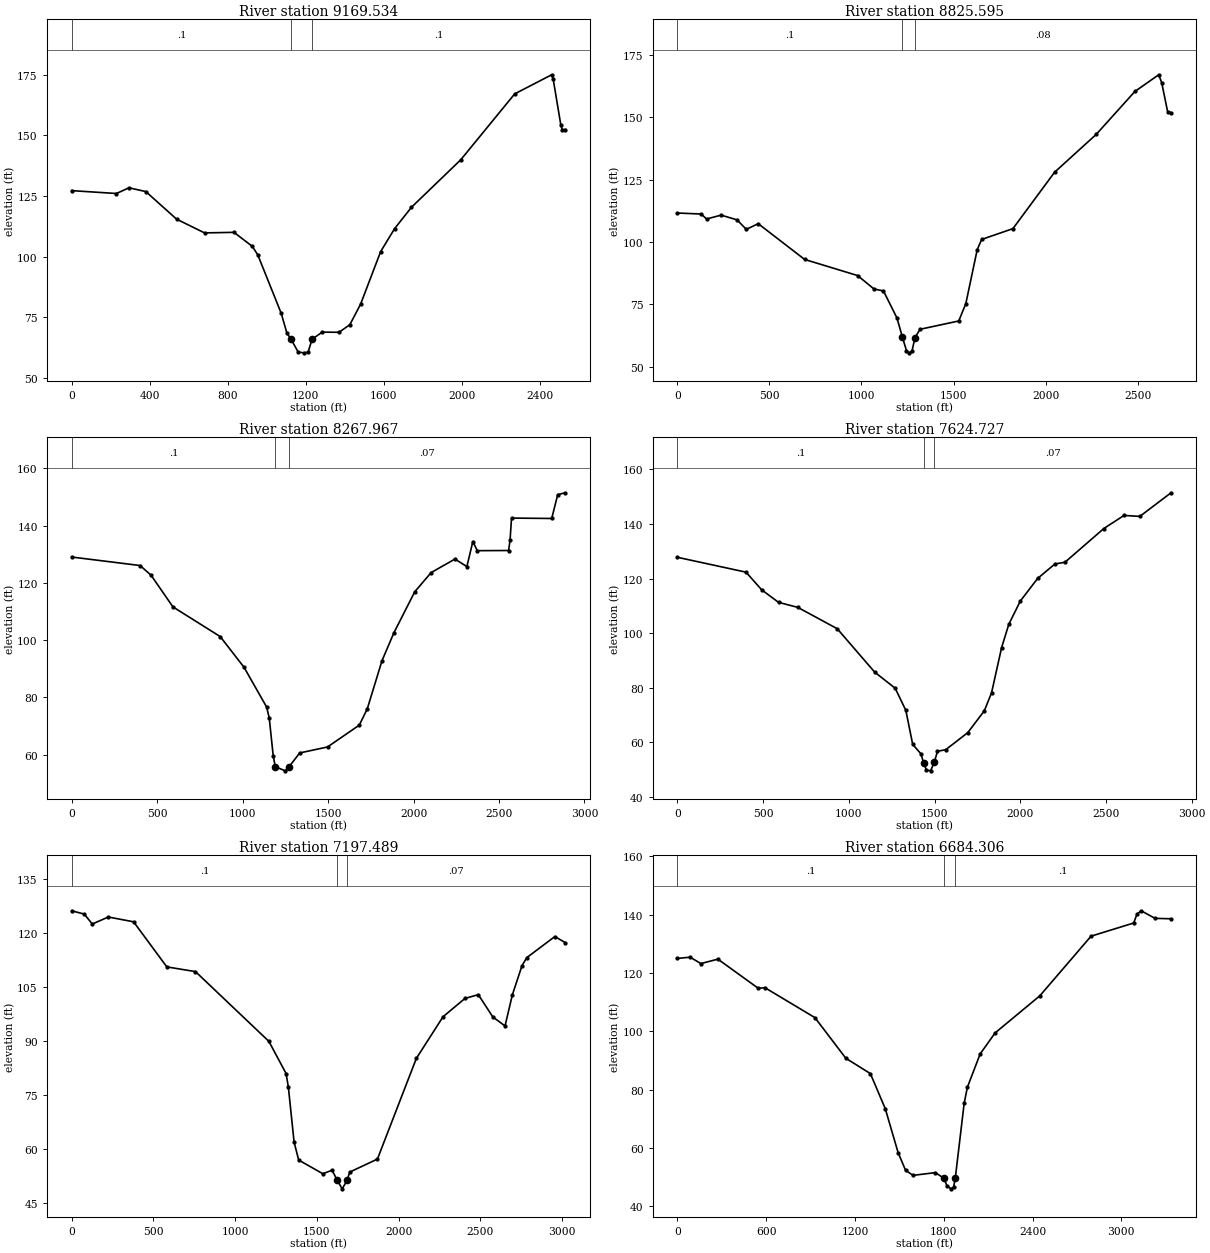
Type RM Length L Ch R = 1 ,9169.534,341.3,343.94,337.43
XS GIS Cut Line= 4
 1587333.6498197701415.4954170881586391.31880979701206.330845878
1586007.34906104701307.1713859741584972.37105751 701846.62683709
#Sta/Elev= 30
       0  127.22  229.45  126.04  293.99  128.39  380.03  126.83  537.78  115.47
  681.18  109.82  831.76  110.05  924.98  104.33  953.66  100.79 1073.83   76.71
 1102.78   68.61 1124.49   66.03 1160.67   60.77 1189.62   60.45 1211.34   60.68
 1231.81   66.03 1283.71   68.98 1370.15   68.91 1425.41   72.03 1480.66   80.51
 1583.28  102.12 1654.33  111.52 1741.16  120.37 1993.76  139.92 2270.04  167.04
  2459.5  174.91 2467.39  173.14 2506.86  154.11 2514.75  152.23 2529.39  152.38
#Mann= 3 , 0 , 0
       0      .1       0 1124.49     .04       0 1231.81      .1       0
Bank Sta=1124.49,1231.81
XS Rating Curve= 0 ,0
Exp/Cntr=0.3,0.1

Type RM Length L Ch R = 1 ,8825.595,557.29,557.63,527.18
XS GIS Cut Line= 5
1587279.00004847701138.8309500371586240.65439431700889.491368622
1585977.65237011700974.8816362321585718.06595658 701091.01240018
 1584806.0978985701617.016448662
#Sta/Elev= 30
       0  111.64  129.58  111.23  158.38  109.24  237.57  110.79  323.95  108.89
  374.35  105.09  439.14  107.36   691.1   93.03  979.06   86.57 1067.86   81.19
 1119.38    80.4 1192.98   69.53 1222.42   61.84  1244.5   56.46 1259.22   55.59
 1273.94   56.15 1290.63   61.67 1318.09   65.03 1528.43   68.36 1566.77    75.3
 1628.76   96.96    1653  101.05  1822.7  105.38 2048.97  127.98 2275.23  143.16
 2485.33  160.37 2614.63  167.05 2630.79  163.91 2663.11  152.26 2681.54  151.87
#Mann= 3 , 0 , 0
       0      .1       0 1222.42     .04       0 1290.63     .08       0
Bank Sta=1222.42,1290.63
XS Rating Curve= 0 ,0
Exp/Cntr=0.3,0.1

Type RM Length L Ch R = 1 ,8267.967,639.16,643.24,618.03
XS GIS Cut Line= 4
1587054.72329462699834.862811431 1586355.9000015700223.097974271
1585508.84146433700625.4507794231584584.13589467701310.156430259
#Sta/Elev= 30
       0  129.05  400.39  126.08  464.45   122.7  592.57  111.62  869.17  101.25
 1008.66    90.5  1140.4   76.65  1155.9   72.82 1179.15   59.56 1191.24   55.82
  1248.9   54.34 1272.37   55.81 1334.14   60.59 1496.88   62.68 1682.87   70.32
 1729.37      76 1815.57   92.83 1885.25  102.58 2007.19  116.91 2103.01  123.61
 2242.37  128.34 2312.05  125.71 2346.89  134.45 2373.02  131.27 2555.94  131.33
 2564.65  134.83 2573.36  142.66 2808.53  142.52 2843.37  150.84  2887.8   151.5
#Mann= 3 , 0 , 0
       0      .1       0 1191.24     .04       0 1272.37     .07       0
Bank Sta=1191.24,1272.37
XS Rating Curve= 0 ,0
Exp/Cntr=0.3,0.1

Type RM Length L Ch R = 1 ,7624.727,391.09,427.24,434.94
XS GIS Cut Line= 5
1587019.63294415699713.1151561741586195.68527378699780.113057703
 1585708.9019326699835.2206057611585258.85695682700087.796867669
1584386.32077934700666.426122233
#Sta/Elev= 30
       0  127.82  400.32  122.37  491.62   115.9  589.94  111.31  702.31  109.47
  932.34  101.65 1150.73   85.75 1270.48   79.84 1332.61   71.73 1372.75   59.24
 1420.91   55.79 1436.35   52.48 1453.02   49.87  1477.1   49.57 1497.97   52.64
 1517.24   56.72  1565.4   57.32 1693.83   63.56 1790.16   71.54 1832.64   78.15
 1891.44   94.76 1933.43  103.29 2000.63   111.8 2101.42  120.07 2202.21  125.37
 2261.01  126.01 2487.79  138.37 2605.39  143.16 2697.78  142.81 2879.61  151.46
#Mann= 3 , 0 , 0
       0      .1       0 1436.35     .04       0 1497.97     .07       0
Bank Sta=1436.35,1497.97
XS Rating Curve= 0 ,0
Exp/Cntr=0.3,0.1

Type RM Length L Ch R = 1 ,7197.489,416.62,513.18,544.8
XS GIS Cut Line= 5
1587007.99749723699604.5176514831585433.33367898699511.434076026
1585305.34376273699569.6113107061585130.81205876699643.302474588
 1584083.6218348700015.636776447
#Sta/Elev= 30
       0  126.08   77.13  125.16  126.22  122.41  224.39  124.35  378.66  123.02
  582.01  110.51  757.32   109.2  1206.1   89.85 1311.28   80.92 1325.31   77.15
 1360.37   61.87 1388.42   56.91 1535.67   53.12 1592.79   54.08 1624.14    51.3
  1654.3   48.92 1684.52   51.24 1700.44   53.57 1869.97   57.18 2108.04   85.12
 2271.49   96.69 2405.21  101.75 2486.93  102.81 2576.08    96.6 2650.38   94.12
 2694.95  102.72 2754.38  110.88  2784.1   113.1 2954.97  118.93 3018.85  117.24
#Mann= 3 , 0 , 0
       0      .1       0 1624.14     .04       0 1684.52     .07       0
Bank Sta=1624.14,1684.52
XS Rating Curve= 0 ,0
Exp/Cntr=0.3,0.1

Type RM Length L Ch R = 1 ,6684.306,391.67,399.96,400.57
XS GIS Cut Line= 2
1587021.18883775699504.5364411771583780.13775072698714.700461999
#Sta/Elev= 30
       0  124.97   86.46  125.37  158.51  123.19  273.78  124.71  547.57  114.67
   590.8  114.94  929.43  104.65 1138.37   90.71 1304.08   85.46 1404.94    73.4
  1491.4   58.38 1541.84    52.3 1592.27   50.55 1743.57   51.49 1801.21   49.55
 1822.83   46.81 1851.64   45.93 1866.05   46.48 1877.89   49.56  1938.1   75.32
 1959.72   80.78 2046.18   92.21 2147.04   99.41 2449.65  112.15 2795.48  132.59
 3083.67  137.11 3105.29   140.1  3134.1   141.3 3227.77   138.7 3335.89  138.56
#Mann= 3 , 0 , 0
       0      .1       0 1801.21     .04       0 1877.89      .1       0
Bank Sta=1801.21,1877.89
XS Rating Curve= 0 ,0
Exp/Cntr=0.5,0.3

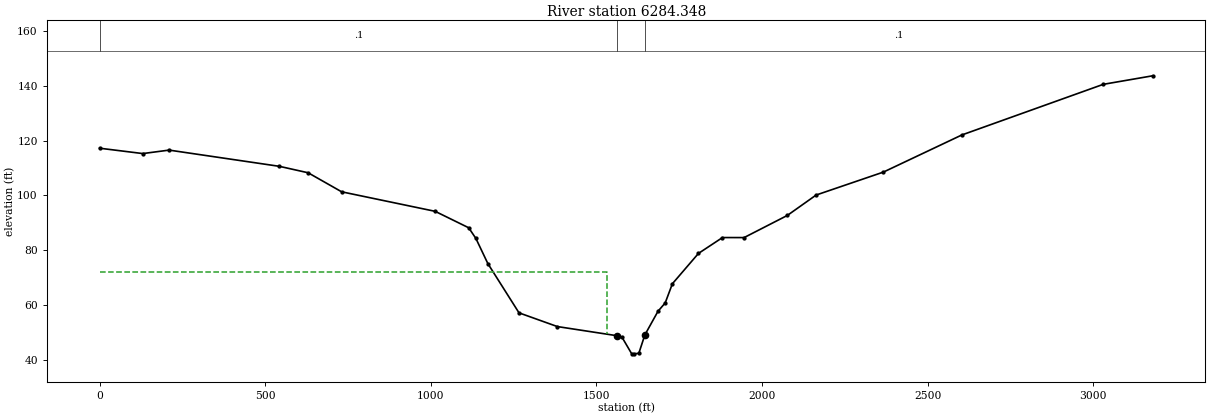
Type RM Length L Ch R = 1 ,6284.348,263.41,263.21,263.59
BEGIN DESCRIPTION:
Center of channel lowered 1.0 ft based on bridge survey info.
END DESCRIPTION:
XS GIS Cut Line= 4
1586926.01865672699106.5586286191585197.89513741698654.069462016
1584604.84427823698493.4192858341583851.27065966698295.623622522
#Sta/Elev= 30
       0  117.22  130.25  115.27  209.84  116.53   542.7  110.62  629.53  108.27
  730.83  101.33 1013.04   94.22 1114.34   88.23 1136.05   84.35 1172.23   75.17
  1266.3   57.22 1382.07   52.22 1562.97   48.87 1577.44    48.3 1606.39   42.33
 1613.62   42.28 1628.09   42.48 1646.23   49.16 1685.98    57.8 1707.69   60.83
  1729.4   67.82 1808.14   78.88 1880.66   84.66 1945.93   84.65 2076.47   92.72
  2163.5  100.16 2366.56  108.52 2603.44  122.05 3030.42   140.5 3179.89  143.62
#Mann= 3 , 0 , 0
       0      .1       0 1562.97     .04       0 1646.23      .1       0
#XS Ineff= 2 , 0
       0 1532.03      72               0
Permanent Ineff=
       F       F
Bank Sta=1562.97,1646.23
XS Rating Curve= 0 ,0
Exp/Cntr=0.5,0.3