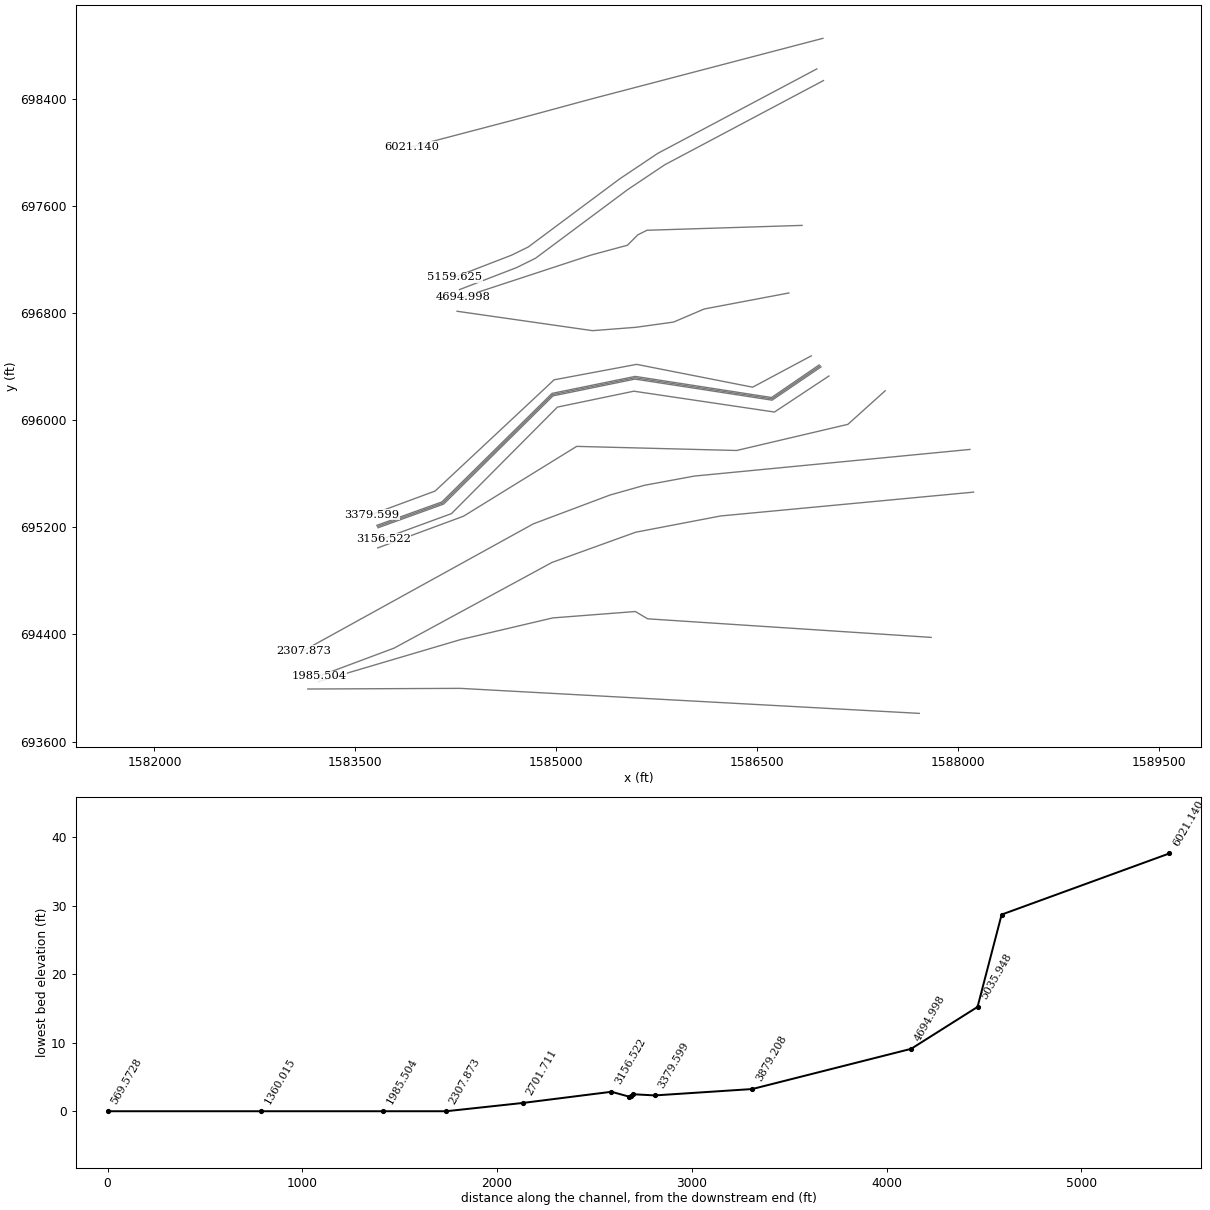
HEC-RAS study PrincipioCreek.prj: PrincipioCreek

--- PrincipioCreek.g01 (geometry) --- (continued)

Type RM Length L Ch R = 2 ,6124.285,,,
BEGIN DESCRIPTION:
Pulaski Highway, MDE Bridge #: CE032907FS-2
Top of road obtained from DEM.
Opening from MDE2 bridge/culvert surveys.
END DESCRIPTION:
Bridge Culvert--1,0,-1,-1, 0
Deck Dist Width WeirC Skew NumUp NumDn MinLoCord MaxHiCord MaxSubmerge Is_Ogee
78.1,107,2.6,0, 60, 60, , , 0.98, 0, 2,2,,
       0  173.66  188.14  246.02   260.5  318.38  397.98  513.75  578.88  593.35
  629.53  665.71  680.18  687.42  781.49  803.19  861.08  918.97  933.44  947.91
  1005.8 1020.27 1078.16 1121.58 1136.05 1179.46 1193.94 1222.88 1244.59 1309.71
 1331.42 1374.83 1411.01 1476.14 1541.26 1642.57 1765.58 1814.71 1865.48 1887.23
 1908.99 1967.01 2054.04 2141.06 2191.83 2213.59 2307.86 2358.63 2450.74 2479.68
 2494.16 2624.43 2689.56 2725.74 2761.93 2877.72 2979.04 3102.07  3167.2 3179.89
  116.26  110.67  110.47   108.5  108.29   106.1  103.91   99.94   98.05   97.93
   96.41   95.23   95.03   94.59    91.5   91.03   88.92   87.48   86.76   86.57
   84.56   84.39   82.15   81.12   80.33   79.04   78.05   77.22   76.97   75.02
   74.03   73.95    73.3   73.22   73.48   74.98   79.15    81.2   84.17   85.09
    86.5   89.37   94.34    98.9     102   102.9  108.28  110.76  116.08  117.35
  118.42  125.42  128.69   130.1   131.9  136.02  139.06   141.5  142.25  142.06
                                                                                
                                                                                
                                                                                
                                                                                
                                                                                
                                                                                
       0  173.66  188.14  246.02   260.5  318.38  397.98  513.75  578.88  593.35
  629.53  665.71  680.18  687.42  781.49  803.19  861.08  918.97  933.44  947.91
  1005.8 1020.27 1078.16 1121.58 1136.05 1179.46 1193.94 1222.88 1244.59 1309.71
 1331.42 1374.83 1411.01 1476.14 1541.26 1642.57 1765.58 1814.71 1865.48 1887.23
 1908.99 1967.01 2054.04 2141.06 2191.83 2213.59 2307.86 2358.63 2450.74 2479.68
 2494.16 2624.43 2689.56 2725.74 2761.93 2877.72 2979.04 3102.07  3167.2 3179.74
  116.26  110.67  110.47   108.5  108.29   106.1  103.91   99.94   98.05   97.93
   96.41   95.23   95.03   94.59    91.5   91.03   88.92   87.48   86.76   86.57
   84.56   84.39   82.15   81.12   80.33   79.04   78.05   77.22   76.97   75.02
   74.03   73.95    73.3   73.22   73.48   74.98   79.15    81.2   84.17   85.09
    86.5   89.37   94.34    98.9     102   102.9  108.28  110.76  116.08  117.35
  118.42  125.42  128.69   130.1   131.9  136.02  139.06   141.5  142.25  142.06
                                                                                
                                                                                
                                                                                
                                                                                
                                                                                
                                                                                
BR Coef=-1 , 0 , 0 ,, 0 ,,,0.8,-1,,0,
WSPro=,,,, 1 ,,,, 0 ,,,, 0 ,,,,-1 ,-1 ,-1 , 0 , 0 , 0 , 0 , 0
Culvert=9,21,65,133,0.017,0.7,1,61,1,42,1616,40,1610,Culvert #1  , 0 ,65.1
Culvert Bottom n=0.017
BC Design=,, 0 ,, 0 ,,,,,,
BC Use User HTab Curves=0
BC User HTab FreeFlow(D)= 0

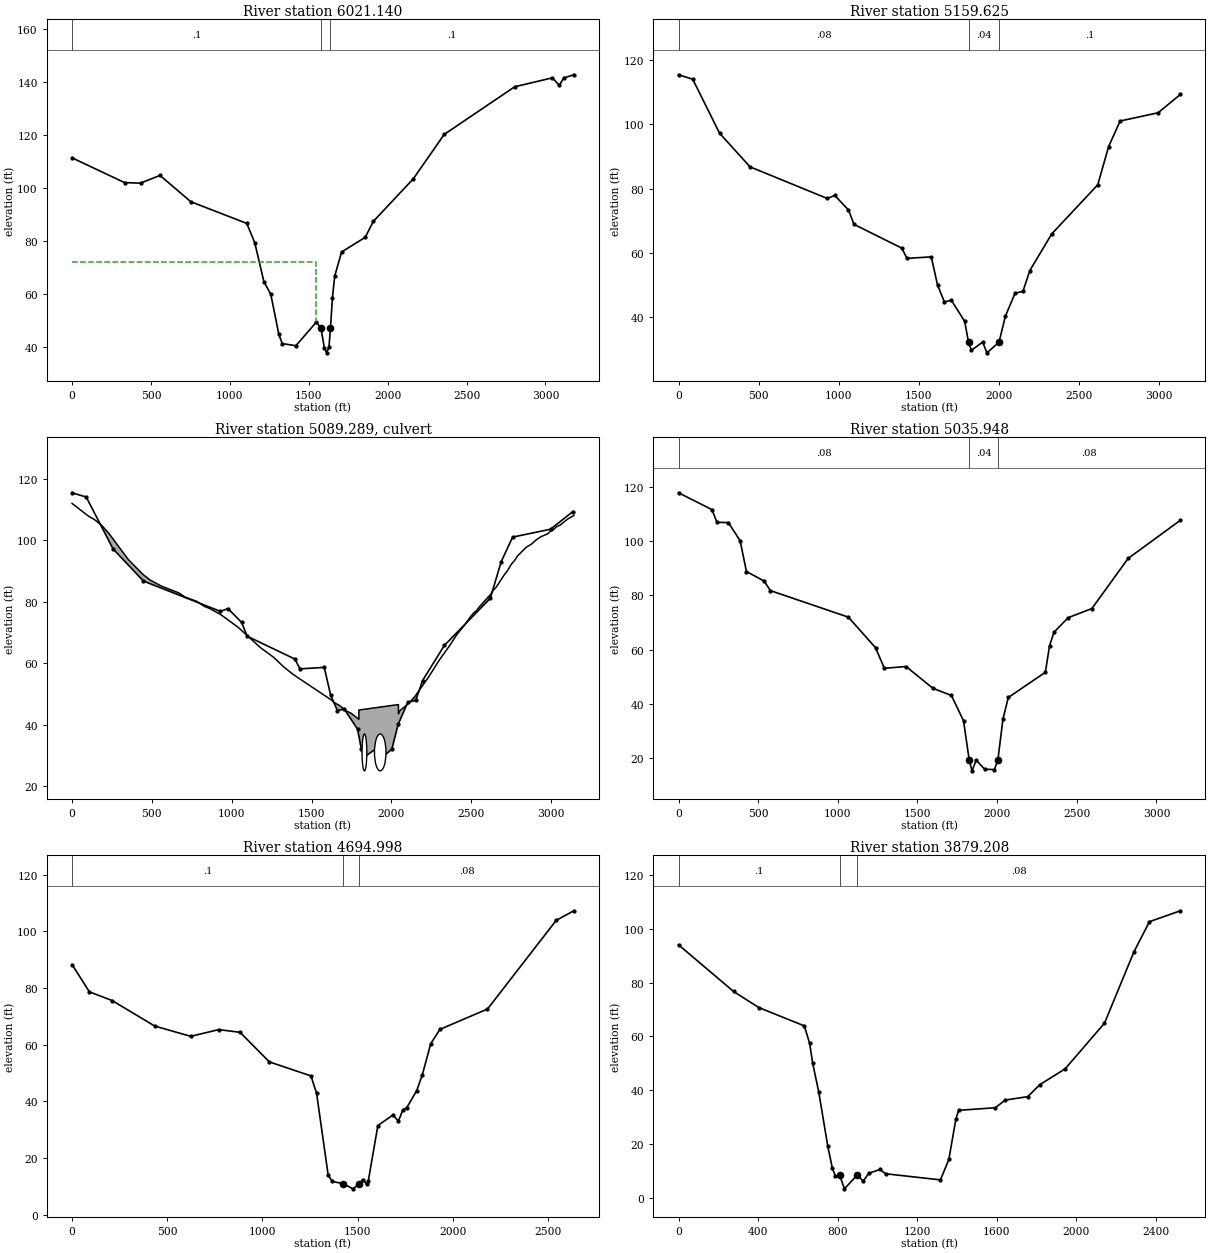
Type RM Length L Ch R = 1 ,6021.140,807.01,861.52,875.68
BEGIN DESCRIPTION:
Center of channel lowered 1.0 ft based on bridge survey info.
END DESCRIPTION:
XS GIS Cut Line= 4
1586992.63638598698852.1355987341585265.58777285698399.927883863
1584672.61273992698239.2982480821583918.04036868698041.240435258
#Sta/Elev= 30
       0  111.26  332.86   101.9  434.16  101.72  557.17  104.63  752.54   94.69
  1107.1   86.51 1157.76    79.2 1215.64   64.47 1259.06   59.79 1309.71    44.8
 1331.42   41.14 1418.25   40.33  1548.5   49.29 1577.44   46.85 1599.15   39.31
 1613.62   37.64 1628.09   39.98 1637.34   46.85  1649.8   58.43 1664.27   66.61
 1707.69    75.7 1857.79   81.26 1908.56   87.24 2162.39  103.35  2358.2   120.1
 2804.89   138.1 3043.71  141.46 3087.13  138.63 3116.08  141.45 3179.74  142.62
#Mann= 3 , 0 , 0
       0      .1       0 1577.44     .04       0 1637.34      .1       0
#XS Ineff= 2 , 0
       0 1546.78      72               0
Permanent Ineff=
       F       F
Bank Sta=1577.44,1637.34
XS Rating Curve= 0 ,0
Exp/Cntr=0.5,0.3

Type RM Length L Ch R = 1 ,5159.625,103.13,123.68,106.52
XS GIS Cut Line= 6
1586947.26505759698623.6830378771585758.95648338697992.832567096
1585474.94461469697802.6471354511584792.48469655697294.114747241
1584666.09992678697232.1322219671584241.11340791697068.163611129
#Sta/Elev= 30
       0   115.5   88.57  114.12  256.04   97.28  447.05   86.76  929.45   76.89
   976.2   77.82 1061.91   73.31 1096.38   68.82  1395.8   61.37 1427.34   58.19
 1579.34   58.67 1618.92   49.78 1661.06   44.63 1704.98    45.1 1787.66   38.59
 1812.19   32.01 1829.86    29.5 1900.57   32.06 1927.08   28.71 2002.79   32.04
 2042.45   40.15  2102.8   47.31 2152.22   47.93 2195.33    54.4 2331.64   65.81
 2619.48   81.15 2687.46   93.06  2759.3  101.07 2996.63  103.64  3135.6  109.35
#Mann= 3 , 0 , 0
       0     .08       0 1812.19     .04       0 2002.79      .1       0
Bank Sta=1812.19,2002.79
XS Rating Curve= 0 ,0
Exp/Cntr=0.5,0.3

Type RM Length L Ch R = 2 ,5089.289,,,
BEGIN DESCRIPTION:
Principio Furnance Road, MDE Bridge #: CE032907FS-1
Top of road obtained from DEM.
Opening from MDE2 bridge/culvert surveys.
END DESCRIPTION:
Bridge Culvert--1,0,-1,-1, 0
Deck Dist Width WeirC Skew NumUp NumDn MinLoCord MaxHiCord MaxSubmerge Is_Ogee
44.8,34,2.6,0, 60, 60, , , 0.98, 0, 2,2,,
       0  104.67  136.88  185.21  232.85  351.96  440.62  488.04  559.18  668.47
  708.16  779.59  827.21  861.53  931.66 1040.74  1177.6 1260.75 1325.74 1385.54
 1624.27 1641.12 1674.84 1717.63 1745.76 1796.25 1796.25 2044.02 2044.02 2050.78
 2104.13 2145.87 2232.09 2299.74 2363.82 2410.06 2456.95 2499.49  2522.9 2531.48
 2544.59 2623.35 2638.49 2654.43 2708.41 2723.33  2751.2 2773.98 2789.16 2843.74
 2877.86 2907.79 2937.72 2981.53 2996.57 3011.62 3034.18 3056.75 3101.88 3142.72
  112.02  107.82  106.89  104.93  102.13    93.8   89.08   87.13   85.13   82.92
   81.54   80.19   78.56   77.85   75.84   71.69   65.19   62.02   58.83   56.34
   48.05   47.23   46.28   44.49    43.8   41.79   44.79   46.57   43.57   44.47
    46.8   49.11   55.45   61.04   65.69   69.38   72.36   75.44   76.81   77.01
   78.02   82.56   83.83   84.64   88.91   89.84   92.24   93.64    94.9   97.75
   98.82  100.22  101.22  102.22  103.05  103.34  104.44  104.98  106.88  108.12
                                                                                
                                                                                
                                                                                
                                                                                
                                                                                
                                                                                
       0  104.67  136.88  185.21  232.85  351.96  440.62  488.04  559.18  668.47
  708.16  779.59  827.21  931.66 1040.74  1177.6 1260.75 1325.74 1385.54 1624.27
 1641.12 1674.84 1717.63 1745.76 1796.25 1796.25 2044.02 2044.02 2050.78 2104.13
 2145.87 2232.09 2299.74 2363.82 2410.06 2456.95 2499.49  2522.9 2531.48 2544.59
 2623.35 2638.49 2654.43 2708.41 2723.33  2751.2 2773.98 2789.16 2843.74 2877.86
 2907.79 2937.72 2981.53 2996.57 3004.09 3034.18 3071.79 3101.88 3124.45 3149.84
  112.02  107.82  106.89  104.93  102.13    93.8   89.08   87.13   85.13   82.92
   81.54   80.19   78.56   75.84   71.69   65.19   62.02   58.83   56.34   48.05
   47.23   46.28   44.49    43.8   41.79   44.79   46.57   43.57   44.47    46.8
   49.11   55.45   61.04   65.69   69.38   72.36   75.44   76.81   77.01   78.02
   82.56   83.83   84.64   88.91   89.84   92.24   93.64    94.9   97.75   98.82
  100.22  101.22  102.22  103.05  103.08  104.44  105.51  106.88  107.48   107.7
                                                                                
                                                                                
                                                                                
                                                                                
                                                                                
                                                                                
BR Coef=-1 , 0 , 0 ,, 0 ,,,0.8,-1,,0,
WSPro=,,,, 1 ,,,, 0 ,,,, 0 ,,,,-1 ,-1 ,-1 , 0 , 0 , 0 , 0 , 0
Culvert=9,12,30,34,0.017,0.7,1,61,1,25,1831,25,1838,Culvert #1  , 0 ,44.8
Culvert Bottom n=0.017
Culvert=9,12,72,35,0.017,0.7,1,61,1,25,1930,25,1960,Culvert #2  , 0 ,44.3
Culvert Bottom n=0.017
BC Design=,, 0 ,, 0 ,,,,,,
BC Use User HTab Curves=0
BC User HTab FreeFlow(D)= 0

Type RM Length L Ch R = 1 ,5035.948,348.37,340.95,280.9
XS GIS Cut Line= 6
1586996.68172008698536.7463168051585811.67417249697907.834091932
1585532.26345222697720.6814594121584846.31943749697209.702345669
1584704.74788406697139.8001181481584277.71703142696975.103551254
#Sta/Elev= 30
       0  117.86  209.66  111.64  241.42  106.94  312.89  106.87  386.78  100.12
  426.29    88.8  536.94   85.29  576.46   81.75 1066.32   71.95 1236.65   60.66
 1292.02   53.07 1428.12   53.74 1596.21   45.72 1712.96   43.04 1789.15   33.67
  1824.5   19.28 1842.18   15.23 1868.69   19.18 1921.72   15.82 1982.99    15.7
 2004.59   19.27 2036.65   34.41 2069.89    42.3 2302.74   51.61 2328.91   61.43
  2357.4   66.43 2445.33   71.75 2594.72   75.13 2821.85   93.61 3149.84   107.7
#Mann= 3 , 0 , 0
       0     .08       0  1824.5     .04       0 2004.59     .08       0
Bank Sta=1824.5,2004.59
XS Rating Curve= 0 ,0
Exp/Cntr=0.5,0.3

Type RM Length L Ch R = 1 ,4694.998,738.9,815.79,613
XS GIS Cut Line= 6
1586836.96279827697455.0101994871585678.22936058697418.555664375
1585610.52808106697384.7050246151585532.41122009697306.588163644
1585261.60610206697233.6790933911584302.07065986696918.607754171
#Sta/Elev= 30
       0   88.26   91.05   78.64   210.1   75.59  434.21   66.57  623.31   62.94
  770.38   65.32  882.44   64.36 1036.51   53.91  1254.8   48.97  1284.5   42.83
 1345.47   13.85 1367.22   11.73 1425.22   10.92 1475.96    9.11 1508.77   10.92
 1526.71   12.38 1548.45   10.72  1555.7   11.78 1606.45   31.46 1684.92   35.14
 1714.43   33.05 1736.55   36.81 1758.68   37.82 1810.31   43.75 1839.81   49.36
 1884.06   60.33 1931.83   65.39 2182.22   72.58 2543.08  103.87 2635.87  107.26
#Mann= 3 , 0 , 0
       0      .1       0 1425.22     .04       0 1508.77     .08       0
Bank Sta=1425.22,1508.77
XS Rating Curve= 0 ,0
Exp/Cntr=0.3,0.1

Type RM Length L Ch R = 1 ,3879.208,440.48,499.61,311.15
XS GIS Cut Line= 6
1586738.54177468696950.3468140361586105.64292799696830.458486244
1585877.01867503696732.8749636261585595.42050974696693.841554597
1585272.00083479696668.7486487931584259.92030025696813.729882389
#Sta/Elev= 30
       0   94.03  276.77   76.68  403.63    70.7  632.74   63.87  659.55   57.35
  674.77   49.94  705.22   39.29  750.88   19.01  773.71   10.94  788.94       8
  810.46    8.28   834.6    3.24  899.97    8.49  928.24    6.04  956.51    9.01
 1013.05   10.45 1041.31    8.85 1317.62    6.57 1359.74   14.21 1394.85   29.12
 1408.89   32.45  1593.6   33.42 1643.14   36.26 1756.39   37.54 1817.37      42
 1944.61   47.89 2142.54   64.88 2290.98   91.47 2368.74  102.64 2524.01   106.7
#Mann= 3 , 0 , 0
       0      .1       0  810.46     .04       0  899.97     .08       0
Bank Sta=810.46,899.97
XS Rating Curve= 0 ,0
Exp/Cntr=0.5,0.3

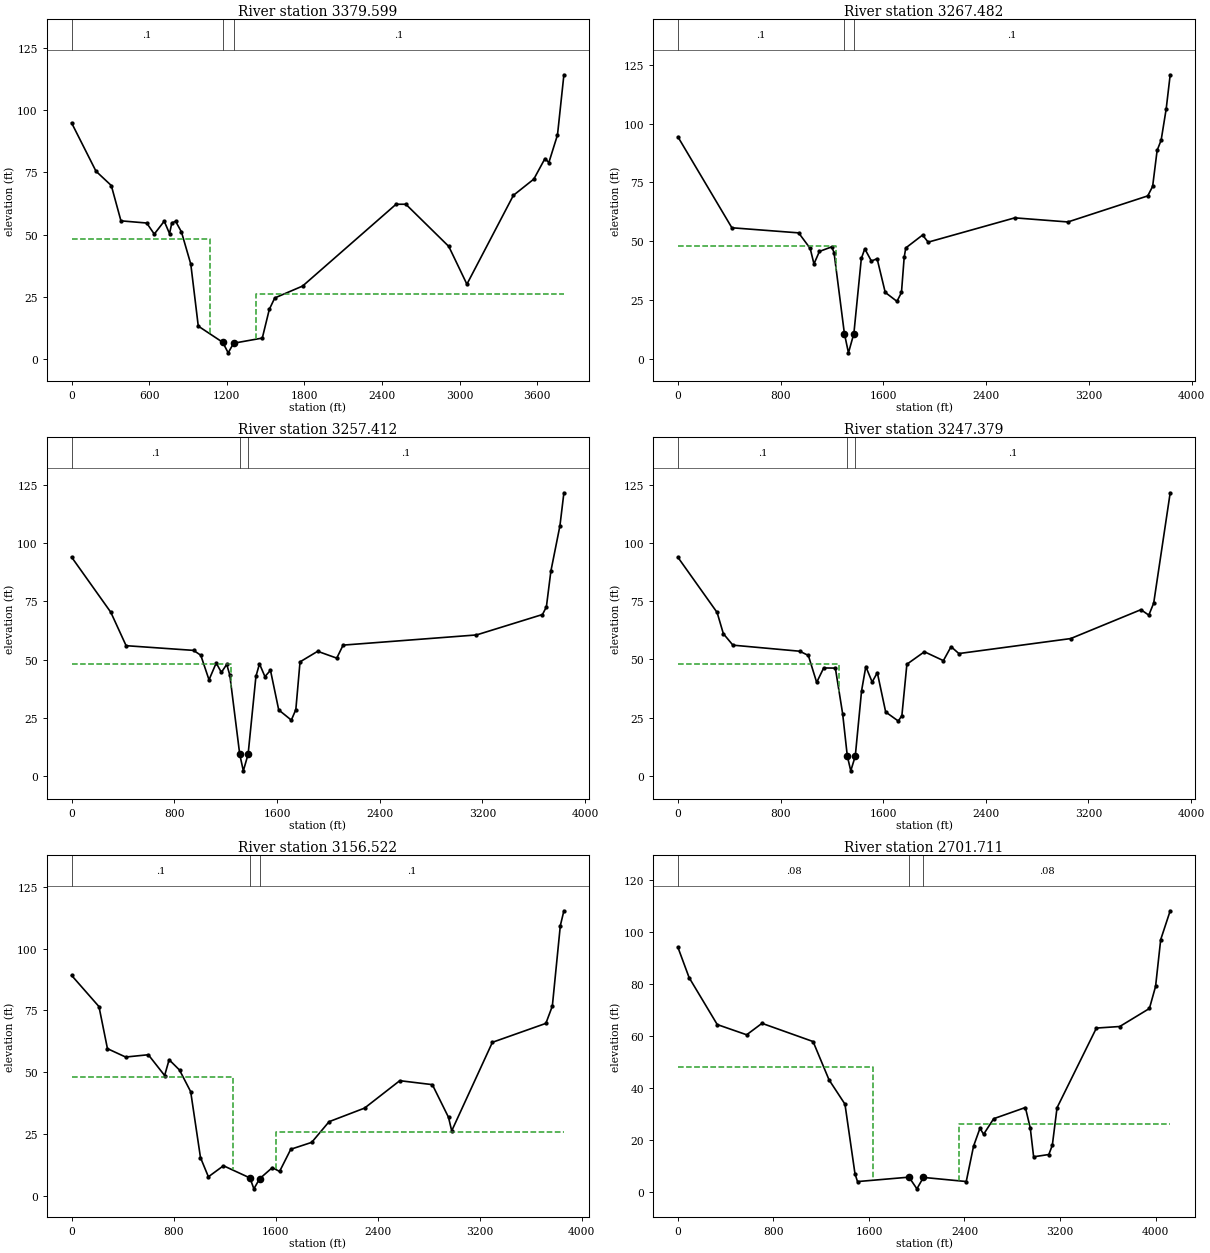
Type RM Length L Ch R = 1 ,3379.599,112.58,112.12,91.3
XS GIS Cut Line= 6
 1586905.6993679696480.5744499121586467.68506838696246.549486905
1585601.31841877696417.0479087681584984.93598917696301.581764176
1584096.37397341 695470.961128191583621.05087875695295.173366755
#Sta/Elev= 30
       0   94.99  188.62   75.51  306.99   69.74   381.5   55.51  580.66   54.63
  639.13   50.17  716.13   55.37  757.27   50.33  774.59   54.63   804.1   55.33
  849.27   51.04  921.44   38.06  979.29   13.08 1168.38    6.55  1210.5    2.31
 1252.62    6.19 1474.26    8.26 1528.59   19.86 1570.71   24.44 1785.66   29.22
 2508.37    62.2 2584.02    62.2 2915.87    45.2 3055.95   29.97 3415.34   65.79
  3573.3   72.33  3659.1   80.58 3689.56   79.01 3756.22   90.13 3805.83  114.38
#Mann= 3 , 0 , 0
       0      .1       0 1168.38     .04       0 1252.62      .1       0
#XS Ineff= 2 , 0
       0 1072.05      48 1421.94       0      26
Permanent Ineff=
       F       F
Bank Sta=1168.38,1252.62
XS Rating Curve= 0 ,0
Exp/Cntr=0.5,0.3

Type RM Length L Ch R = 1 ,3267.482,10.55,10.07,10.03
XS GIS Cut Line= 6
1586964.91425765696412.7983713151586609.07453966696169.371263251
1585591.21990854696327.047908783 1584969.5438436696200.335193351
1584146.88878177695389.4770090131583661.30010235695214.674919546
#Sta/Elev= 30
       0    94.4  420.35    55.7  939.88   53.53  1029.9   46.92 1059.24   40.32
 1101.76   45.63 1197.38   47.57 1215.55   45.16 1296.14    10.7 1327.86    2.48
 1369.97    10.7 1428.01   42.64    1455   46.74 1506.31   41.53 1550.87   42.55
 1614.09    28.2 1705.35   24.39 1740.45   28.16 1761.51   43.05 1773.82   47.11
 1904.68    52.6 1948.41   49.58 2622.59   59.92 3036.06   58.17 3657.56   69.26
 3695.64    73.3 3730.66   88.61 3761.96   92.98 3801.09  106.22  3832.4   120.8
#Mann= 3 , 0 , 0
       0      .1       0 1296.14     .04       0 1369.97      .1       0
#XS Ineff= 2 , 0
       0 1234.24      48 1405.07       0      26
Permanent Ineff=
       F       F
Bank Sta=1296.14,1369.97
XS Rating Curve= 0 ,0
Exp/Cntr=0.3,0.3

Type RM Length L Ch R = 1 ,3257.412,10.49,10.03,10.03
XS GIS Cut Line= 6
1586971.49368981696405.2676959041586611.05284533696159.512574628
1585590.09785183696317.0479087681584973.18948336696191.019641474
1584153.37560456695381.540080532 1583665.7722383695205.730647638
#Sta/Elev= 30
       0   93.99  305.19   70.34  424.67   55.97  949.95   53.95  1006.3   51.87
 1070.56   41.31 1126.47   48.54 1166.78    44.5 1208.54   47.94 1232.47   43.34
 1309.68    9.37 1337.76    2.24 1375.03    9.37 1435.93   42.81 1463.66   48.17
  1506.1   42.69 1549.25    45.4 1613.44    28.4 1711.71   24.01 1746.81   28.53
 1779.46   49.02 1916.83   53.56 2065.53   50.62 2115.01   56.21 3153.98   60.58
 3668.06   69.35 3698.52   72.61 3733.57   87.97 3804.01  107.42 3835.02  121.61
#Mann= 3 , 0 , 0
       0      .1       0 1309.68     .04       0 1375.03      .1       0
#XS Ineff= 2 , 0
       0 1245.53      48 1413.75       0      26
Permanent Ineff=
       F       F
Bank Sta=1309.68,1375.03
XS Rating Curve= 0 ,0
Exp/Cntr=0.3,0.3

Type RM Length L Ch R = 1 ,3247.379,94.66,90.86,95.34
XS GIS Cut Line= 6
1586978.07312201696397.7370205071586613.03115104696149.653886035
1585588.97579516696307.0479087681584976.83512317696181.704089627
1584159.86242738695373.6031520661583670.24437426695196.786375731
#Sta/Elev= 30
       0    93.9  305.83   70.18   354.4   61.07  428.99   56.14  949.85   53.53
 1016.97   51.71 1081.89   40.14 1136.61   46.35 1227.53   46.28 1284.48   26.61
 1320.76    8.44 1347.66    2.13 1382.75    8.44 1431.89   36.54 1464.91   46.92
  1514.4   40.28 1554.65   44.33  1619.8   27.41 1718.07   23.53 1746.15   25.88
  1785.1   47.94  1921.7    53.3 2069.57   49.49 2129.47   55.48 2190.37   52.53
 3061.81   58.97 3609.33   71.38 3670.94   69.04 3709.02   74.21 3837.64  121.62
#Mann= 3 , 0 , 0
       0      .1       0 1320.76     .04       0 1382.75      .1       0
#XS Ineff= 2 , 0
       0 1256.82      48 1422.42       0      26
Permanent Ineff=
       F       F
Bank Sta=1320.76,1382.75
XS Rating Curve= 0 ,0
Exp/Cntr=0.3,0.3

Type RM Length L Ch R = 1 ,3156.522,437.29,454.81,425.57
XS GIS Cut Line= 6
1587037.28801176696329.9609419111586630.83590218696060.925688565
1585580.64074557696216.6471222491585009.64588137696097.864122927
1584218.24383266695302.1707956791583710.49359787695116.287928551
#Sta/Elev= 30
       0   89.16  214.77   76.54   281.2   59.53  423.84   56.14   601.8   57.07
  729.78   48.67  764.84   55.06  846.29   50.89  934.01   42.13 1010.84   15.48
 1072.91    7.71 1191.18   12.18 1398.89    7.24 1429.74    2.84 1474.57    6.92
 1573.86   11.41  1631.3    9.88 1719.07   18.85 1882.93   21.63 2019.46      30
 2297.33   35.48 2573.83   46.58 2829.38   44.98 2956.09   31.77 2981.22   26.29
 3300.32    62.1 3719.63   69.75 3770.45   76.74 3833.06  109.28 3861.13  115.29
#Mann= 3 , 0 , 0
       0      .1       0 1398.89     .04       0 1474.57      .1       0
#XS Ineff= 2 , 0
       0 1263.21      48 1600.74       0      26
Permanent Ineff=
       F       F
Bank Sta=1398.89,1474.57
XS Rating Curve= 0 ,0
Exp/Cntr=0.5,0.3

Type RM Length L Ch R = 1 ,2701.711,398.83,393.84,454.31
XS GIS Cut Line= 6
1587457.87174143696219.8644447481587179.06167676695968.935386613
1586348.20768425695773.7683413481585153.50655735695804.437448457
1584308.71206158695283.0626276141583667.44891295695046.074072689
#Sta/Elev= 30
       0   94.05   94.18   82.36  329.61   64.34  575.92   60.41  704.32   64.81
 1132.07   57.81 1265.89   43.08 1399.02   33.76  1483.1    6.97 1504.12       4
 1935.44     5.7 2001.45    1.21 2056.06     5.6 2414.66    4.02 2475.96   17.62
 2529.53   24.48 2560.14   22.18 2644.31   28.16 2909.79   32.46 2950.73   24.61
 2978.89   13.52 3106.13    14.4 3135.49   17.96 3174.93   32.37 3504.53   62.99
 3700.06   63.59 3948.42   70.51 4000.09   79.01 4042.99   96.98 4122.49  108.06
#Mann= 3 , 0 , 0
       0     .08       0 1935.44     .04       0 2056.06     .08       0
#XS Ineff= 2 , 0
       0 1634.23      48  2351.7       0      26
Permanent Ineff=
       F       F
Bank Sta=1935.44,2056.06
XS Rating Curve= 0 ,0
Exp/Cntr=0.5,0.3

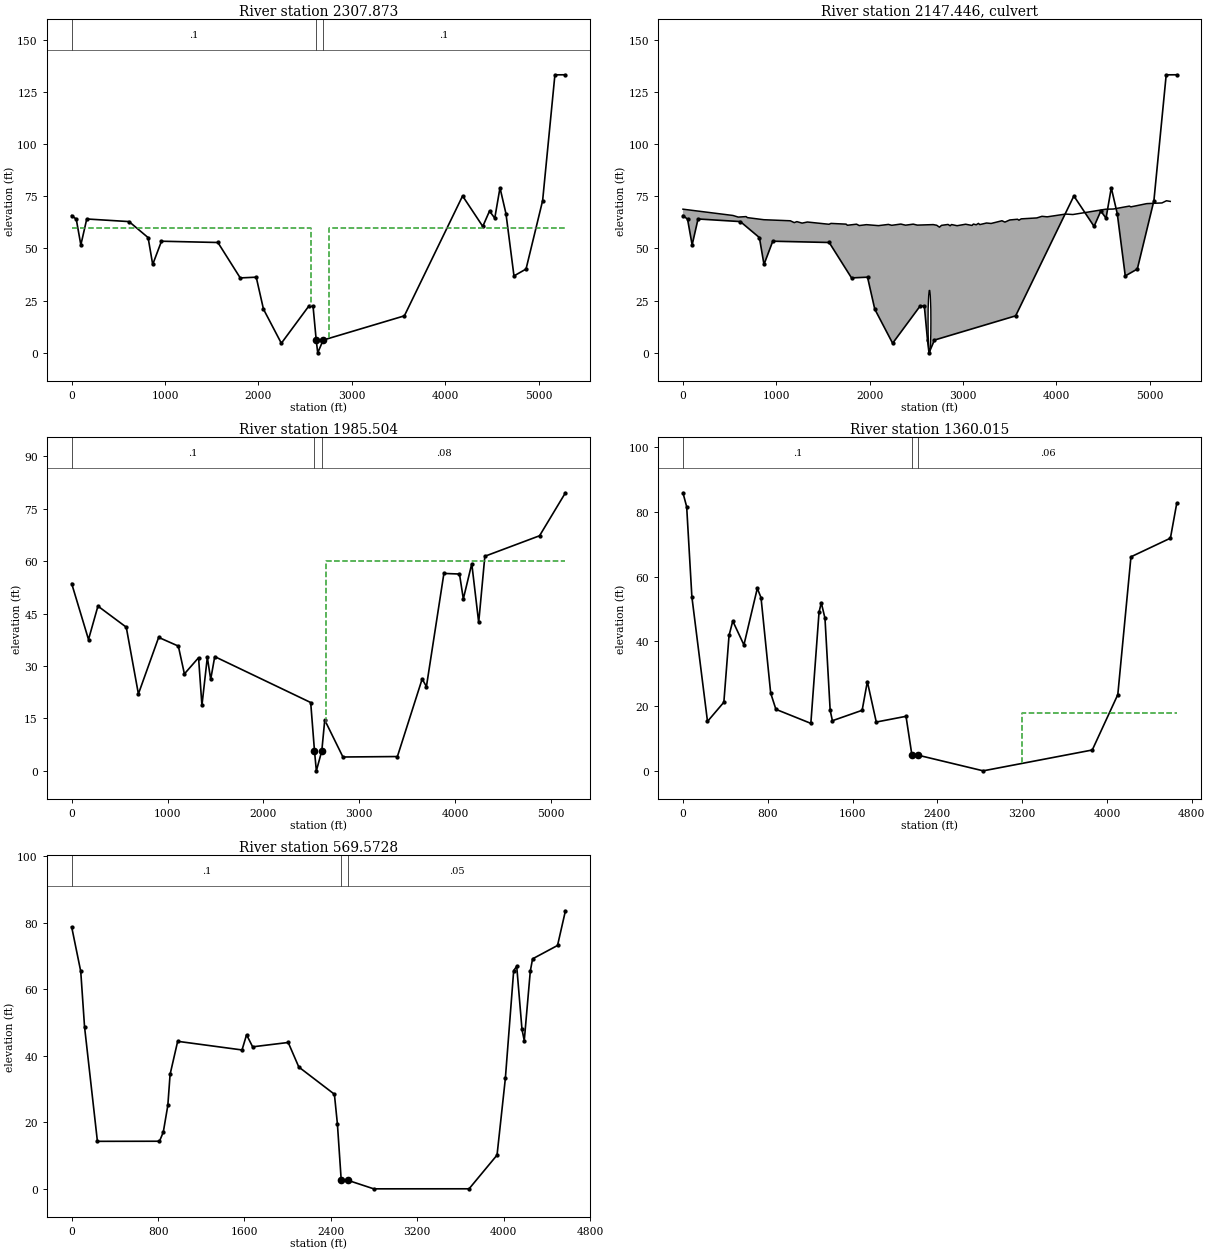
Type RM Length L Ch R = 1 ,2307.873,320.78,322.37,322.17
BEGIN DESCRIPTION:
Center of channel lowered 2.0 ft based on bridge survey info.
END DESCRIPTION:
XS GIS Cut Line= 6
1588090.77291404695781.6231504681586032.51516856695582.683806598
1585659.88748847695513.7749083941585402.03416185695440.973233193
1584829.92599683695225.9317399411583112.79496774694278.524237722
#Sta/Elev= 30
       0   65.72   49.17   63.99   98.35   51.67  161.57   64.09  614.44   62.84
  818.51   55.18  867.76   42.31  961.88   53.44 1565.96   52.83  1805.2   35.87
 1976.51   36.22 2054.11   20.91 2245.38    4.58 2541.43    22.5 2585.03   22.29
 2618.83    6.11    2635       0 2693.29    6.11 3562.84   17.71 4186.32   75.11
 4402.66   60.53 4474.77    67.9 4530.86   64.46 4586.95   79.01 4651.05   66.61
 4736.68   36.82 4865.84   40.12 5043.43   72.86 5175.09   133.1 5287.76  133.13
#Mann= 3 , 0 , 0
       0      .1       0 2618.83     .04       0 2693.29      .1       0
#XS Ineff= 2 , 0
       0 2563.82      60 2756.83       0      60
Permanent Ineff=
       F       F
Bank Sta=2618.83,2693.29
XS Rating Curve= 0 ,0
Exp/Cntr=0.5,0.3

Type RM Length L Ch R = 2 ,2147.446,,,
BEGIN DESCRIPTION:
Conrail Railroad, MDE Bridge #: CE033108FS-5
Top of road obtained from DEM.
Opening from MDE2 bridge/culvert surveys.
Opening approximated as a box culvert.
END DESCRIPTION:
Bridge Culvert--1,0,-1,-1, 0
Deck Dist Width WeirC Skew NumUp NumDn MinLoCord MaxHiCord MaxSubmerge Is_Ogee
141.2,40,2.6,0, 60, 60, , , 0.98, 0, 2,2,,
       0  535.56  591.86   676.3  690.37  866.29  1149.6 1191.77 1219.89 1276.13
 1332.36 1563.92 1585.03 1746.87 1760.94 1859.45  1887.6 1964.78 2093.72 2200.17
 2235.65 2333.44 2383.45 2466.15 2509.75 2680.47 2717.31 2746.79 2768.89  2838.8
 2861.14 2876.03 2935.59 3027.18 3095.13 3110.23 3140.44 3164.16 3179.04 3250.85
 3299.51 3416.15  3447.6 3499.58 3582.51 3598.44 3622.34 3789.04 3844.67 3900.58
 4097.39 4175.33 4527.89 4608.02 4780.74 4796.89  4966.4 5129.55 5177.89 5218.35
   68.78   65.77      65   65.23   64.74   63.74   63.23   62.35   62.82   62.11
   62.64   61.56   61.97   61.62   61.09    61.6   60.94   61.37    60.9   61.49
   61.06   61.66   61.12   61.62   61.15    61.4   61.08   60.18   61.04   61.47
   60.84   61.43   60.87   61.58      61   61.66   61.31   61.98    61.4   62.16
   61.94   63.24    62.6   63.62   63.96   63.51   64.15   64.59   65.37   65.12
   66.44   66.22   68.77   68.85   70.26   69.89   71.44   71.77   72.81   72.51
                                                                                
                                                                                
                                                                                
                                                                                
                                                                                
                                                                                
       0  535.56  591.86   676.3  690.37  866.29  1149.6 1191.77 1219.89 1276.13
 1332.36 1563.92 1585.03 1746.87 1760.94 1859.45  1887.6 1964.78 2093.72 2200.17
 2235.65 2333.44 2383.45 2466.15 2509.75 2680.47 2717.31 2746.79 2768.89  2838.8
 2861.14 2876.03 2935.59 3027.18 3095.13 3110.23 3140.44 3164.16 3179.04 3250.85
 3299.51 3416.15  3447.6 3499.58 3582.51 3598.44 3622.34 3789.04 3844.67 3900.58
 4097.39 4175.33 4527.89 4608.02 4780.74 4796.89  4966.4 5129.55 5177.89 5218.35
   68.78   65.77      65   65.23   64.74   63.74   63.23   62.35   62.82   62.11
   62.64   61.56   61.97   61.62   61.09    61.6   60.94   61.37    60.9   61.49
   61.06   61.66   61.12   61.62   61.15    61.4   61.08   60.18   61.04   61.47
   60.84   61.43   60.87   61.58      61   61.66   61.31   61.98    61.4   62.16
   61.94   63.24    62.6   63.62   63.96   63.51   64.15   64.59   65.37   65.12
   66.44   66.22   68.77   68.85   70.26   69.89   71.44   71.77   72.81   72.51
                                                                                
                                                                                
                                                                                
                                                                                
                                                                                
                                                                                
BR Coef=-1 , 0 , 0 ,, 0 ,,,0.8,-1,,0,
WSPro=,,,, 1 ,,,, 0 ,,,, 0 ,,,,-1 ,-1 ,-1 , 0 , 0 , 0 , 0 , 0
Culvert=9,30,30,200,0.015,0.7,1,60,1,0,2640,0,2576,Culvert #1  , 0 ,61.2
Culvert Bottom n=0.015
BC Design=,, 0 ,, 0 ,,,,,,
BC Use User HTab Curves=0
BC User HTab FreeFlow(D)= 0

Type RM Length L Ch R = 1 ,1985.504,648.33,625.49,656.44
BEGIN DESCRIPTION:
Center of channel lowered 2.0 ft based on bridge survey info.
END DESCRIPTION:
XS GIS Cut Line= 6
1588117.59888704695462.7495592531586229.40176503 695284.80432117
1585594.03639089695163.3108822411584968.95100623694937.539022267
1583790.52148458694298.0684732791583229.78817338 694088.38883312
#Sta/Elev= 30
       0    53.6  175.62   37.58  273.96   47.14  569.27   41.11  695.94   22.01
  907.04   38.19 1112.37    35.7 1175.64   27.74 1323.26   32.38  1358.4   18.71
 1414.64    32.5 1449.79   26.18 1491.96   32.69 2492.59   19.55 2532.04    5.73
 2551.65       0 2608.49    5.73 2639.08   14.54  2828.8    3.96 3396.73    4.09
 3654.85   26.28 3699.38   24.11 3881.65   56.49 4044.16   56.32 4084.22    49.2
 4172.36   59.27 4244.48   42.45 4308.58    61.4 4879.19   67.27 5149.02   79.57
#Mann= 3 , 0 , 0
       0      .1       0 2532.04     .04       0 2608.49     .08       0
#XS Ineff= 2 , 0
       0                 2654.41       0      60
Permanent Ineff=
       F       F
Bank Sta=2532.04,2608.49
XS Rating Curve= 0 ,0
Exp/Cntr=0.5,0.3

Type RM Length L Ch R = 1 ,1360.015,775.16,790.44,891.29
XS GIS Cut Line= 6
1587800.90812634694377.8030915861585683.75383918694516.521117598
1585591.43900111694571.0279457721584974.62640138 694523.27471225
1584285.75974758 694361.188440741583227.64047481694048.368400827
#Sta/Elev= 30
       0   85.93   35.08    81.6   84.18   53.77   231.5   15.27  385.83    21.2
  434.93   41.85  470.01   46.29  575.23   38.91   701.5   56.41  736.58   53.51
  827.77   24.01  876.88   19.01 1206.58   14.67 1283.75   48.95 1304.79   51.98
 1339.87   47.17 1388.97   18.67 1410.02   15.49 1690.62   18.71 1739.72   27.58
  1823.9   15.08  2104.5   16.85 2160.35    4.83 2219.24    4.83 2832.71       0
 3861.82    6.44 4102.71   23.55  4226.8   66.14 4599.06    71.9 4658.62   82.64
#Mann= 3 , 0 , 0
       0      .1       0 2160.35     .04       0 2219.24     .06       0
#XS Ineff= 2 , 0
                         3201.94              18
Permanent Ineff=
       F       F
Bank Sta=2160.35,2219.24
XS Rating Curve= 0 ,0
Exp/Cntr=0.3,0.1

Type RM Length L Ch R = 1 ,569.5728,515.33,569.57,224.7
XS GIS Cut Line= 3
1587712.28465272693810.2792869361584282.82422693693997.128436118
1583145.62773022693992.208524331
#Sta/Elev= 30
       0   78.74   84.12   65.35  119.18   48.72  238.35   14.28   813.2   14.31
  848.26   17.05  890.32   25.07  911.35   34.42  981.45   44.35 1577.33   41.75
  1619.4   46.32 1675.48   42.69 2004.97      44 2103.11   36.62 2432.61   28.44
 2460.65   19.43  2495.7    2.61 2560.65    2.53 2797.15       0 3679.57     .01
 3938.57   10.15 4015.57   33.21 4092.57   65.59 4120.57   66.93 4169.57   47.92
 4190.57   44.57 4246.57   65.47 4267.57   69.14 4498.57   73.16 4571.77   83.59
#Mann= 3 , 0 , 0
       0      .1       0  2495.7     .04       0 2560.65     .05       0
Bank Sta=2495.7,2560.65
XS Rating Curve= 0 ,0
Exp/Cntr=0.3,0.1

Chan Stop Cuts=-1
Use User Specified Reach Order=0
User Specified Reach Order=PrincipioCreek  ,Reach1