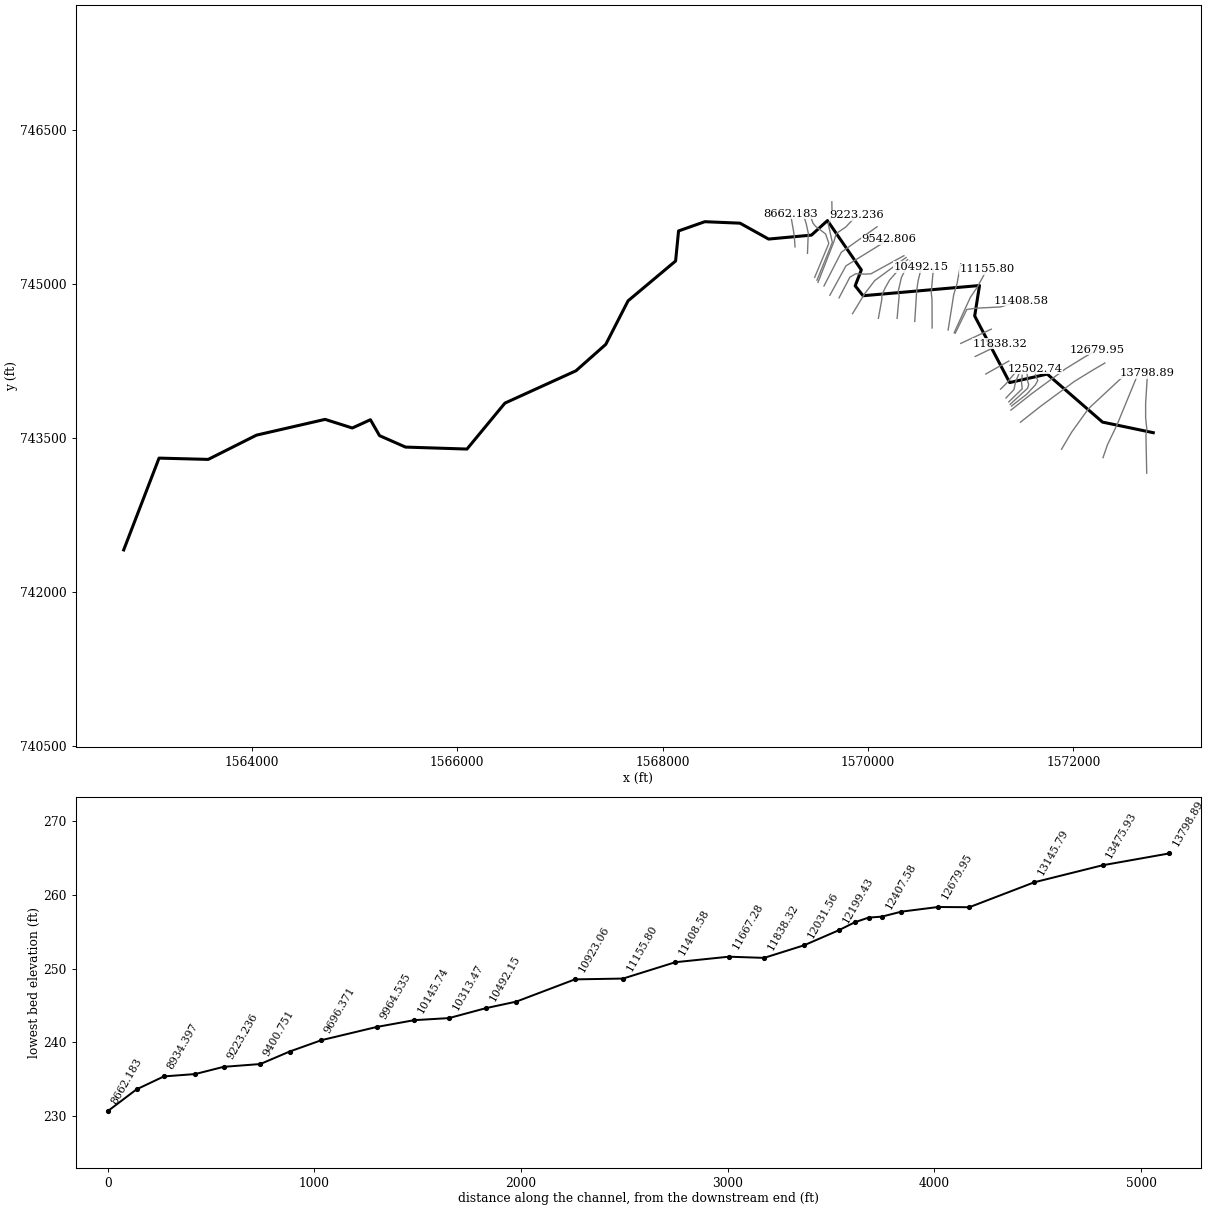
--- StoneRun.prj (project) ---

Proj Title=StoneRun
Current Plan=p01
Default Exp/Contr=0.3,0.1
English Units
Geom File=g01
Flow File=f01
Plan File=p01
Y Axis Title=Elevation
X Axis Title(PF)=Main Channel Distance
X Axis Title(XS)=Station
BEGIN DESCRIPTION:
Stone Run - Georeferenced HEC-RAS model.  This was formerly an approximate method stream.  Projection:  MD Stateplane.  Horizontal datum:  NAD83.  Vertrial datum: NAVD88.  Units:Feet.  Created by: Aaron W. Buesing, USACE- St Paul District as part of FEMA Map Modernization study for Cecil County, MD.
END DESCRIPTION:
DSS Export Rating Curves= 0
DSS Export Rating Curve Sorted= 0
DSS Export Volume Flow Curves= 0
DXF OffsetX= 0
DXF OffsetY= 0
DXF ScaleX= 1
DXF ScaleY= 10

--- StoneRun.p01 (plan) ---

Plan Title=StoneRun_100yr
Program Version=4.00
Short Identifier=StoneRun100
Geom File=g01
Flow File=f01
Subcritical Flow
K Sum by GR= 0
Std Step Tol= 0.01
Critical Tol= 0.01
Num of Std Step Trials= 20
Max Error Tol= 0.3
Flow Tol Ratio= 0.001
Split Flow NTrial= 30
Split Flow Tol= 0.02
Split Flow Ratio= 0.02
Log Output Level= 0
Friction Slope Method= 1
Unsteady Friction Slope Method= 2
Unsteady Bridges Friction Slope Method= 1
Secant Critical Depth
Global Vel Dist= 0 , 0 , 0
Global Log Level= 0
CheckData=True
Encroach Param=-1 ,0,0, 0
Computation Interval=1HOUR
Output Interval=1HOUR
Run HTab= 0
Run UNet= 0
Run PostProcess= 0
Run WQNet= 0
UNET Theta= 1
UNET Theta Warmup= 1
UNET ZTol= 0.02
UNET ZSATol= 0.05
UNET MxIter= 20
UNET MaxInSteps= 0
UNET DtIC= 0
UNET DtMin= 0
UNET MaxCRTS= 20
UNET WFStab= 2
UNET SFStab= 1
UNET WFX= 1
UNET SFX= 1
UNET DSS MLevel= 4
UNET DZMax Abort= 100
UNET Convert EG Bridges= 0
UNET Use Existing IB Tables=-1
UNET Froude Reduction=False
UNET Froude Limit= 1
UNET Froude Power= 10
UNET Time Slicing=0,0, 5
Instantaneous Interval=1HOUR
Write IC File= 0
Echo Input=False
Echo Output=False
Write Detailed= 0
Detailed Automatic Start=False, 10
WQ ULTIMATE=-1
WQ Max Comp Step=1HOUR
WQ Output Interval=15MIN
WQ Output Selected Increments= 0
WQ Output face flow=0
WQ Output face velocity=0
WQ Output face area=0
WQ Output face dispersion=0
WQ Output cell volume=0
WQ Output cell surface area=0
WQ Output cell continuity=0
WQ Output face conc=0
WQ Output face dconc_dx=0
WQ Output face courant=0
WQ Output face peclet=0
WQ Output face adv mass=0
WQ Output face disp mass=0
WQ Output cell mass=0
WQ Output cell source sink temp=0
WQ Output cell source sink nsm=0
WQ Output MaxMinRange=-1
WQ Create Restart=0
WQ Fixed Restart=0
Sorting and Armoring Iterations= 10
XS Update Threshold= 0.02
Hydraulics Update Threshold= 0.02
Energy Slope Method= 1
Volume Change Method= 0
XS Weighting Method= 0
Number of US Weighted Cross Sections= 1
Number of DS Weighted Cross Sections= 1
Upstream XS Weight=0.25
Main XS Weight=0.5
Downstream XS Weight=0.25
Number of DS XS's Weighted with US Boundary= 1
Upstream Boundary Weight= 1
Weight of XSs Associated with US Boundary= 0
Number of US XS's Weighted with DS Boundary= 1
Downstream Boundary Weight= 0.5
Weight of XSs Associated with DS Boundary= 0.5
Sediment Output Level= 4
Mass or Volume Output= 0
Output Increment Type= 1
Profile and TS Output Increment= 10
XS Output Flag= 0
XS Output Increment= 10
Disregard all LS=0
Disregard all Conn=0
Disregard all Breaches=0
Disregard all Pumps=0

--- StoneRun.f01 (steady flow) ---

Flow Title=StoneRun_100yr
Program Version=4.00
Number of Profiles= 2
Profile Names=100CUR,100ULT
River Rch & RM=StoneRun,Reach1          ,13798.89
    4270    5740
River Rch & RM=StoneRun,Reach1          ,12502.74
    4340    5810
River Rch & RM=StoneRun,Reach1          ,11838.32
    4590    6040
River Rch & RM=StoneRun,Reach1          ,9223.236
    4690    6120
River Rch & RM=StoneRun,Reach1          ,9085.740
    4790    6230
River Rch & RM=StoneRun,Reach1          ,4634.494
    5130    6600
River Rch & RM=StoneRun,Reach1          ,2739.274
    5300    6830
River Rch & RM=StoneRun,Reach1          ,1621.230
    5610    7080
Boundary for River Rch & Prof#=StoneRun,Reach1          , 1
Up Type= 0
Dn Type= 3
Dn Slope=0.006
Boundary for River Rch & Prof#=StoneRun,Reach1          , 2
Up Type= 0
Dn Type= 3
Dn Slope=0.006
DSS Import GetInterval= 0
DSS Import GetPeak= 0
DSS Import FillOption= 0

--- StoneRun.g01 (geometry) ---

Geom Title=StoneRun
Program Version=4.00

River Reach=StoneRun        ,Reach1
Reach XY= 30
 1572778.3877354743553.6309450271572284.21191433743656.784150407
1571745.65622582 744124.571942211571379.82218349744041.809486732
1571039.17671458744690.1153879311571085.95549379744986.980717361
1569951.98990819744887.4258796271569875.22473209744984.221968845
1569935.19752592745138.9517768921569605.34715991745619.333855405
1569449.41789599745477.7980619821569032.00725096745439.415473953
1568753.73348767745594.1452820151568410.68910697745608.538752526
 1568155.2050053  745518.5795618 1568126.4180643 745225.91232793
1567663.42809601744837.8883519171567446.32658236 744413.88069959
1567156.05826026744156.5974141211566463.97221953743841.740246549
1566094.53980961743394.3432046471565496.01132727743413.534498662
1565242.92613736743525.0838951621565154.16640252743679.813703254
1564977.84638867743599.4501595051564712.76663998743683.412070856
1564044.66971682743529.8817186651563574.48301323743293.588911012
1563095.66022737743306.1831977221562751.41639087742411.988841847

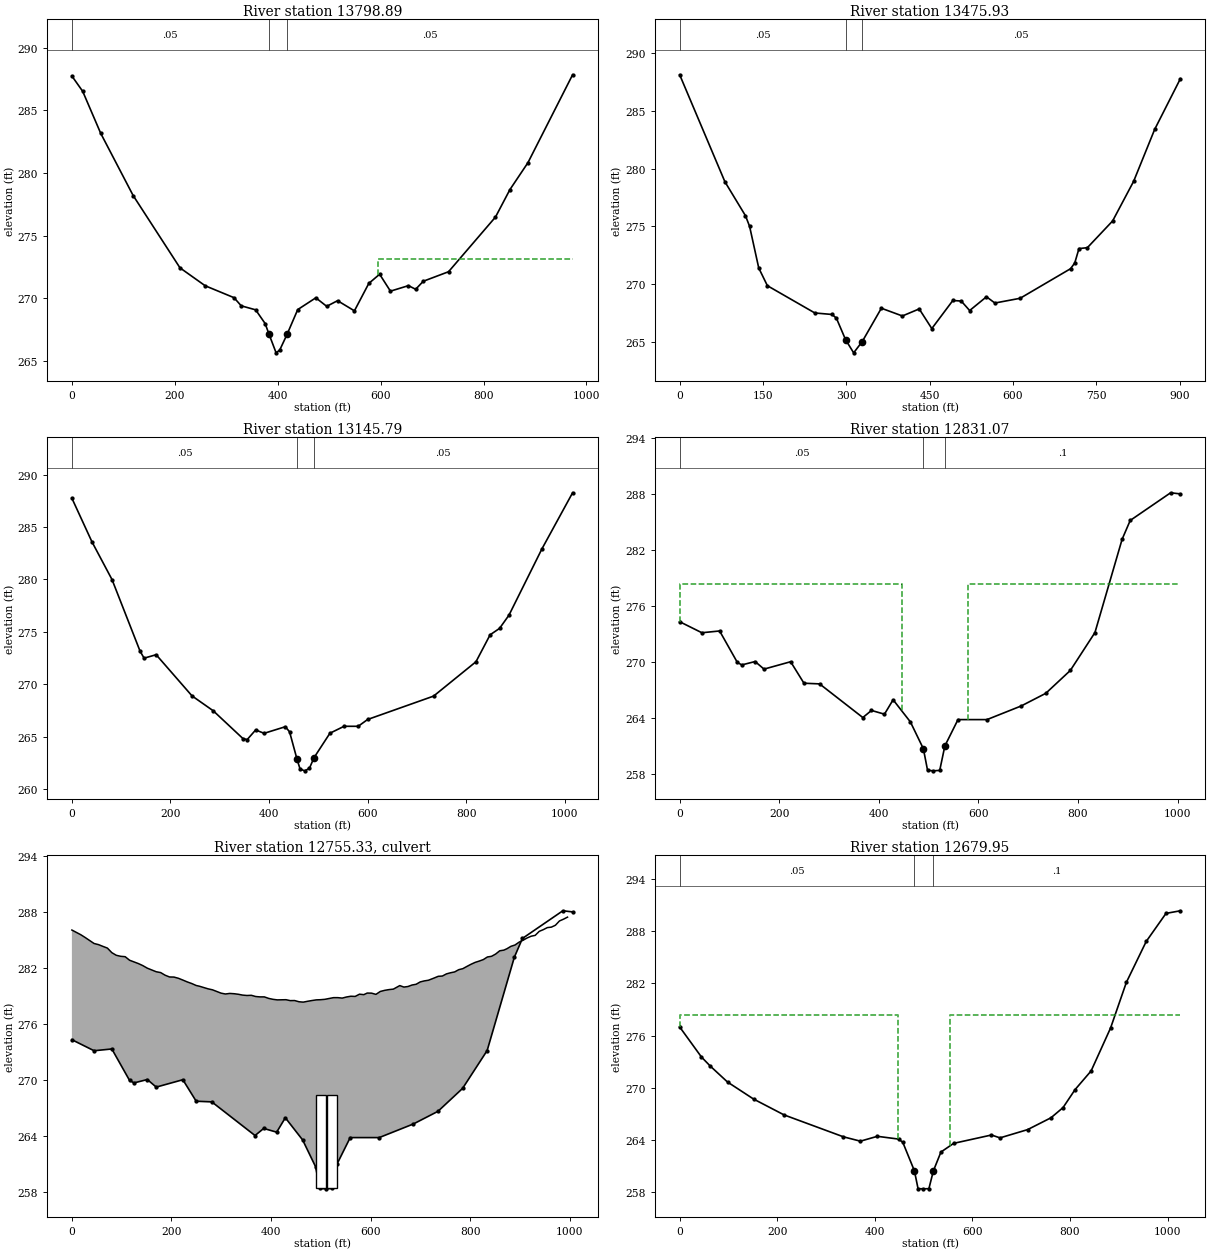
Type RM Length L Ch R = 1 ,13798.89,339.52,322.96,248.2
XS GIS Cut Line= 6
1572714.50066181743159.3743496241572706.92905347743534.774691805
1572716.01498351743583.2329852731572703.90041015743699.835753948
1572703.90041015743840.6676693111572722.13488176744130.235200673
#Sta/Elev= 30
       0  287.74      21  286.52   56.01  283.17  119.02  278.21  210.04  272.44
  259.05  271.01  315.06  270.06  329.07  269.41  357.07  269.09  375.48     268
   382.6   267.2  396.84  265.66  403.96  265.89  418.21  267.14  438.85  269.11
  474.04  270.05  495.16  269.37  516.27  269.82  549.01  269.01  577.01   271.2
  598.01  271.93  619.01  270.58  654.01  271.02  668.01  270.73  682.84  271.37
  731.94  272.13  823.12  276.49  851.17  278.68  886.24  280.83  972.98  287.84
#Mann= 3 , 0 , 0
       0     .05       0   382.6     .04       0  418.21     .05       0
#XS Ineff= 2 , 0
                          595.35          273.12
Permanent Ineff=
       F       F
Bank Sta=382.6,418.21
XS Rating Curve= 0 ,0
Exp/Cntr=0.3,0.1

Type RM Length L Ch R = 1 ,13475.93,341.24,330.14,279.8
XS GIS Cut Line= 4
1572288.97627236 743310.65508455 1572332.8916008 743437.85810487
 1572425.2652227743630.1769570861572635.75593495744142.017681807
#Sta/Elev= 30
       0  288.11   81.46  278.85  118.49  275.91  125.89  274.99  142.34  271.39
  157.87  269.86  243.29   267.5  274.35  267.37  282.12  267.05  298.62  265.19
  313.18  264.05  328.71  265.03  363.06  267.91   400.9  267.24  431.18  267.85
  453.89  266.15  491.73  268.58  506.87  268.53  522.01  267.71  552.28   268.9
  567.42  268.36  612.83  268.77  703.66  271.33  711.23  271.83  718.79  273.07
  733.93  273.15  779.34  275.46  817.19  278.89  855.03  283.38  901.35  287.77
#Mann= 3 , 0 , 0
       0     .05       0  298.62     .04       0  328.71     .05       0
Bank Sta=298.62,328.71
XS Rating Curve= 0 ,0
Exp/Cntr=0.3,0.1

Type RM Length L Ch R = 1 ,13145.79,347.8,314.72,302.65
XS GIS Cut Line= 5
1571884.73553057743392.6041316091571982.86826707743557.794237986
1572134.97400855743770.4151669891572169.32046629743808.032715961
1572543.86041048744156.403930396
#Sta/Elev= 30
       0  287.75   40.71  283.59   81.42  279.99  138.41  273.15  146.56  272.49
  170.98  272.82  243.78  268.89  286.81  267.47  347.06  264.82  355.67  264.72
  372.88  265.64   390.1  265.32  433.13  265.95  441.74  265.46   456.8  262.85
  463.05  261.91  472.52  261.74     482  261.98  491.24  262.99  523.63  265.33
  552.31  265.99  580.99  265.99   600.1  266.64  733.94  268.87  819.98  272.15
  848.66  274.72  867.78  275.33   886.9  276.59  953.82  282.92 1016.02  288.27
#Mann= 3 , 0 , 0
       0     .05       0   456.8     .04       0  491.24     .05       0
Bank Sta=456.8,491.24
XS Rating Curve= 0 ,0
Exp/Cntr=0.5,0.3

Type RM Length L Ch R = 1 ,12831.07,154.12,151.12,153.66
BEGIN DESCRIPTION:
Center of channel lowered 1.0 ft based on bridge survey info.
END DESCRIPTION:
XS GIS Cut Line= 6
1571484.67384726743655.915905863 1571684.8456223743813.774947882
1571955.61300507744012.7726629671572005.39102648744050.106179029
1572185.12747583 744160.849561931572307.03984427744232.371484727
#Sta/Elev= 30
       0   274.3   44.57  273.12   80.23  273.31  115.89  269.94  124.81  269.68
  151.55  270.04  169.38  269.23  222.87  270.02  249.62  267.72  280.99  267.65
  367.86  264.05  385.24  264.81   411.3  264.41  428.67  265.95  463.42  263.58
  489.48  260.71  497.89   258.4  509.72  258.35   522.3   258.4  532.59  261.01
  558.98  263.83  617.21  263.83  685.99  265.29  735.28  266.64  784.66  269.09
  834.04  273.14  888.64  283.12  904.87  285.13  986.03  288.09 1005.64  287.97
#Mann= 3 , 0 , 0
       0     .05       0  489.48     .04       0  532.59      .1       0
#XS Ineff= 2 , 0
       0   447.5  278.32  578.91       0  278.32
Permanent Ineff=
       F       F
Bank Sta=489.48,532.59
XS Rating Curve= 0 ,0
Exp/Cntr=0.5,0.3

Type RM Length L Ch R = 2 ,12755.33,,,
BEGIN DESCRIPTION:
Conowingo Road, MDE Bridge #: CE042407FS-11
Top of road obtained from DEM.
Opening from MDE2 bridge/culvert surveys.
END DESCRIPTION:
Bridge Culvert--1,0,-1,-1, 0
Deck Dist Width WeirC Skew NumUp NumDn MinLoCord MaxHiCord MaxSubmerge Is_Ogee
50.5,50,2.6,0, 117, 117, , , 0.95, 0, 2,2,,
       0    8.91   17.83   26.74   35.66   44.57   53.49    62.4   71.32   80.23
   89.15   98.06  106.98  115.89  124.81  133.72  142.64  151.55  160.47  169.38
   178.3  187.21  196.13  205.04  213.96  222.87  231.79   240.7  249.62   256.2
  264.89  273.58  282.26  290.95  299.64  308.32  317.01   325.7  334.39  343.07
  351.76  360.45  369.14  377.82  386.51   395.2  403.88  412.57  421.26  429.95
  438.63  447.32  456.01  464.69  473.38  482.07  490.76  499.44  508.13  516.82
   525.5  534.19  542.88  551.57  560.25  568.94  577.63  586.31  593.14  601.89
  610.64  619.39  628.14  636.89  645.64  658.56  666.77  674.97  683.17  691.38
  699.58  707.78  715.99  727.57   735.8  744.03  752.26  760.49  768.72  776.95
  785.18  793.41  801.64  809.87   818.1  826.33  834.56  842.79  851.02  859.25
  867.48  873.72  881.83  889.95  898.06  906.18  914.29  922.41  930.53  938.64
  946.76  954.87  962.99   971.1  979.22  987.34  995.45
  286.03  285.78  285.53  285.23  284.91  284.59  284.47  284.28   284.1  283.61
  283.33  283.22  283.18   282.8  282.62  282.44  282.22  281.95  281.76  281.57
  281.48   281.2  281.01     281  280.87  280.68  280.48  280.31   280.1  280.02
  279.88  279.74  279.64  279.46  279.28  279.19  279.25  279.22  279.16  279.07
  279.03  279.05  278.92  278.88  278.88  278.72  278.62  278.56  278.57  278.58
  278.48  278.49  278.36  278.32  278.41  278.49  278.56  278.58  278.62  278.71
   278.8   278.8  278.75  278.87  278.95  278.93  279.17  279.12  279.29  279.28
  279.15  279.46  279.58  279.66  279.71  280.09  279.93  279.99  280.15  280.23
  280.48  280.59  280.66   280.9  281.08  281.11  281.34  281.46  281.55  281.79
   281.9  282.14  282.37  282.57  282.71  282.87  283.15  283.22  283.46  283.81
  283.88  284.03  284.29  284.43  284.73  284.94  285.18  285.37  285.46  285.89
  286.07  286.29  286.34  286.54     287  287.19  287.41
                                                                                
                                                                                
                                                                                
                                                                                
                                                                                
                                                                                
                                                                                
                                                                                
                                                                                
                                                                                
                                                                                
                                                        
       0    8.91   17.83   26.74   35.66   44.57   53.49    62.4   71.32   80.23
   89.15   98.06  106.98  115.89  124.81  133.72  142.64  151.55  160.47  169.38
   178.3  187.21  196.13  205.04  213.96  222.87  231.79   240.7  249.62   256.2
  264.89  273.58  282.26  290.95  299.64  308.32  317.01   325.7  334.39  343.07
  351.76  360.45  369.14  377.82  386.51   395.2  403.88  412.57  421.26  429.95
  438.63  447.32  456.01  464.69  473.38  482.07  490.76  499.44  508.13  516.82
   525.5  534.19  542.88  551.57  560.25  568.94  577.63  586.31  593.14  601.89
  610.64  619.39  628.14  636.89  645.64  658.56  666.77  674.97  683.17  691.38
  699.58  707.78  715.99  727.57   735.8  744.03  752.26  760.49  768.72  776.95
  785.18  793.41  801.64  809.87   818.1  826.33  834.56  842.79  851.02  859.25
  867.48  873.72  881.83  889.95  898.06  906.18  914.29  922.41  930.53  938.64
  946.76  954.87  962.99   971.1  979.22  987.34  995.45
  286.03  285.78  285.53  285.23  284.91  284.59  284.47  284.28   284.1  283.61
  283.33  283.22  283.18   282.8  282.62  282.44  282.22  281.95  281.76  281.57
  281.48   281.2  281.01     281  280.87  280.68  280.48  280.31   280.1  280.02
  279.88  279.74  279.64  279.46  279.28  279.19  279.25  279.22  279.16  279.07
  279.03  279.05  278.92  278.88  278.88  278.72  278.62  278.56  278.57  278.58
  278.48  278.49  278.36  278.32  278.41  278.49  278.56  278.58  278.62  278.71
   278.8   278.8  278.75  278.87  278.95  278.93  279.17  279.12  279.29  279.28
  279.15  279.46  279.58  279.66  279.71  280.09  279.93  279.99  280.15  280.23
  280.48  280.59  280.66   280.9  281.08  281.11  281.34  281.46  281.55  281.79
   281.9  282.14  282.37  282.57  282.71  282.87  283.15  283.22  283.46  283.81
  283.88  284.03  284.29  284.43  284.73  284.94  285.18  285.37  285.46  285.89
  286.07  286.29  286.34  286.54     287  287.19  287.41
                                                                                
                                                                                
                                                                                
                                                                                
                                                                                
                                                                                
                                                                                
                                                                                
                                                                                
                                                                                
                                                                                
                                                        
BR Coef=-1 , 0 , 0 ,, 0 ,,,0.8,0,,0,
WSPro=,,,, 1 ,,,, 0 ,,,, 0 ,,,,-1 ,-1 ,-1 , 0 , 0 , 0 , 0 , 0
Multiple Barrel Culv=2,10,20,82,0.011,0.4,1,8,1,258.4,258.4, 2,Culvert #1  , 0 ,34.5
   500.5     490   521.5     511
Culvert Bottom n=0.011
BC Design=,, 0 ,, 0 ,,,,,,
BC Use User HTab Curves=0
BC User HTab FreeFlow(D)= 0

Type RM Length L Ch R = 1 ,12679.95,68.88,177.2,232.09
BEGIN DESCRIPTION:
Center of channel lowered 1.0 ft based on bridge survey info.
END DESCRIPTION:
XS GIS Cut Line= 6
1571391.78931209743773.6973268091571593.96175666743933.134132639
1571866.19551562744133.209545866 1571921.0924131744174.382218957
1572107.71817976744289.3441299051572231.13765253744361.750220597
#Sta/Elev= 30
       0  276.99   44.57  273.54    62.4  272.51   98.06  270.66  151.55   268.7
  213.96  266.88  335.66  264.36  370.41  263.86  405.16  264.42  448.59   264.1
  457.28  263.73   481.1  260.45  488.58   258.4  499.48  258.38  510.79   258.4
  519.99  260.45  535.47  262.61  561.53  263.61  639.07  264.57  656.57  264.24
  713.17  265.19     761  266.55   785.7  267.72  810.39  269.79  843.31  271.94
  883.14  276.87   915.6  282.13  956.18  286.82  996.76  290.05 1026.23  290.35
#Mann= 3 , 0 , 0
       0     .05       0   481.1     .04       0  519.99      .1       0
#XS Ineff= 2 , 0
       0  447.15  278.32  554.23       0  278.32
Permanent Ineff=
       F       F
Bank Sta=481.1,519.99
XS Rating Curve= 0 ,0
Exp/Cntr=0.5,0.3

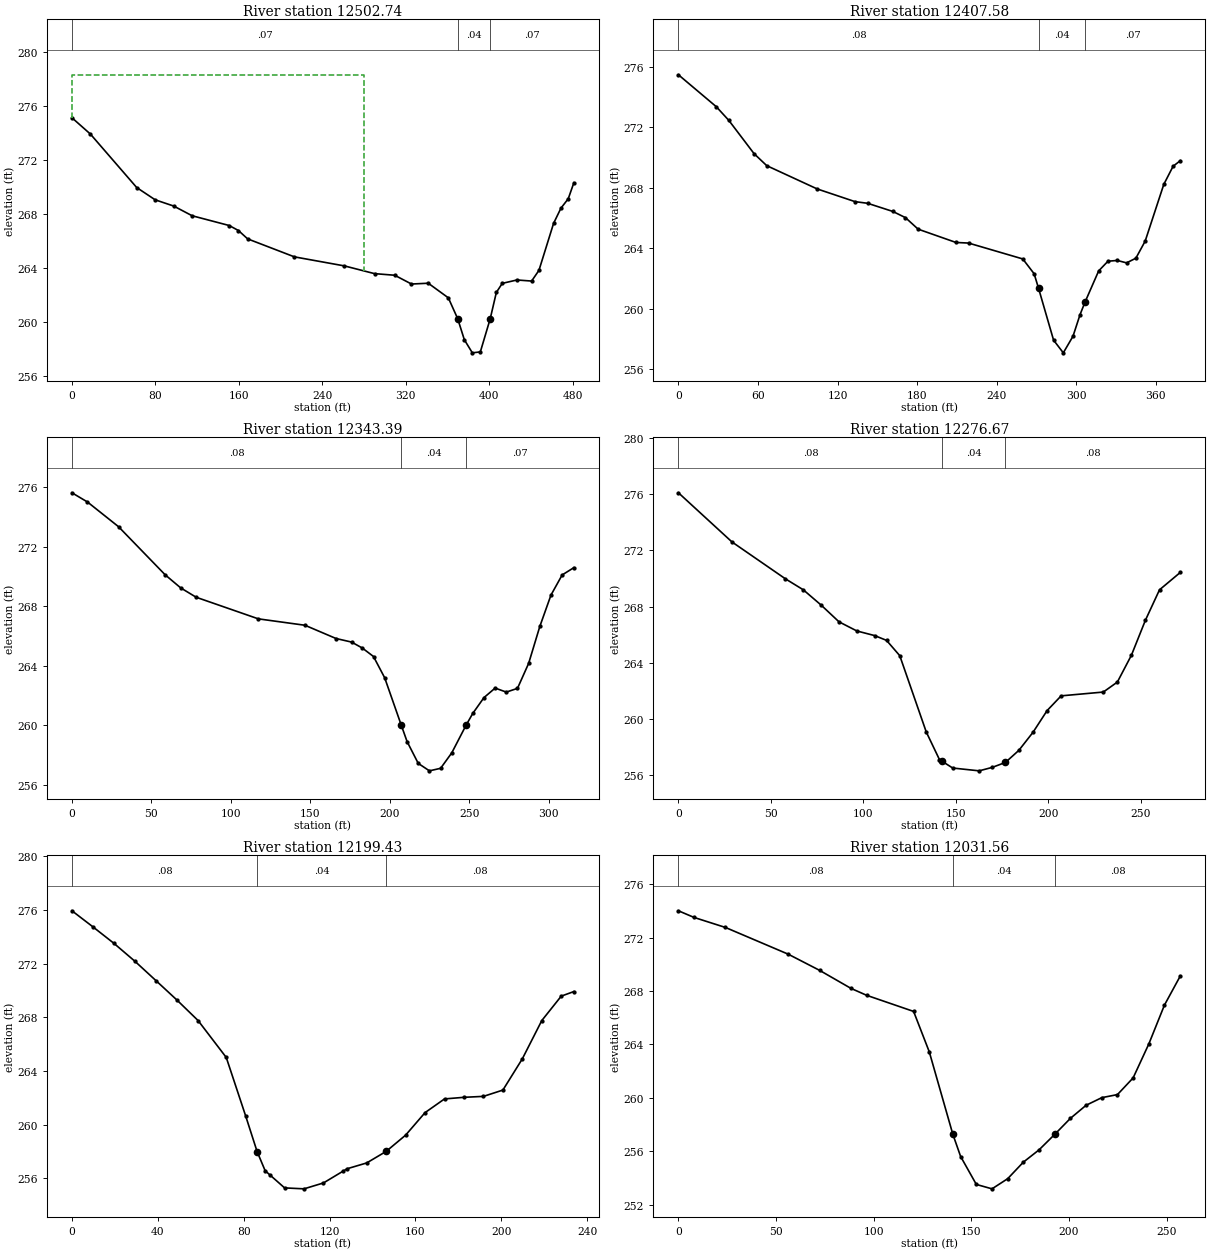
Type RM Length L Ch R = 1 ,12502.74,62.97,95.16,88.69
XS GIS Cut Line= 6
1571397.59426233743813.1156619341571543.24345553743926.217549339
  1571628.680133744017.3500053581571653.90429495 744062.10255073
1571632.74854627744109.2961440381571627.05276775744177.645486072
#Sta/Elev= 30
       0  275.14   17.73  273.93   62.04  269.98   79.76  269.07   97.49  268.61
  115.22  267.89  150.67  267.17  159.53   266.8  168.39  266.18  213.19  264.85
  261.17  264.18  289.95  263.61  309.32  263.49   325.4  262.84  341.47   262.9
   360.7  261.82   369.7  260.27  376.04  258.72  383.71  257.75  391.38  257.82
  400.87  260.28  406.72  262.22  412.41  262.89  426.46  263.14  440.51  263.06
  447.54  263.85  461.58  267.33  468.61  268.45  475.63  269.15     481  270.33
#Mann= 3 , 0 , 0
       0     .07       0   369.7     .04       0  400.87     .07       0
#XS Ineff= 2 , 0
       0   279.7  278.32               0
Permanent Ineff=
       F       F
Bank Sta=369.7,400.87
XS Rating Curve= 0 ,0
Exp/Cntr=0.3,0.1

Type RM Length L Ch R = 1 ,12407.58,58.89,64.19,56.82
XS GIS Cut Line= 5
  1571384.278598743829.7558016631571553.76215972743985.804690823
 1571565.1299596744021.9749631581571554.79559606 744055.04492642
1571549.62841432 744130.48578012
#Sta/Elev= 30
       0  275.46   28.55  273.35   38.06  272.44   57.09  270.24   66.61  269.45
  104.67  267.91  133.21  267.07  142.73  266.96  161.76  266.42  171.27  266.01
  180.79  265.25  209.34  264.37  218.85  264.33  259.73  263.28   268.3   262.3
  271.66  261.33  282.96  257.91   290.3  257.07  297.63  258.17  302.94   259.6
  306.56   260.4  316.98  262.49  323.99  263.13  331.01  263.18  338.03  263.02
  345.04  263.33  352.06  264.46  366.09  268.21  373.11  269.41  378.56  269.78
#Mann= 3 , 0 , 0
       0     .08       0  271.66     .04       0  306.56     .07       0
Bank Sta=271.66,306.56
XS Rating Curve= 0 ,0
Exp/Cntr=0.3,0.1

Type RM Length L Ch R = 1 ,12343.39,75.55,66.71,51.43
XS GIS Cut Line= 4
1571371.17420979743853.8279929611571502.01785837743981.400550365
1571495.47567594744043.5512834641571502.01785837744113.879744604
#Sta/Elev= 30
       0  275.62    9.78     275   29.33  273.34   58.66  270.11   68.44  269.23
   78.21   268.6  117.32  267.15  146.65  266.72   166.2  265.83  175.98  265.59
  182.74  265.19  189.78  264.62  196.82  263.19  207.28     260   210.9  258.91
  217.94  257.44  224.97  256.94  232.01  257.11  239.05  258.15  248.01     260
  252.27   260.8   259.3  261.86  266.33   262.5  273.36  262.23  280.39  262.48
  287.42  264.16  294.45  266.64  301.48  268.75  308.51   270.1  315.87  270.59
#Mann= 3 , 0 , 0
       0     .08       0  207.28     .04       0  248.01     .07       0
Bank Sta=207.28,248.01
XS Rating Curve= 0 ,0
Exp/Cntr=0.3,0.1

Type RM Length L Ch R = 1 ,12276.67,89.85,77.24,53.67
XS GIS Cut Line= 4
1571343.97458021743891.7619827991571421.48230667743973.403454602
1571438.01728827744050.9111810181571469.02037886744124.285162017
#Sta/Elev= 27
       0   276.1   28.96   272.6   57.91  269.97   67.56  269.19   77.22   268.1
   86.87  266.91   96.52  266.26  106.17  265.93  112.57  265.59  119.73   264.5
  134.05  259.07   141.2   257.1  142.77  256.97  148.36   256.5  162.68   256.3
  169.83  256.55   176.9   256.9  184.15  257.76  191.83  259.05  199.42  260.59
  207.02  261.64  229.82  261.91  237.42  262.62  245.02  264.53  252.62  267.03
  260.22  269.19  271.48  270.43
#Mann= 3 , 0 , 0
       0     .08       0  142.77     .04       0   176.9     .08       0
Bank Sta=142.77,176.9
XS Rating Curve= 0 ,0
Exp/Cntr=0.3,0.1

Type RM Length L Ch R = 1 ,12199.43,178.5,167.87,145.73
XS GIS Cut Line= 4
 1571290.8871246743977.4450978791571342.26478319 744027.70585084
1571378.00576311744071.2651701121571445.02010043744152.799280524
#Sta/Elev= 29
       0  275.94    9.79  274.74   19.58  273.51   29.38  272.17   39.17  270.73
   48.96  269.28   58.75  267.76   71.87  265.01   80.93  260.64   86.23     258
   89.98  256.57   92.03  256.28   99.04  255.29  108.09  255.22  117.15  255.66
   126.3  256.54  128.22  256.72  137.28  257.15  146.34  258.01   155.4  259.22
  164.46   260.9  173.52  261.92  182.59  262.04  191.65  262.11  200.71  262.58
  209.77  264.91  218.83  267.76  227.89  269.58  233.76  269.92
#Mann= 3 , 0 , 0
       0     .08       0   86.23     .04       0  146.34     .08       0
Bank Sta=86.23,146.34
XS Rating Curve= 0 ,0
Exp/Cntr=0.3,0.1

Type RM Length L Ch R = 1 ,12031.56,189.97,193.24,192.18
XS GIS Cut Line= 2
1571147.10446151744125.3285638541571371.17420979744251.265575632
#Sta/Elev= 25
       0  274.01    8.03  273.51   24.09  272.76   56.21  270.76   72.27  269.55
   88.33   268.2   96.36  267.68  120.45  266.47  128.48  263.44  140.51  257.28
  144.54   255.6  152.57  253.51   160.6  253.18  168.63  253.94  176.66  255.18
  184.69   256.1  192.72  257.26  200.75  258.46  208.78  259.44  216.81  260.01
  224.84  260.24  232.87  261.49   240.9  264.03  248.93  266.95  257.04  269.13
#Mann= 3 , 0 , 0
       0     .08       0  140.51     .04       0  192.72     .08       0
Bank Sta=140.51,192.72
XS Rating Curve= 0 ,0
Exp/Cntr=0.3,0.1

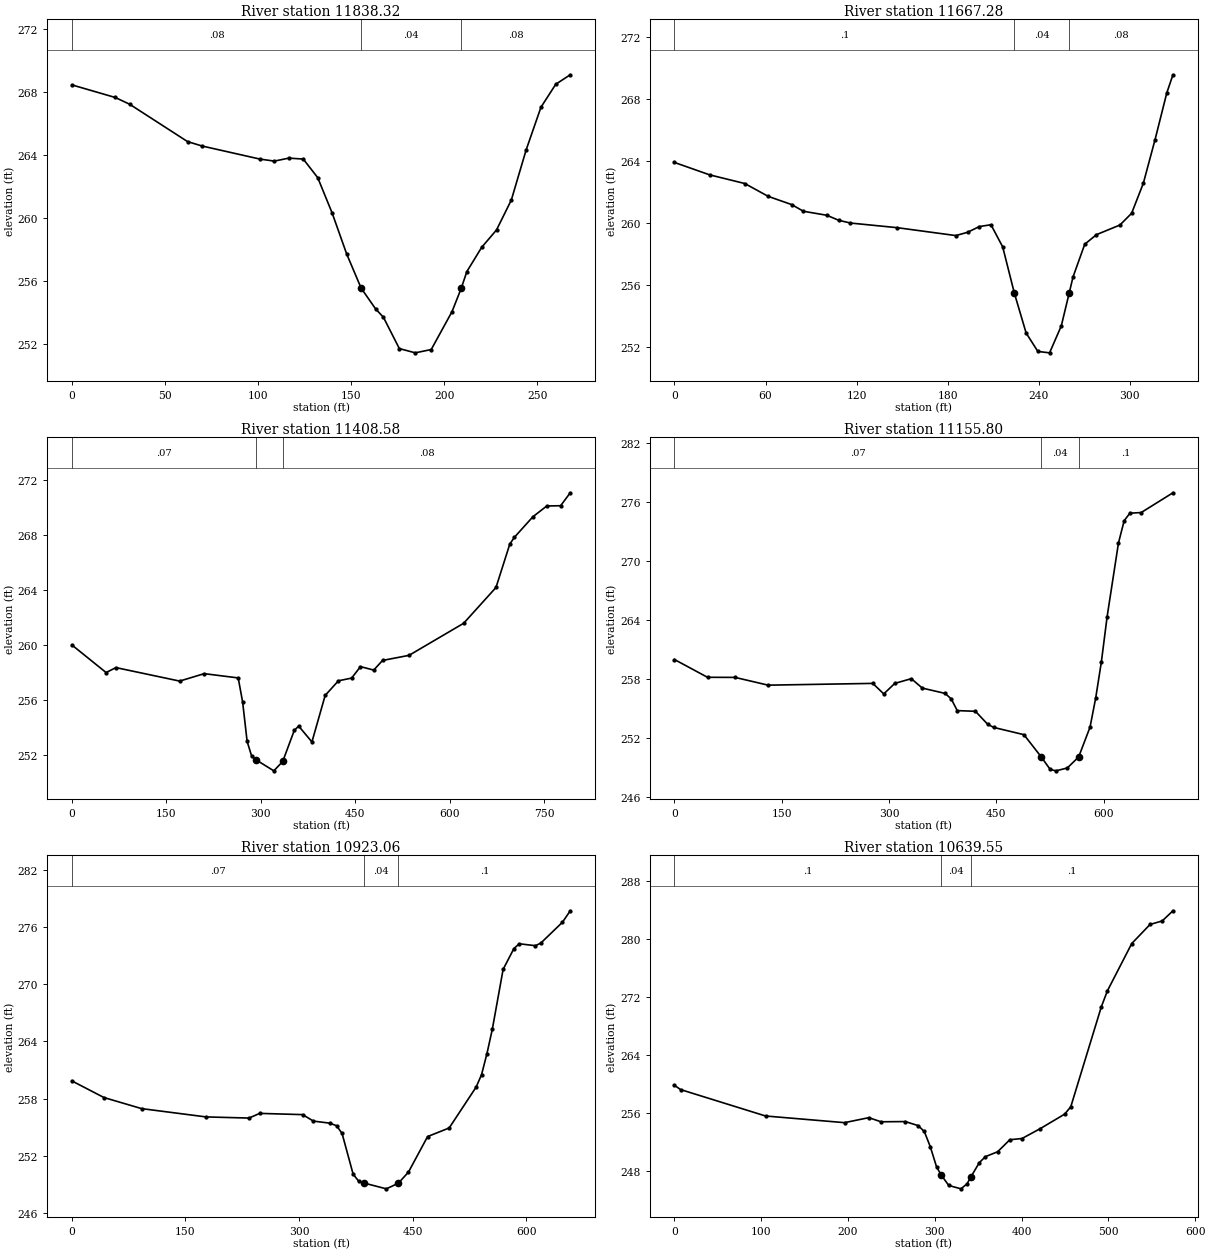
Type RM Length L Ch R = 1 ,11838.32,180.14,171.04,165.39
XS GIS Cut Line= 4
1571044.05098207744295.7632001491571194.83324109744368.362065569
1571224.98969287744389.5832723831571280.83497396744419.739724174
#Sta/Elev= 28
       0  268.48   23.31  267.68   31.08  267.25   62.15  264.88   69.92   264.6
     101  263.77  108.77  263.64  116.54  263.83  124.31  263.77  132.08  262.59
  139.84  260.34  147.61  257.75  155.38  255.58  163.15  254.26  167.35  253.73
  175.91  251.74  184.47  251.47  193.03  251.68  204.22  254.09  209.18  255.58
  212.18  256.63  220.14  258.17  228.09  259.27  236.05  261.17     244  264.35
  251.96  267.06  259.91  268.52  267.69  269.12
#Mann= 3 , 0 , 0
       0     .08       0  155.38     .04       0  209.18     .08       0
Bank Sta=155.38,209.18
XS Rating Curve= 0 ,0
Exp/Cntr=0.3,0.1

Type RM Length L Ch R = 1 ,11667.28,251.18,258.7,232.38
XS GIS Cut Line= 2
1570903.40816596 744422.997864441571201.07746658744562.019241109
#Sta/Elev= 30
       0  263.92   23.18  263.12   46.35  262.56   61.81  261.73   77.26   261.2
   84.98  260.77  100.44  260.51  108.16  260.19  115.89  260.01  146.79  259.71
  185.42   259.2  193.14  259.41  200.87  259.78   208.6   259.9  216.32  258.47
  224.05  255.47  231.77  252.91   239.5  251.72  247.23  251.63  254.95  253.37
   260.1  255.47  262.68  256.53   270.4  258.64  278.13  259.26  293.58  259.88
  301.31  260.64  309.03  262.58  316.76   265.4  324.48  268.41  328.53  269.58
#Mann= 3 , 0 , 0
       0      .1       0  224.05     .04       0   260.1     .08       0
Bank Sta=224.05,260.1
XS Rating Curve= 0 ,0
Exp/Cntr=0.3,0.1

Type RM Length L Ch R = 1 ,11408.58,25.5,252.79,289.7
XS GIS Cut Line= 5
1570849.70940389744522.4950414151570962.51687172744753.694505185
1571050.75241587744765.9804670211571289.77021897744778.266428858
1571486.34560843744839.696238071
#Sta/Elev= 30
       0  260.03   54.52  258.02    70.1  258.38  171.35   257.4   210.3  257.94
  264.32  257.63  271.39  255.86  278.45  253.02  285.52  251.97  292.59  251.68
  320.86  250.88     335  251.56  353.35  253.82  360.36  254.13  381.39  252.98
  402.41  256.36  423.44  257.42  444.47  257.62  458.49  258.45  479.51   258.2
  493.53   258.9  535.59  259.27  622.34   261.6  673.68   264.2  695.68  267.36
  703.01  267.85  732.35  269.34  754.35  270.12  776.35  270.14  791.62  271.08
#Mann= 3 , 0 , 0
       0     .07       0  292.59     .04       0     335     .08       0
Bank Sta=292.59,335
XS Rating Curve= 0 ,0
Exp/Cntr=0.3,0.1

Type RM Length L Ch R = 1 ,11155.80,160.17,232.73,236.5
XS GIS Cut Line= 4
1570839.65725331744528.0795695331570997.14094599744872.086501122
1571066.38909455744973.7249127181571159.09226118745145.728378505
#Sta/Elev= 30
       0  259.99   46.19  258.18   84.69  258.17  130.88  257.38  277.15  257.56
  292.55  256.49  307.95  257.56  331.04  258.04  346.44  257.08  378.34  256.54
  386.81  255.98  395.28  254.79  420.69  254.72  437.63  253.41   446.1  253.08
  488.45  252.34  512.41   250.1  525.18   248.8  533.14  248.66  549.04  248.95
  564.94  250.07  580.85  253.11   588.8  256.09  596.75  259.78   604.7  264.34
  620.61  271.86  628.56  274.12  636.51  274.88  652.41  274.95  696.72  276.96
#Mann= 3 , 0 , 0
       0     .07       0  512.41     .04       0  564.94      .1       0
Bank Sta=512.41,564.94
XS Rating Curve= 0 ,0
Exp/Cntr=0.3,0.1

Type RM Length L Ch R = 1 ,10923.06,209,283.52,272.24
XS GIS Cut Line= 4
 1570780.4612553744553.7683988211570835.18963081744898.892236054
1570867.57989384745007.2320813831570903.32087377745199.339848369
#Sta/Elev= 30
       0  259.87   42.52  258.12   92.14  256.96  177.19  256.09  233.89  255.97
  248.06  256.46  304.76  256.33  318.94  255.65   340.2  255.44  349.44  255.17
  356.74  254.36  371.35  250.09  378.66  249.35  386.04  249.15  415.19  248.55
  431.07  249.14  444.42  250.31  469.63  254.03  498.11  254.93  533.72  259.22
  540.84  260.52  547.96  262.72  555.08  265.29  569.32  271.56  583.56  273.74
  590.68  274.24  612.04  274.04  619.16  274.32  647.64   276.5  657.92   277.7
#Mann= 3 , 0 , 0
       0     .07       0  386.04     .04       0  431.07      .1       0
Bank Sta=386.04,431.07
XS Rating Curve= 0 ,0
Exp/Cntr=0.3,0.1

Type RM Length L Ch R = 1 ,10639.55,156.85,147.4,143.84
XS GIS Cut Line= 4
1570624.70224839744573.7206129131570623.26929963 744854.57857199
 1570616.1045558744917.628317922 1570636.1658386745146.900121242
#Sta/Elev= 30
       0  259.83       7  259.24     105  255.59     196  254.67     224  255.36
     238  254.79     266  254.82  280.86  254.26  287.91  253.45  294.95  251.31
     302  248.58  307.22  247.47  316.09     246  330.18  245.53  337.22  246.23
  341.23   247.1  351.34  249.15  358.37  249.98  372.42  250.65  386.48  252.31
  400.53  252.48  421.61  253.85  449.72  255.85  456.74  256.87  491.88  270.65
  498.91  272.87  527.01  279.41  548.09  282.04  562.15  282.53  574.46  283.93
#Mann= 3 , 0 , 0
       0      .1       0  307.22     .04       0  341.23      .1       0
Bank Sta=307.22,341.23
XS Rating Curve= 0 ,0
Exp/Cntr=0.3,0.1

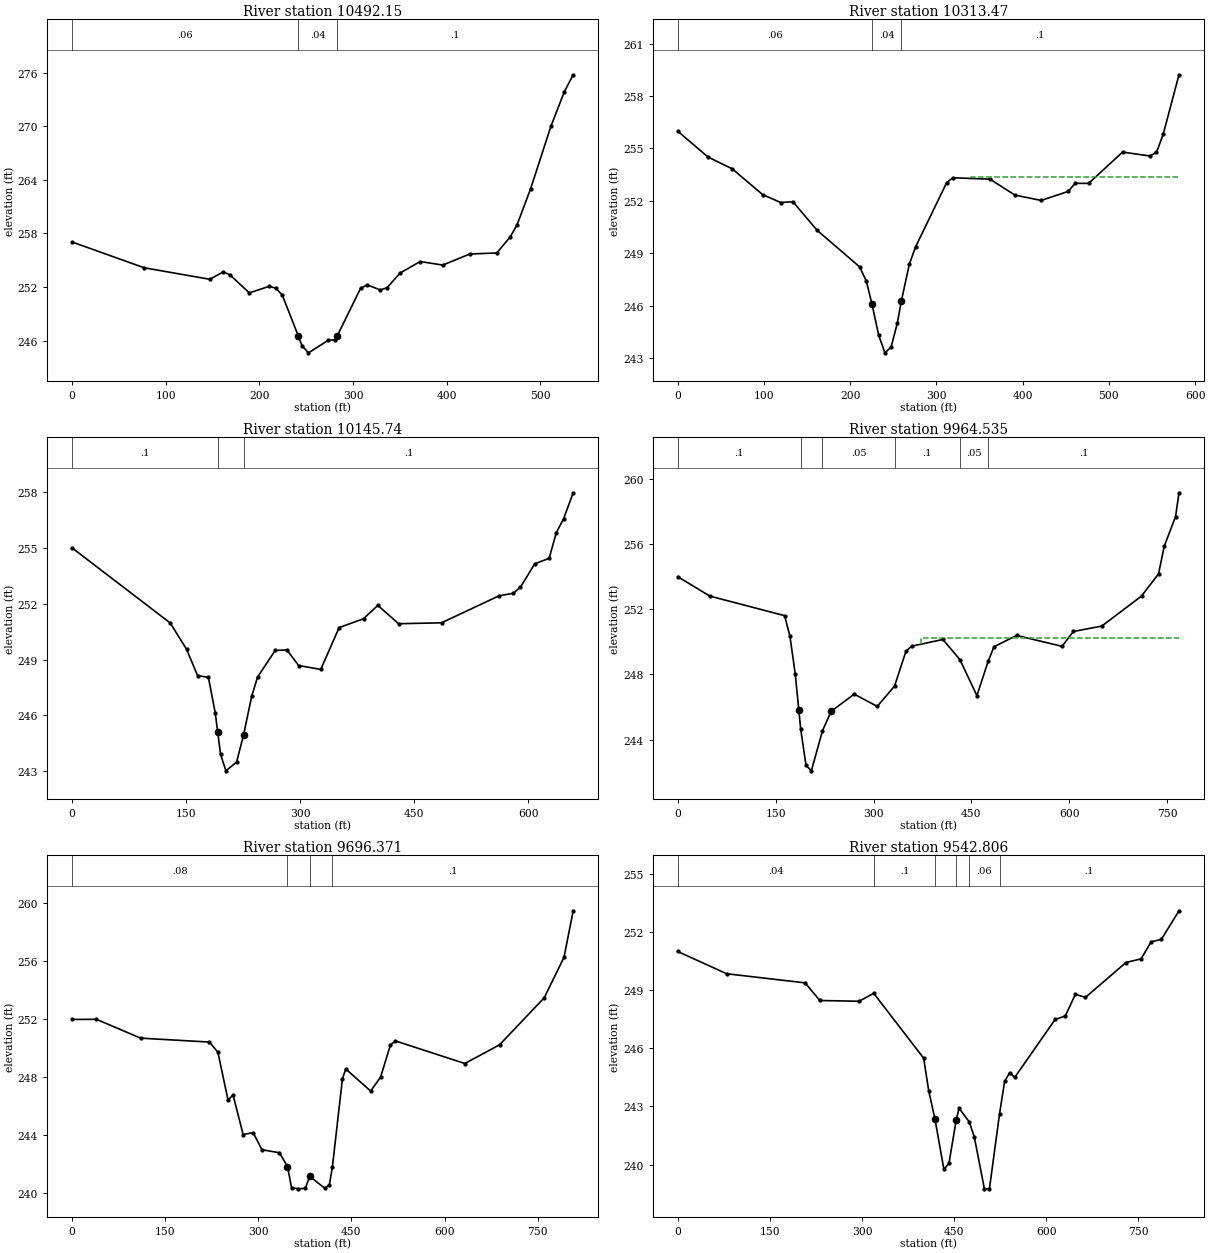
Type RM Length L Ch R = 1 ,10492.15,170.7,178.68,177.5
XS GIS Cut Line= 4
1570455.44171926744637.5363204931570474.42911486744937.983932808
1570487.83198231745031.8040050571570521.33915101745166.949585319
#Sta/Elev= 30
       0  257.05   77.15  254.16  147.29  252.87  161.32  253.69  168.34   253.4
  189.38  251.35  210.42  252.08  217.43  251.89  224.45  251.12  241.62  246.54
  245.49  245.45   252.5  244.64  273.54  246.04  280.56  246.09  283.24  246.55
  308.12  251.86  315.19  252.24  329.33  251.68   336.4  251.93  350.54  253.59
  371.76  254.86  395.82  254.46  424.67   255.7  453.52  255.82  467.94  257.63
  475.15  258.97  489.57  262.99  511.21  269.98  525.63  273.87  535.06  275.76
#Mann= 3 , 0 , 0
       0     .06       0  241.62     .04       0  283.24      .1       0
Bank Sta=241.62,283.24
XS Rating Curve= 0 ,0
Exp/Cntr=0.3,0.1

Type RM Length L Ch R = 1 ,10313.47,169.02,167.73,145.01
XS GIS Cut Line= 5
1570283.66044097744668.2952318041570303.72172375744886.103444949
1570293.69108233744927.6589593141570326.64890404745068.087938845
1570406.89403522 745224.27935487
#Sta/Elev= 30
       0  255.99   35.15  254.51   63.27  253.83   98.41  252.36   119.5   251.9
  133.56  251.95  161.68  250.31  210.89  248.22  218.73   247.4  225.26  246.09
  233.13  244.29  240.33  243.29  247.53  243.63  254.74     245  259.39  246.26
  268.67  248.38  275.86  249.36  311.81  253.03     319  253.32  362.14  253.24
   390.9  252.33  421.46  252.02  452.94  252.54  460.81     253  476.55     253
   515.9  254.79  547.38  254.57  555.25  254.77  563.12  255.83  581.32  259.22
#Mann= 3 , 0 , 0
       0     .06       0  225.26     .04       0  259.39      .1       0
#XS Ineff= 2 , 0
                          340.44          253.35
Permanent Ineff=
       F       F
Bank Sta=225.26,259.39
XS Rating Curve= 0 ,0
Exp/Cntr=0.3,0.1

Type RM Length L Ch R = 1 ,10145.74,190.34,181.21,150.15
XS GIS Cut Line= 6
1570101.38263711744667.6927722691570134.88980575744853.099105552
1570134.88980575744893.3077079211570169.51388001  744968.1403846
1570209.72248244745039.6223444041570385.07666509745239.548450753
#Sta/Elev= 30
       0  255.02  129.28  250.97  150.81  249.55  165.15  248.14   179.5  248.04
   188.5  246.12  191.62  245.12   195.5  243.89   202.5  243.01   216.5  243.48
   225.7  244.94  236.42  247.03  244.13  248.06  267.27  249.49   282.7  249.52
  298.12  248.68  327.22  248.47  351.32  250.72  383.45   251.2  402.27  251.92
  429.53  250.93  485.99  250.98  561.49  252.43  580.37  252.57   589.8   252.9
  608.68  254.16  627.56  254.45  636.99  255.84  646.43  256.57  659.17  257.98
#Mann= 3 , 0 , 0
       0      .1       0  191.62     .04       0   225.7      .1       0
#XS Ineff= 2 , 0
                          402.43          251.84
Permanent Ineff=
       F       F
Bank Sta=191.62,225.7
XS Rating Curve= 0 ,0
Exp/Cntr=0.3,0.1

Type RM Length L Ch R = 1 ,9964.535,262.51,268.16,141.33
XS GIS Cut Line= 4
1569849.47696339744712.716643691 1569966.9787626744906.164727747
1570065.85222778745035.1301171331570371.07031596745260.103074133
#Sta/Elev= 30
       0  253.99   49.14   252.8   163.8   251.6  171.99  250.33  180.18     248
  185.55  245.82  188.37  244.67  196.56  242.43  204.75  242.09   221.8  244.54
  235.16  245.74  270.44  246.79  305.72  246.04  332.18  247.28  349.82  249.43
  358.65  249.73  406.24  250.14  432.32  248.91  458.41   246.7   475.8  248.82
   484.5  249.69  519.28  250.39  588.85  249.72  606.24  250.63  649.73  250.96
   710.6   252.8  736.69  254.16  745.38  255.85  762.77  257.67  768.01  259.13
#Mann= 6 ,-1 , 0
       0      .1       0  188.37     .04       0   221.8     .05       0
  332.18      .1       0  432.32     .05       0   475.8      .1       0
#XS Ineff= 2 , 0
                          372.62           250.2
Permanent Ineff=
       F       F
Bank Sta=185.55,235.16
XS Rating Curve= 0 ,0
Exp/Cntr=0.3,0.1

Type RM Length L Ch R = 1 ,9696.371,122.94,153.57,185.93
BEGIN DESCRIPTION:
Channel modified since photographs show water between bank stations.
END DESCRIPTION:
XS GIS Cut Line= 6
1569718.11559013 744867.099082411569823.61982615745068.059532017
1569879.56888759745101.0457605871569974.14350647745098.179863036
1570028.59555975745101.0457605871570349.57608439745277.298459396
#Sta/Elev= 30
       0  251.98   39.53  251.99  110.68  250.69  221.37  250.42   235.1  249.72
  251.35  246.42  259.48  246.77  275.73  244.04  291.92  244.17  305.93  242.99
   334.2242.7811  347.16  241.83  353.66  240.38  364.67  240.29  375.86  240.33
  382.96  241.15  407.27  240.33  414.58  240.56  419.52  241.82  435.61  247.88
  441.07  248.56     481  247.04  496.97  247.99  512.94  250.22  520.93   250.5
  632.73  248.94  688.63  250.23   760.5  253.47  792.45  256.27  807.25  259.48
#Mann= 4 ,-1 , 0
       0     .08       0  347.16     .04       0  382.96     .06       0
  419.52      .1       0
#XS Ineff= 2 , 0
          221.31  250.41     521          250.49
Permanent Ineff=
       F       F
Bank Sta=347.16,382.96
XS Rating Curve= 0 ,0
Exp/Cntr=0.3,0.1

Type RM Length L Ch R = 1 ,9542.806,139.26,142.05,148.18
XS GIS Cut Line= 3
1569628.68819006744892.0181781651569785.43734072745178.386818826
1570201.90414307745436.123840272
#Sta/Elev= 30
       0     251    79.8  249.85  207.48  249.38  231.42  248.47  295.26  248.43
   319.2  248.84  400.55  245.49  408.78   243.8  418.97  242.34  433.48  239.75
  441.71  240.07   453.5   242.3  458.17  242.91  474.64  242.21  482.87  241.44
  499.34  238.76  507.57  238.75  524.03  242.61  532.26  244.29   540.5  244.74
  548.73   244.5  614.58  247.49  631.05  247.67  647.51  248.79  663.98  248.63
  729.83  250.43  754.53  250.62  770.99   251.5  787.46  251.62  816.23   253.1
#Mann= 6 ,-1 , 0
       0     .04       0   319.2      .1       0  418.97     .04       0
   453.5      .1       0  474.64     .06       0  524.03      .1       0
#XS Ineff= 2 , 0
          319.22  248.83
Permanent Ineff=
       F       F
Bank Sta=418.97,453.5
XS Rating Curve= 0 ,0
Exp/Cntr=0.3,0.1

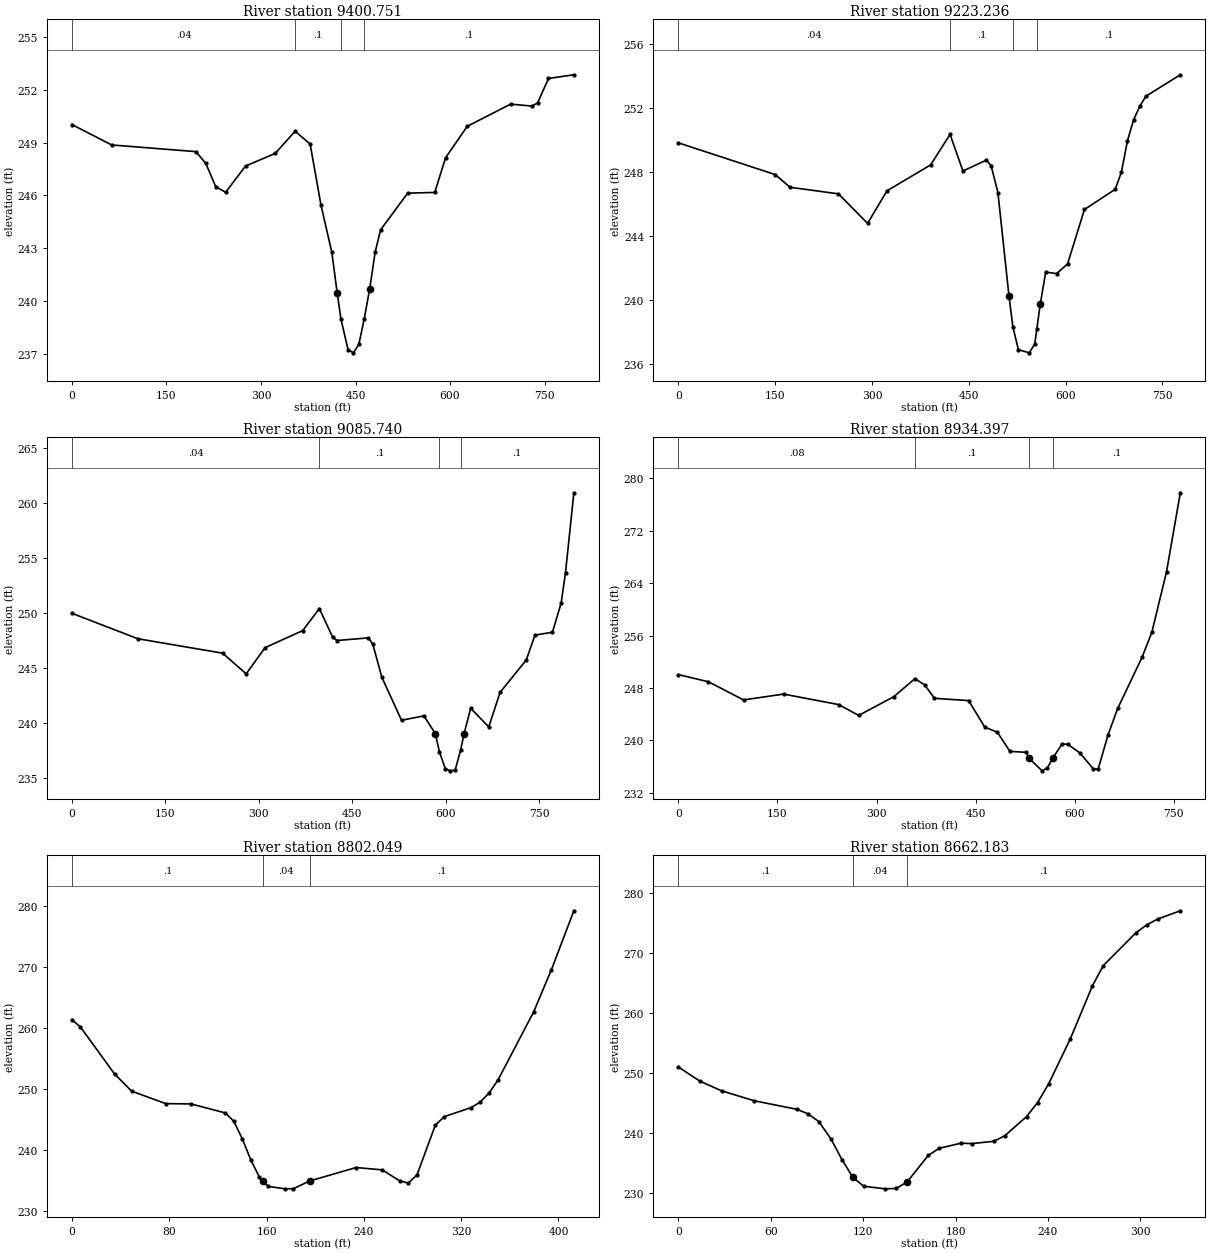
Type RM Length L Ch R = 1 ,9400.751,177.43,177.52,185.72
XS GIS Cut Line= 3
1569571.41446191744982.450380474 1569740.2051926745311.043223917
1570087.97976966745558.983458668
#Sta/Elev= 30
       0  250.03   62.96  248.87  196.74  248.49  212.48  247.82  228.22  246.49
  243.96  246.18  275.43  247.67  322.65  248.39  354.13  249.65  378.01  248.92
   395.2  245.45  412.39  242.77  420.99  240.44  426.92  238.97  438.18  237.23
  446.78  237.05  455.38  237.55  463.81  238.97  472.57   240.7  481.17  242.77
  489.77  244.04  532.75  246.13  575.73  246.17  592.93  248.14  627.31  249.93
  696.09  251.19  730.48  251.08  739.07  251.27  756.27  252.65  796.52  252.86
#Mann= 4 ,-1 , 0
       0     .04       0  354.13      .1       0  426.92     .04       0
  463.81      .1       0
#XS Ineff= 2 , 0
          355.27  247.77
Permanent Ineff=
       F       F
Bank Sta=420.99,472.57
XS Rating Curve= 0 ,0
Exp/Cntr=0.3,0.1

Type RM Length L Ch R = 1 ,9223.236,93.2,137.5,166.79
XS GIS Cut Line= 6
1569513.13593151745017.6184591651569668.26312344745414.690361634
1569687.01065131745480.8000651151569700.41351876745499.787460715
1569784.18144046745556.7496474391569891.40438014745672.907832131
#Sta/Elev= 30
       0  249.81   150.3  247.82  172.85  247.03     248  246.62  293.09  244.77
  323.16  246.81  390.79  248.43  420.85  250.34  440.85  248.05  477.23  248.73
  484.51  248.38  495.02   246.7  512.15  240.23  518.26  238.29  526.72  236.87
  543.65  236.67  552.12  237.23  555.31  238.16  560.58   239.7  569.05  241.72
  585.98  241.63  602.91  242.23  629.08  245.64  676.72   246.9  686.24  247.96
  695.77  249.94  705.29  251.26  714.82   252.1  724.35  252.73  777.64  254.07
#Mann= 4 ,-1 , 0
       0     .04       0  420.85      .1       0  518.26     .04       0
  555.31      .1       0
#XS Ineff= 2 , 0
       0  313.08   245.7               0
Permanent Ineff=
       F       F
Bank Sta=512.15,560.58
XS Rating Curve= 0 ,0
Exp/Cntr=0.3,0.1

Type RM Length L Ch R = 1 ,9085.740,72.43,151.34,208.03
XS GIS Cut Line= 6
1569503.08790906745038.7193063651569652.80344403745406.476929113
1569612.17797467 745588.023004831569635.63299271745631.582324103
1569650.15276581745684.0768883381569647.91895454745802.468884274
#Sta/Elev= 30
       0  249.99  105.81  247.68  241.85  246.37  279.64  244.49  309.87  246.87
  370.33  248.42  397.06  250.42  418.53   247.8  425.68  247.52  475.76  247.76
  482.91  247.18  497.22   244.2  528.88  240.28  564.89  240.68  583.12  239.07
  589.61  237.44  599.02   235.9  606.97  235.69  614.92  235.75   623.6  237.54
  629.36  239.07  639.86  241.37  668.91  239.68  687.06  242.81  729.07  245.75
  743.07  248.01  771.07  248.27  785.08  250.92  792.08  253.68  805.47  260.93
#Mann= 4 ,-1 , 0
       0     .04       0  397.06      .1       0  589.61     .04       0
   623.6      .1       0
#XS Ineff= 2 , 0
       0  299.58     245               0
Permanent Ineff=
       F       F
Bank Sta=583.12,629.36
XS Rating Curve= 0 ,0
Exp/Cntr=0.3,0.1

Type RM Length L Ch R = 1 ,8934.397,163.1,132.35,82.25
XS GIS Cut Line= 6
 1569480.9822596745066.8537693171569618.64016758745397.433708891
  1569587.606051745488.6184044781569488.20145062745564.567986786
1569463.62952694745595.8413441931569418.95330203 745727.63620761
#Sta/Elev= 30
       0  250.04    45.5  248.95   98.57  246.18  159.24  247.07  242.64  245.47
  272.98  243.82  326.05  246.67   358.1  249.42  372.88  248.47  387.67  246.43
  439.43  246.08  463.92  242.03  482.94  241.26  501.95  238.34  526.61  238.19
  530.98  237.27  550.72  235.37  558.75  235.84  566.79  237.28  581.06  239.49
  589.96  239.39  607.76  238.11  628.22  235.68  635.61  235.64  650.39  240.81
  665.18  244.89  702.13   252.7  716.91   256.5  739.09  265.71  759.99  277.76
#Mann= 4 ,-1 , 0
       0     .08       0   358.1      .1       0  530.98     .04       0
  566.79      .1       0
#XS Ineff= 2 , 0
          291.98  244.05
Permanent Ineff=
       F       F
Bank Sta=530.98,566.79
XS Rating Curve= 0 ,0
Exp/Cntr=0.3,0.1

Type RM Length L Ch R = 1 ,8802.049,135.28,139.87,137.05
XS GIS Cut Line= 4
1569410.66109875745300.1829442531569418.33442032745497.770976529
1569398.24771135745589.1655025041569361.08729964745704.664079279
#Sta/Elev= 30
       0  261.31    7.01  260.11   35.03  252.42   49.04  249.61   77.06  247.57
   98.07  247.51   126.1  246.04   133.1  244.67  140.11  241.76  147.11  238.33
  154.12  235.52     157  234.86  161.22  234.02  175.13  233.61  182.14  233.64
  195.34  234.89  233.57   237.1  255.07  236.72  269.41  234.92  276.57  234.54
  283.74  235.92  298.67     244  306.02  245.43  328.08  246.91  335.43  247.78
  342.79  249.27  350.14  251.39  379.55  262.57  394.26  269.53  412.64  279.15
#Mann= 3 , 0 , 0
       0      .1       0     157     .04       0  195.34      .1       0
Bank Sta=157,195.34
XS Rating Curve= 0 ,0
Exp/Cntr=0.3,0.1

Type RM Length L Ch R = 1 ,8662.183,160.54,161.1,163.3
XS GIS Cut Line= 4
1569289.58686477745363.2613778561569282.78874908 745462.14306055
1569273.51859134745524.5621227471569245.09010758745685.862867638
#Sta/Elev= 30
       0  250.95   14.03  248.58   28.07  246.98   49.12  245.33   77.18  243.89
    84.2  243.14   91.21  241.85   99.12  238.95  106.19  235.53  113.27  232.57
  120.35  231.07   134.5  230.64  141.58  230.71  148.65  231.81  162.22   236.2
  169.33   237.4  183.54  238.25  190.65  238.18  204.87  238.57  211.97  239.49
  226.19   242.7   233.3  245.03  240.41  248.11  254.62  255.68  268.84  264.45
  275.94  267.85  297.27  273.36  304.38  274.68  311.48  275.64  326.01     277
#Mann= 3 , 0 , 0
       0      .1       0  113.27     .04       0  148.65      .1       0
Bank Sta=113.27,148.65
XS Rating Curve= 0 ,0
Exp/Cntr=0.3,0.1