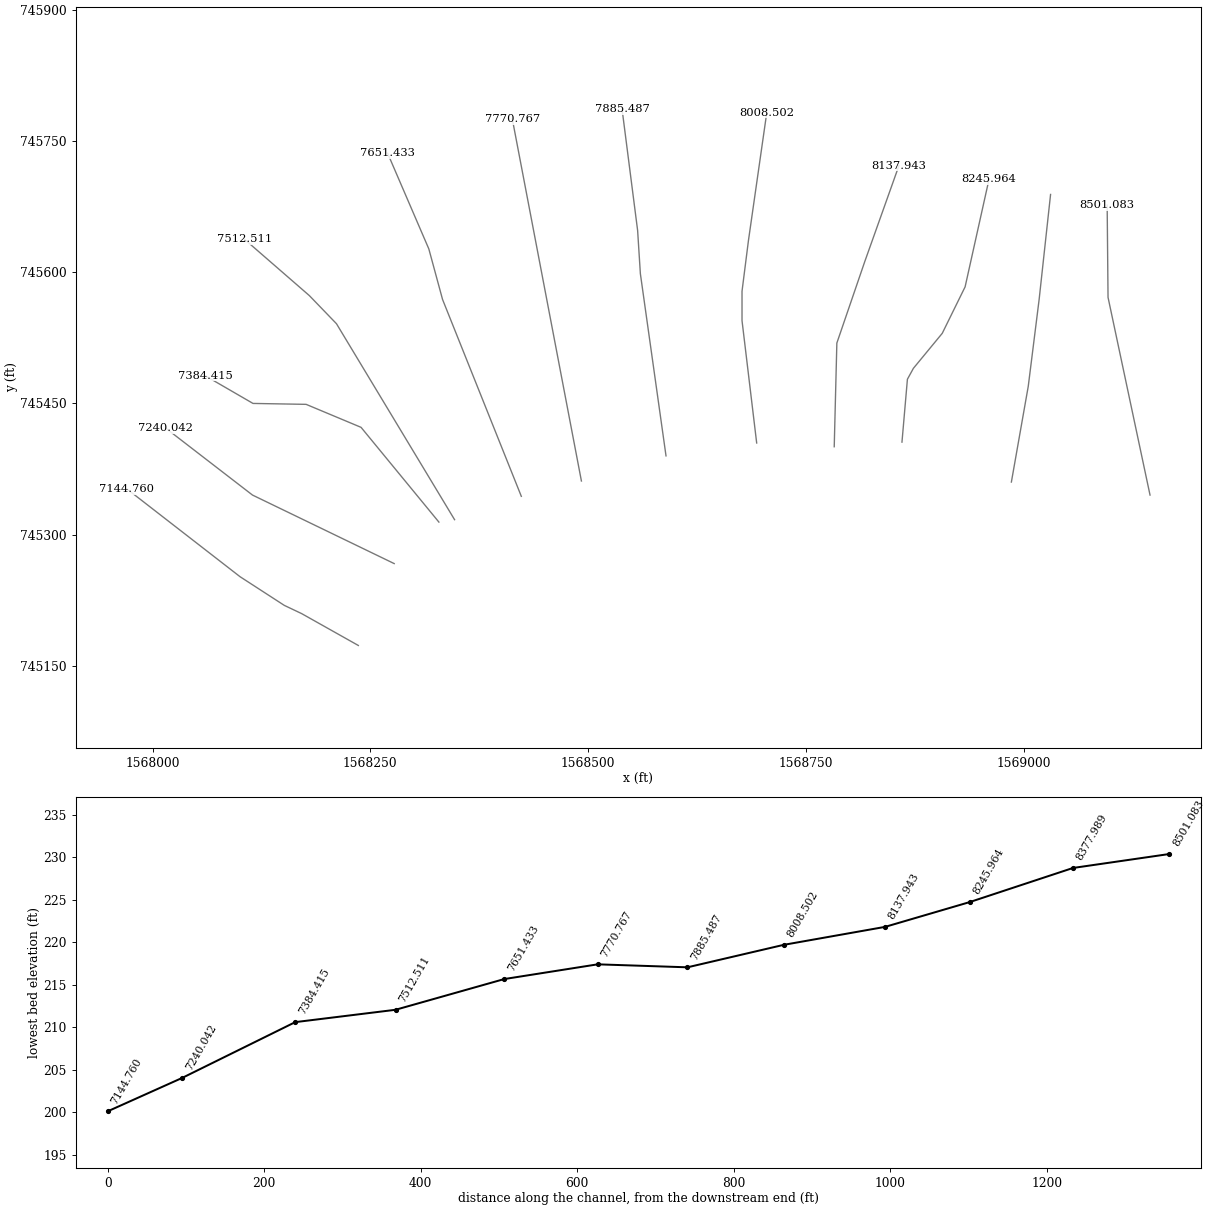
HEC-RAS study StoneRun.prj: StoneRun

--- StoneRun.g01 (geometry) --- (continued)

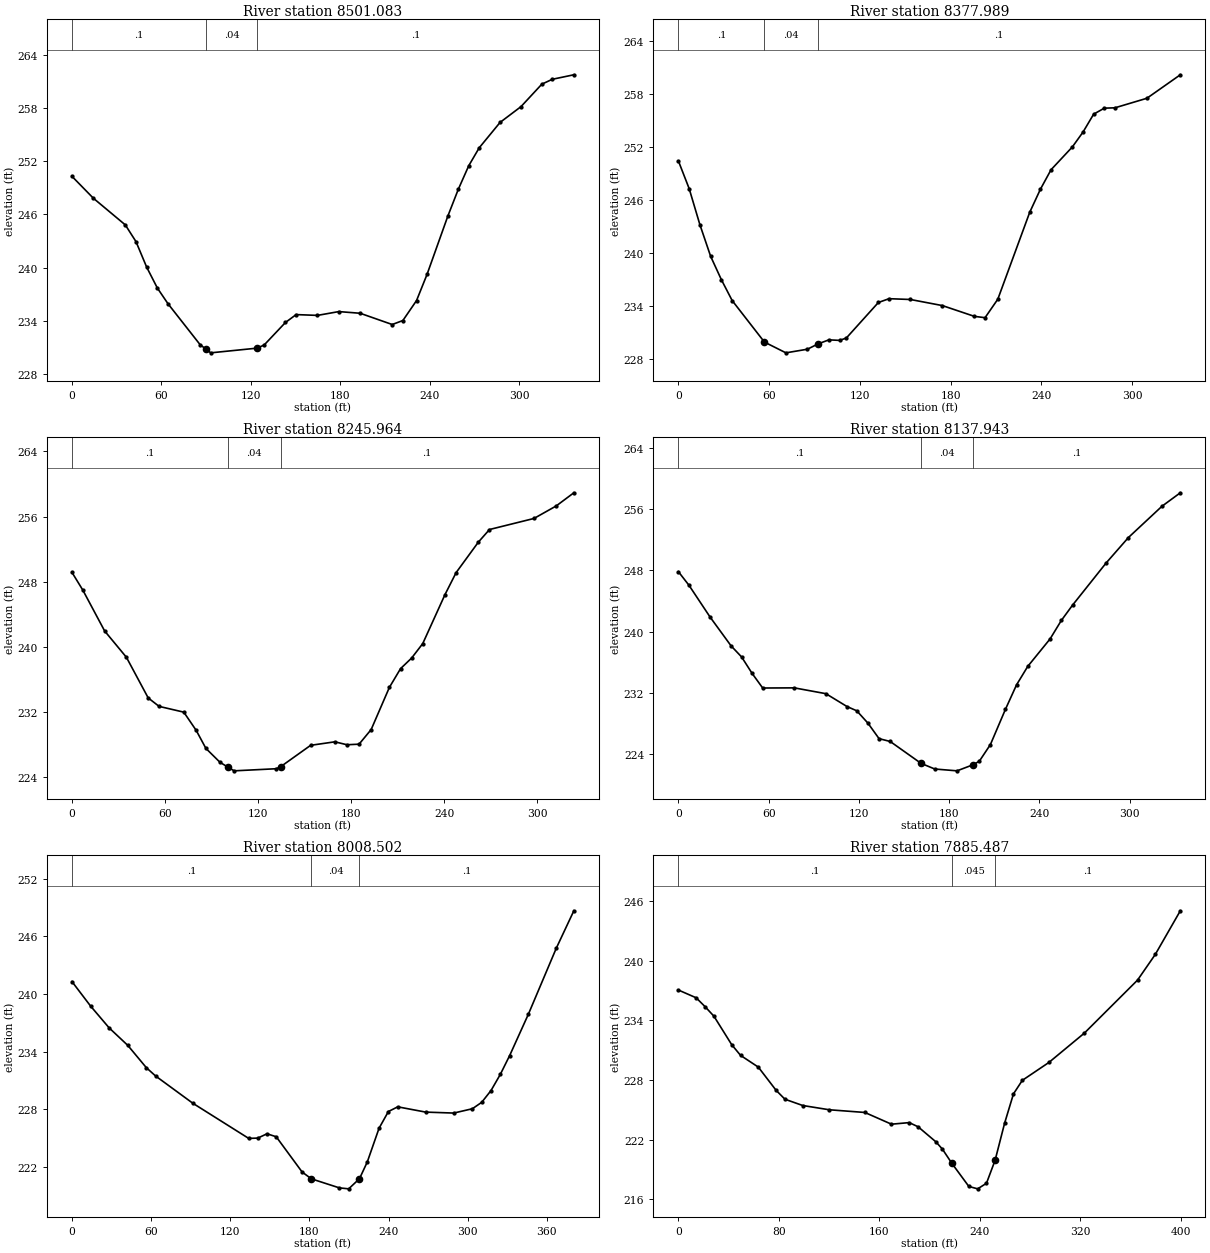
Type RM Length L Ch R = 1 ,8501.083,139.55,123.1,109.05
XS GIS Cut Line= 3
1569145.15517786745345.1119880831569096.94707626745571.087464407
1569095.94274081745676.542686671
#Sta/Elev= 30
       0   250.3   14.32  247.83   35.79  244.81   42.95  242.92    50.1  240.04
   57.26  237.68   64.42   235.9   85.89  231.29   90.05  230.75   93.05  230.36
  124.11  230.89  128.84  231.24  143.15  233.79  150.31  234.68  164.62  234.59
  178.94  235.02  193.25  234.83  214.73  233.56  221.88  234.01  231.06  236.27
  238.06  239.21  252.06  245.82  259.06  248.84  266.06   251.5  273.06  253.52
  287.06  256.39  301.06  258.17  315.06  260.71  322.06  261.26  336.52  261.77
#Mann= 3 , 0 , 0
       0      .1       0   90.05     .04       0  124.11      .1       0
Bank Sta=90.05,124.11
XS Rating Curve= 0 ,0
Exp/Cntr=0.3,0.1

Type RM Length L Ch R = 1 ,8377.989,147.59,132.02,113.09
XS GIS Cut Line= 4
1568985.97240661745359.9958928081569005.34515366745469.358174622
1569017.84370017745568.7216192041569030.96717399745688.707665533
#Sta/Elev= 30
       0  250.44    7.11  247.31   14.22  243.22   21.33  239.64   28.44  236.99
   35.54  234.64   56.87  229.94   71.09  228.72   85.31  229.13   92.42  229.74
   99.53  230.19  106.63  230.13  111.06   230.4  132.23  234.42  139.29  234.85
   153.4  234.76  174.56  234.07  195.73  232.85  202.78   232.7  211.21  234.79
  232.34  244.64  239.38  247.24  246.42  249.45   260.5  252.03  267.55  253.71
  274.59  255.74  281.63  256.42  288.67  256.46   309.8  257.54  331.91   260.2
#Mann= 3 , 0 , 0
       0      .1       0   56.87     .04       0   92.42      .1       0
#XS Ineff= 2 , 0
                          142.14          234.78
Permanent Ineff=
       F       F
Bank Sta=56.87,92.42
XS Rating Curve= 0 ,0
Exp/Cntr=0.3,0.1

Type RM Length L Ch R = 1 ,8245.964,95.47,108.02,115.68
XS GIS Cut Line= 6
1568860.36201435745405.6155875181568866.61128764745477.482229844
1568873.48548824745489.9807763251568906.60663641745529.976125106
1568932.85358404745583.0949476661568960.35038632  745706.2056306
#Sta/Elev= 30
       0  249.13    7.03  246.94   21.08  241.92   35.13  238.68   49.18  233.68
   56.21  232.64   72.14  231.93   80.13  229.69    86.4  227.47   95.49  225.76
  100.48  225.18  104.58  224.71  131.85  224.97  134.54  225.21  153.95  227.85
  169.56  228.28  177.37  227.92  185.18  227.99  192.99  229.79  204.75  234.98
  211.93  237.28   219.1  238.59  226.27  240.37  240.62   246.4  247.79   249.1
  262.13  252.85  269.31   254.4     298  255.76  312.34   257.3  323.72  258.92
#Mann= 3 , 0 , 0
       0      .1       0  100.48     .04       0  134.54      .1       0
Bank Sta=100.48,134.54
XS Rating Curve= 0 ,0
Exp/Cntr=0.3,0.1

Type RM Length L Ch R = 1 ,8137.943,117.33,129.44,134.31
XS GIS Cut Line= 4
1568782.59008028 745400.350437851568785.60308665745518.862020999
1568817.74182107745612.2652178561568856.91090365745721.737781942
#Sta/Elev= 30
       0  247.84       7  246.07   21.01  241.92   35.01  238.14   42.01  236.69
   49.02  234.53   56.02  232.63   77.02  232.65   98.03  231.89  112.04  230.21
  118.55  229.65  125.95  228.04  133.36  226.01  140.76  225.64  161.26  222.78
  170.37  222.04  185.18   221.8  195.62  222.58  199.98  223.05  207.38  225.24
  217.33  229.83  224.76  233.05   232.2  235.46  247.07  239.06   254.5  241.46
  261.94  243.46  284.24  248.97  299.11  252.31  321.41   256.4   333.6  258.16
#Mann= 3 , 0 , 0
       0      .1       0  161.26     .04       0  195.62      .1       0
Bank Sta=161.26,195.62
XS Rating Curve= 0 ,0
Exp/Cntr=0.3,0.1

Type RM Length L Ch R = 1 ,8008.502,109.75,123.02,127.92
XS GIS Cut Line= 5
1568693.55286601745404.6380829361568676.73049805745544.474016786
1568676.73049805745578.1187527181568684.09028405745635.945642665
1568705.11824405745782.089964479
#Sta/Elev= 30
       0   241.3    14.1  238.75    28.2  236.47    42.3  234.65    56.4  232.32
   63.45  231.45   91.66  228.61  133.96  224.95  140.84  224.98  147.84  225.43
  154.84  225.12  174.49  221.44  181.55  220.73  202.71  219.79  209.77  219.69
  217.95  220.75  223.88   222.5  232.78  226.01  239.85  227.75  246.93  228.24
  268.14  227.69  289.36  227.59   303.5  228.04  310.58  228.71  317.65  229.94
  324.72  231.63  331.79  233.59  345.94  237.89  367.15  244.79  380.43  248.68
#Mann= 3 , 0 , 0
       0      .1       0  181.55     .04       0  217.95      .1       0
#XS Ineff= 2 , 0
                          247.68          228.12
Permanent Ineff=
       F       F
Bank Sta=181.55,217.95
XS Rating Curve= 0 ,0
Exp/Cntr=0.3,0.1

Type RM Length L Ch R = 1 ,7885.487,108.95,114.72,117.93
XS GIS Cut Line= 4
1568589.46446416745389.9185109591568560.02532017745598.095314711
1568556.87112619745647.5110206461568538.99736024745786.295556501
#Sta/Elev= 30
       0  237.04   14.14  236.26   21.21  235.37   28.28  234.41   42.42  231.55
   49.49  230.47   63.63  229.29   77.77  226.96   84.84  226.06   98.98  225.43
  120.18     225  148.46  224.73  169.67  223.55  183.81  223.71  190.88  223.29
  205.02  221.78  210.25  221.04  217.79  219.61  231.29  217.29  238.31  217.05
  245.32  217.61  252.21  219.93  259.76  223.65  266.82   226.6  273.88  227.96
  295.05  229.76  323.28  232.71  365.63  238.04  379.75  240.62  399.69  245.01
#Mann= 3 , 0 , 0
       0      .1       0  217.79    .045       0  252.21      .1       0
Bank Sta=217.79,252.21
XS Rating Curve= 0 ,0
Exp/Cntr=0.3,0.1

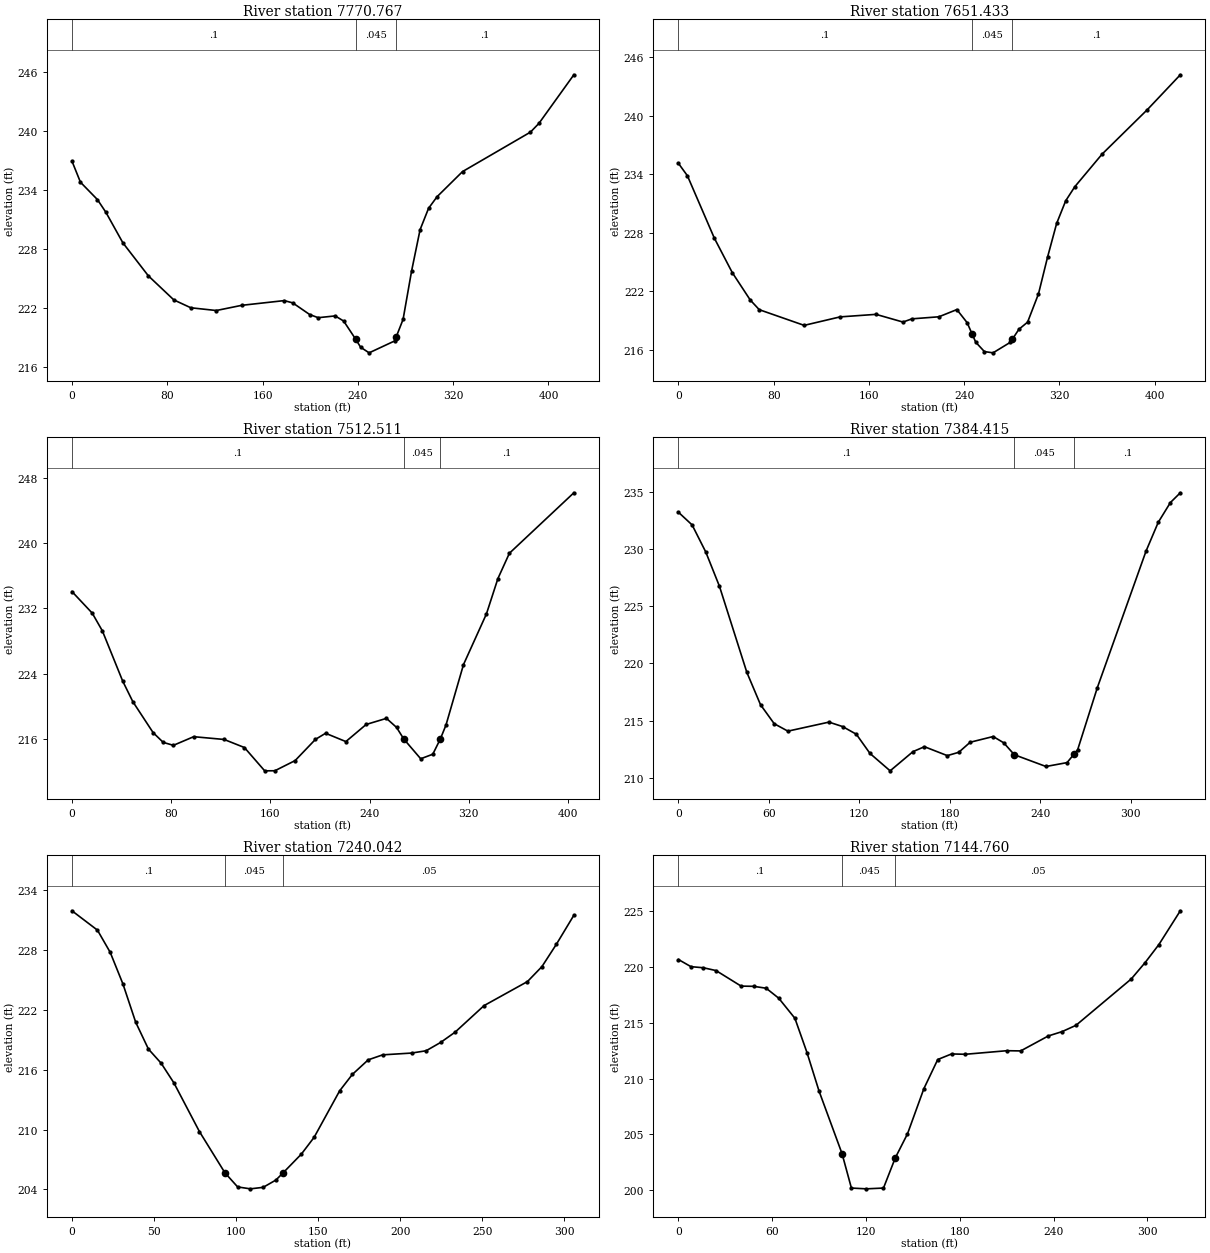
Type RM Length L Ch R = 1 ,7770.767,105.09,119.33,121.62
XS GIS Cut Line= 2
 1568492.3371352745361.181355298 1568412.9946346745774.967560813
#Sta/Elev= 30
       0  236.93    7.13  234.78   21.38  233.01   28.51  231.71   42.77   228.6
   64.15  225.24   85.53  222.79   99.79  221.99  121.17  221.71  142.55  222.24
  178.19  222.72  185.32  222.49  199.57   221.3   206.7  220.98  220.95  221.16
  228.08  220.64  238.05  218.81  242.34  217.97  249.46   217.4  270.85  218.61
  272.22  219.03  277.97  220.81   285.1  225.73  292.23  229.94  299.36  232.12
  306.48   233.3  327.87  235.86  384.89  239.88  392.01  240.77  421.32  245.72
#Mann= 3 , 0 , 0
       0      .1       0  238.05    .045       0  272.22      .1       0
Bank Sta=238.05,272.22
XS Rating Curve= 0 ,0
Exp/Cntr=0.3,0.1

Type RM Length L Ch R = 1 ,7651.433,109.64,138.92,148.39
XS GIS Cut Line= 4
1568423.34358035745343.6569990071568332.92335247745568.656170756
1568317.15238248745626.4830606731568269.83947255745735.828452542
#Sta/Elev= 30
       0  235.12    7.54  233.85   30.18  227.44   45.26   223.9   60.35  221.09
    67.9   220.1  105.62  218.49  135.79  219.36  165.97  219.62   188.6  218.83
  196.15  219.16  218.78  219.37  233.87  220.11  242.49  218.77  246.53  217.65
  249.74  216.76     257   215.8  264.26  215.67  278.77  216.75  280.55  217.08
  286.02  218.09  293.28  218.82  302.43  221.72  310.05  225.49  317.68  228.95
  325.31  231.28  332.94  232.72  355.82  236.06  393.95  240.64  421.57  244.21
#Mann= 3 , 0 , 0
       0      .1       0  246.53    .045       0  280.55      .1       0
Bank Sta=246.53,280.55
XS Rating Curve= 0 ,0
Exp/Cntr=0.3,0.1

Type RM Length L Ch R = 1 ,7512.511,40.14,128.1,141.53
XS GIS Cut Line= 4
1568346.70849489745316.9905955051568211.12320909745540.957400903
1568179.98881015745573.0961353031568105.66798684745637.373604119
#Sta/Elev= 30
       0  234.06   16.37  231.41   24.55  229.23   40.91  223.08    49.1  220.55
   65.46  216.75   73.64  215.55   81.83  215.19   98.19  216.25  122.74  215.91
  139.11  214.92  155.47  212.06  163.66  212.07  180.02  213.32  196.39  215.92
  204.57  216.67  220.93  215.65   237.3  217.75  253.67   218.5  261.81  217.39
  267.67  215.96   281.3  213.54  291.05   214.1  297.16  215.98  301.67  217.67
  315.81   225.1  334.32  231.32  343.58  235.66  352.83  238.76  404.82  246.18
#Mann= 3 , 0 , 0
       0      .1       0  267.67    .045       0  297.16      .1       0
Bank Sta=267.67,297.16
XS Rating Curve= 0 ,0
Exp/Cntr=0.3,0.1

Type RM Length L Ch R = 1 ,7384.415,125.28,144.37,121.81
XS GIS Cut Line= 5
 1568328.7177605745314.217855051 1568239.3489306745422.511848912
1568176.26505068  745448.79679891568115.28396672745449.848196879
 1568060.6112708745481.390136838
#Sta/Elev= 30
       0  233.22    9.08  232.11   18.15  229.74   27.23  226.74   45.38  219.22
   54.45  216.39   63.53  214.73   72.61  214.08   99.83  214.87  108.91  214.48
  117.99  213.81  127.06  212.13  140.41  210.61  155.57  212.29  163.16  212.72
  178.32  211.94  185.91  212.23  193.49  213.11  208.75  213.61  215.75  213.06
  222.75  212.02  243.75  210.99  257.76  211.33  262.66  212.12  264.76  212.45
  277.82  217.88  310.15  229.83  318.23  232.34  326.31  234.07  332.86  234.92
#Mann= 3 , 0 , 0
       0      .1       0  222.75    .045       0  262.66      .1       0
Bank Sta=222.75,262.66
XS Rating Curve= 0 ,0
Exp/Cntr=0.3,0.1

Type RM Length L Ch R = 1 ,7240.042,98,95.28,101.82
XS GIS Cut Line= 3
 1568277.4093488745266.7738229781568114.70700587745345.111988083
1568015.27779628 745421.44148232
#Sta/Elev= 30
       0  231.91   15.54  229.97   23.31  227.75   31.08  224.58   38.85  220.75
   46.61  218.06   54.38  216.64   62.15  214.67   77.69   209.8   93.23  205.67
     101  204.25  108.77  204.06  116.54  204.21  124.31  204.94  128.69  205.66
  139.84  207.54  147.61  209.22  163.15  213.87  170.92  215.52  180.58  216.98
   189.4  217.48  207.05  217.66  215.88  217.89   224.7  218.72  233.53  219.75
  251.18  222.41  277.65  224.82  286.48  226.32   295.3  228.56  305.93  231.46
#Mann= 3 , 0 , 0
       0      .1       0   93.23    .045       0  128.69     .05       0
Bank Sta=93.23,128.69
XS Rating Curve= 0 ,0
Exp/Cntr=0.5,0.3

Type RM Length L Ch R = 1 ,7144.760,81.16,80.4,83.18
BEGIN DESCRIPTION:
Center of channel lowered 1.0 ft based on bridge survey info.
END DESCRIPTION:
XS GIS Cut Line= 5
1568236.22112668745173.1896691921568171.18031013745209.588658258
1568151.23492251745219.0073135351568100.41149434745251.796622053
1567970.56745373 745352.07795696
#Sta/Elev= 30
       0  220.65    8.02  220.01   16.04  219.91   24.06  219.66   40.11  218.27
   48.13  218.25   56.15  218.08   64.17  217.19   74.53  215.39   82.27  212.32
   90.02  208.86  104.69  203.28  110.68   200.2  120.27  200.13  131.21   200.2
  138.76   202.9  146.57  205.05  157.07   209.1  165.92   211.7  174.76   212.2
  183.61  212.17  210.14  212.49  218.99  212.47  236.68  213.81  245.52   214.2
  254.36  214.76  289.74  218.91  298.59  220.37  307.43  221.99  321.13  225.01
#Mann= 3 , 0 , 0
       0      .1       0  104.69    .045       0  138.76     .05       0
Bank Sta=104.69,138.76
XS Rating Curve= 0 ,0
Exp/Cntr=0.5,0.3

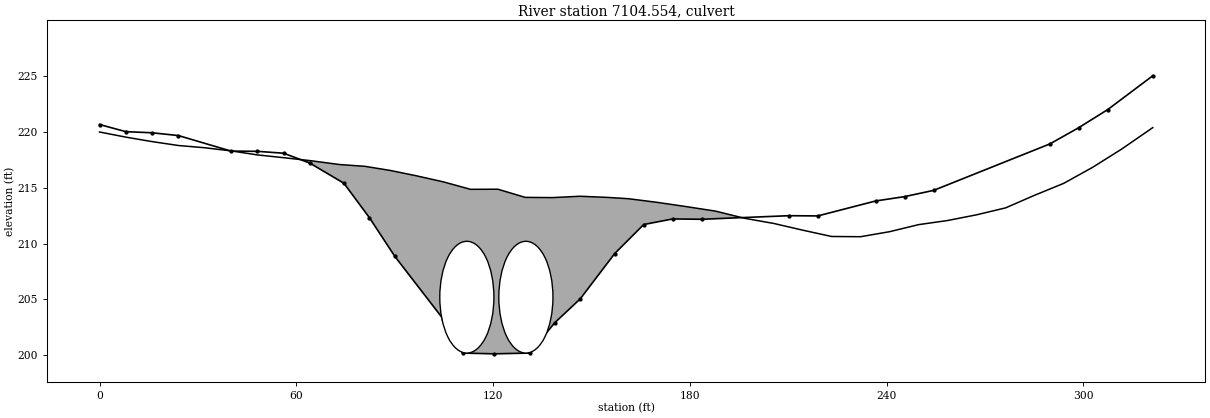
Type RM Length L Ch R = 2 ,7104.554,,,
BEGIN DESCRIPTION:
Slicers Mill Road, MDE Bridge #: CE042407FS-10
Top of road obtained from DEM.
Opening from MDE2 bridge/culvert surveys.
END DESCRIPTION:
Bridge Culvert--1,0,-1,-1, 0
Deck Dist Width WeirC Skew NumUp NumDn MinLoCord MaxHiCord MaxSubmerge Is_Ogee
24,32,2.6,0, 39, 41, , , 0.95, 0, 2,2,,
       0    8.02   16.04   24.06   32.09   40.11   48.13   56.15   64.17   73.15
   80.89   88.63   96.47   104.8  113.13  121.46  129.79  138.12  146.45  154.78
  161.28  170.13  178.97  187.82  196.66  205.51  214.35   223.2  232.04  240.89
  249.73  258.58  267.42  276.26  285.11  293.95   302.8  311.64  321.13
  219.98  219.52  219.12  218.77  218.57  218.29  217.93  217.68  217.42  217.07
  216.91  216.54  216.07  215.52  214.85  214.86  214.13  214.11  214.23  214.13
  214.01  213.68   213.3   212.9  212.26   211.8   211.2  210.63  210.61  211.06
  211.69  212.06  212.57  213.19  214.32  215.38  216.82  218.45  220.37
                                                                                
                                                                                
                                                                                
                                                                        
       0    8.02   16.04   24.06   32.09   40.11   48.13   56.15   64.17   73.15
   80.89   88.63   96.47   104.8  113.13  121.46  129.79  138.12  146.45  154.78
  161.28  170.13  178.97  187.82  196.66  205.51  214.35   223.2  232.04  240.89
  249.73  258.58  267.42  276.26  285.11  293.95   302.8  311.64  320.49  327.04
  332.94
  219.98  219.52  219.12  218.77  218.57  218.29  217.93  217.68  217.42  217.07
  216.91  216.54  216.07  215.52  214.85  214.86  214.13  214.11  214.23  214.13
  214.01  213.68   213.3   212.9  212.26   211.8   211.2  210.63  210.61  211.06
  211.69  212.06  212.57  213.19  214.32  215.38  216.82  218.45  220.37   221.8
     223
                                                                                
                                                                                
                                                                                
                                                                                
        
BR Coef=-1 , 0 , 0 ,, 0 ,,,0.8,0,,0,
WSPro=,,,, 1 ,,,, 0 ,,,, 0 ,,,,-1 ,-1 ,-1 , 0 , 0 , 0 , 0 , 0
Multiple Barrel Culv=3,10,16.5,44,0.03,0.7,1,34,2,200.2,200.2, 2,Culvert #1  , 0 ,18
     112     126     130     144
Culvert Bottom n=0.03
BC Design=,, 0 ,, 0 ,,,,,,
BC Use User HTab Curves=0
BC User HTab FreeFlow(D)= 0