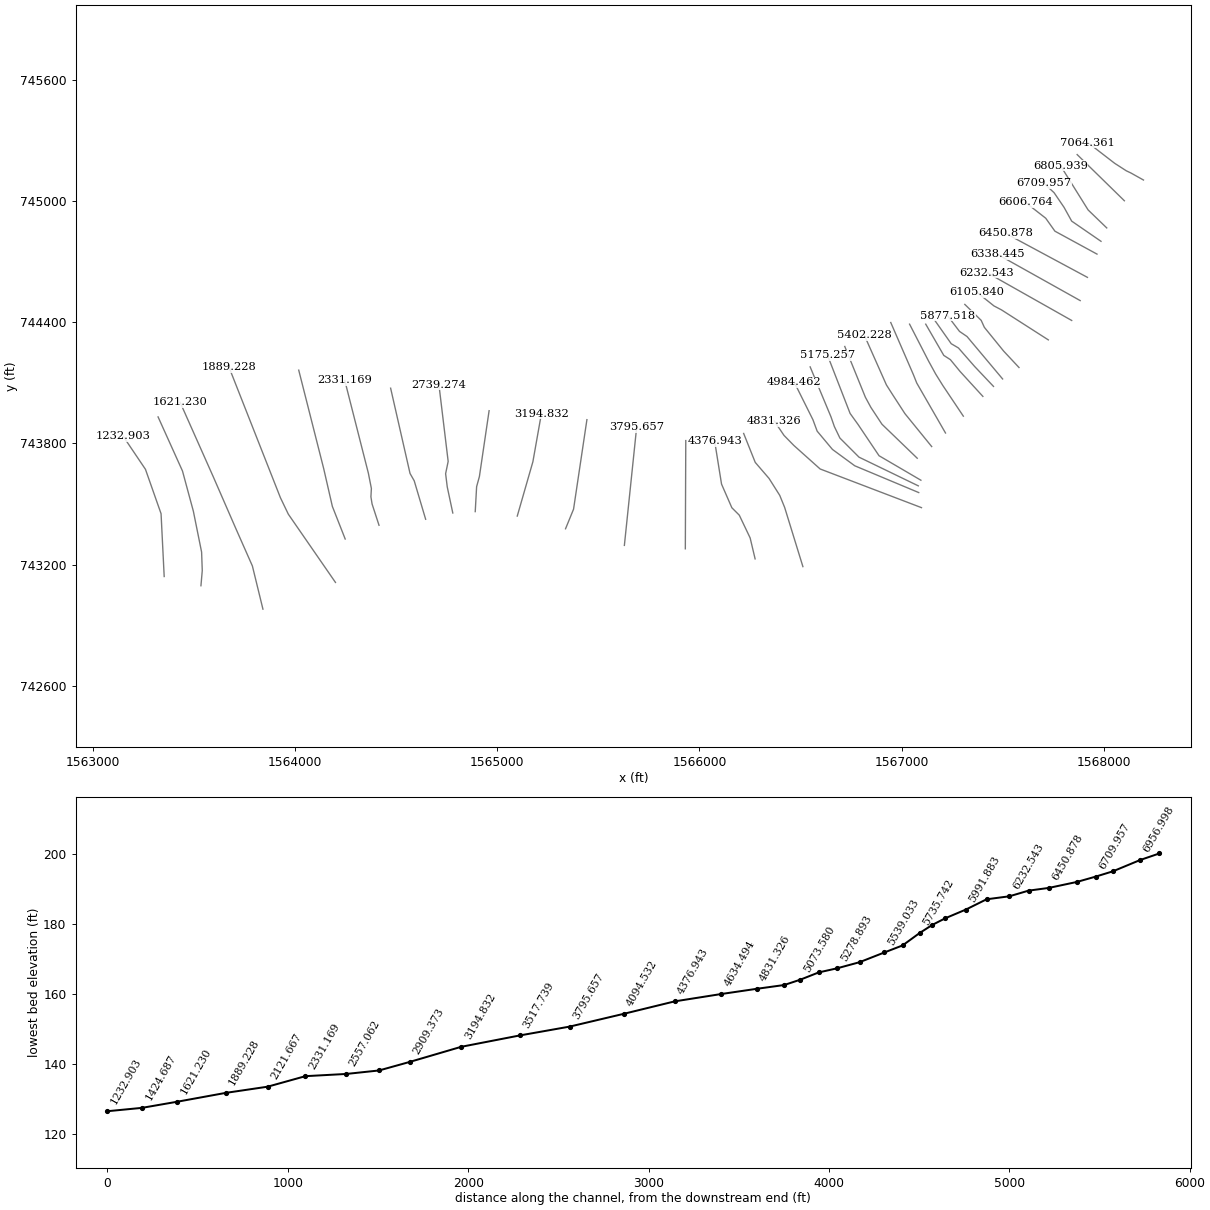
HEC-RAS study StoneRun.prj: StoneRun

--- StoneRun.g01 (geometry) --- (continued)

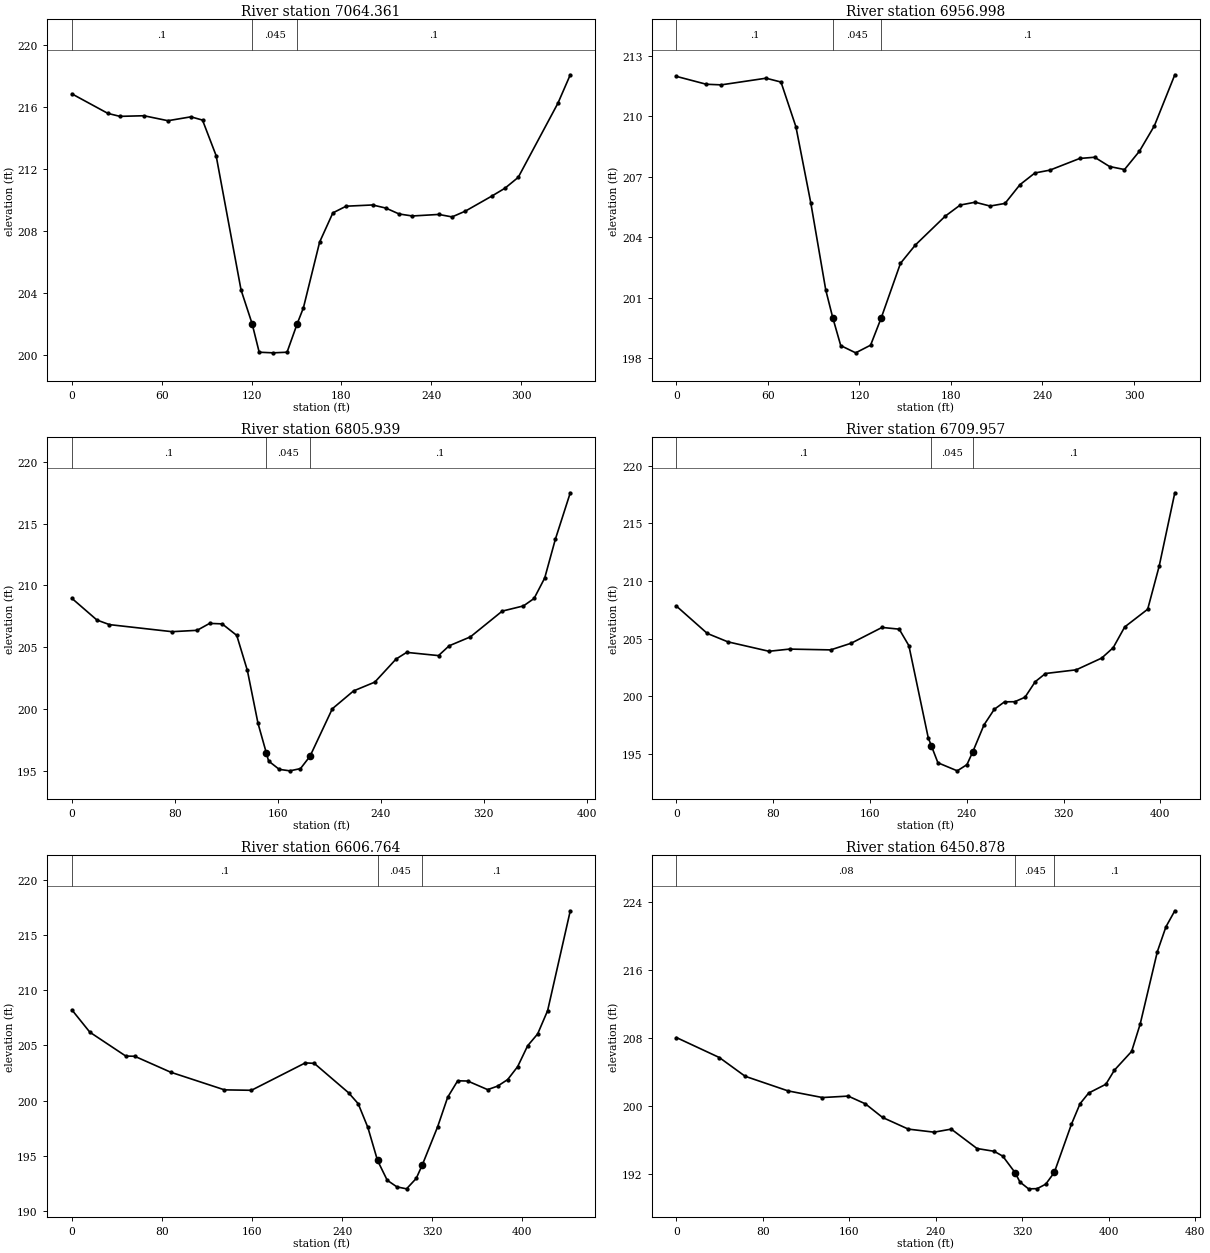
Type RM Length L Ch R = 1 ,7064.361,111.86,107.36,104.71
BEGIN DESCRIPTION:
Center of channel lowered 1.0 ft based on bridge survey info.
END DESCRIPTION:
XS GIS Cut Line= 5
1568197.15236147745103.3782690911568134.52202293745138.428275064
1568112.30079068745148.9216347491568054.19378382745186.410026252
1567921.66774438745288.762726352
#Sta/Elev= 30
       0  216.85   24.06  215.59   32.09   215.4   48.13  215.44   64.17  215.12
   79.51  215.37   87.25  215.16   96.35  212.87  113.01  204.21  120.38  202.04
  125.12   200.2  134.42  200.16  143.73   200.2  150.49  202.03  154.66  203.06
   165.5   207.3  174.34  209.18  183.19  209.61  200.87  209.69  209.72  209.49
  218.56  209.11  227.41  208.98   245.1  209.08  253.94  208.92  262.79  209.29
  280.48  210.26  289.32  210.77  298.17  211.47   324.7  216.25  332.94  218.08
#Mann= 3 , 0 , 0
       0      .1       0  120.38    .045       0  150.49      .1       0
Bank Sta=120.38,150.49
XS Rating Curve= 0 ,0
Exp/Cntr=0.5,0.3

Type RM Length L Ch R = 1 ,6956.998,156.3,151.06,137.13
XS GIS Cut Line= 2
 1568102.6141953 745000.78552036 1567869.0373781745229.284580693
#Sta/Elev= 30
       0  211.98   19.58  211.59   29.38  211.56   58.75  211.89   68.55   211.7
   78.34  209.48   88.13  205.69   97.92  201.38  102.47  200.02  107.72  198.63
  117.51  198.27   127.3  198.65  134.35  200.02  146.89  202.71  156.68  203.62
  176.26  205.05  186.06   205.6  195.85  205.74  205.64  205.55  215.43  205.68
  225.23  206.61  235.02  207.19  244.81  207.33   264.4  207.91  274.19  207.97
  283.98  207.51  293.77  207.36  303.57  208.27  313.36  209.53  326.76  212.06
#Mann= 3 , 0 , 0
       0      .1       0  102.47    .045       0  134.35      .1       0
Bank Sta=102.47,134.35
XS Rating Curve= 0 ,0
Exp/Cntr=0.3,0.1

Type RM Length L Ch R = 1 ,6805.939,97.68,95.98,94.99
XS GIS Cut Line= 3
1568015.40115687744866.3223075871567923.24113832744955.261744052
1567786.10068212745175.121840447
#Sta/Elev= 30
       0  208.96   19.46  207.21   29.18  206.84   77.82  206.27   97.28  206.38
  107.01  206.94  116.74   206.9  128.08  205.97  136.33  203.14  144.58  198.88
  151.01   196.5  152.83  195.83  161.08  195.16  169.33  195.04  177.58  195.22
  185.01  196.22  202.33  200.05  218.83  201.49  235.33   202.2  251.83  204.06
  260.08   204.6  284.83  204.34  293.08  205.13  309.58  205.85  334.33  207.93
  350.83  208.35  359.08  208.95  367.33   210.6  375.58  213.72   387.2  217.48
#Mann= 3 , 0 , 0
       0      .1       0  151.01    .045       0  185.01      .1       0
Bank Sta=151.01,185.01
XS Rating Curve= 0 ,0
Exp/Cntr=0.3,0.1

Type RM Length L Ch R = 1 ,6709.957,100.6,103.19,108.24
XS GIS Cut Line= 5
1567987.01341088744800.0842336861567841.92048708744899.967043579
1567804.07015911744968.3079134671567754.65445317745040.854375377
1567703.13595124745088.167285323
#Sta/Elev= 30
       0  207.82   25.49  205.45   42.49  204.72   76.48   203.9   93.48  204.09
  127.47  204.02  144.47   204.6  169.97  205.97  184.15  205.82  192.15  204.39
  208.16  196.39  210.82  195.67  216.16  194.22  232.16  193.52  240.16  194.06
  244.85  195.14  254.27  197.51  262.74  198.86  271.21  199.51  279.68  199.52
  288.15  199.91  296.62  201.26  305.09  201.97   330.5  202.29  351.55  203.31
  361.06  204.21  370.56  206.01  389.57  207.55  399.07  211.29     412  217.66
#Mann= 3 , 0 , 0
       0      .1       0  210.82    .045       0  244.85      .1       0
Bank Sta=210.82,244.85
XS Rating Curve= 0 ,0
Exp/Cntr=0.3,0.1

Type RM Length L Ch R = 1 ,6606.764,136.38,155.89,165.65
XS GIS Cut Line= 4
1567967.20734474744736.7421617811567759.01931202744850.145399123
1567713.31949995744914.4636531471567613.45694764744992.322592214
#Sta/Elev= 30
       0  208.21   15.94  206.19   47.83  204.03    55.8  204.01   87.68  202.57
  135.51  200.97  159.42  200.93  207.25  203.41  215.22  203.37  245.66  200.71
  254.24  199.72  262.83  197.57  271.42  194.58  280.01  192.79  288.59  192.19
  297.18  192.01  305.77  192.95  311.24  194.19  324.85  197.64  333.72   200.3
   342.6  201.79  351.48  201.77  369.23  200.99   378.1  201.31  386.98   201.9
  395.86  203.07  404.73  204.96  413.61  206.03  422.48  208.14   442.6  217.18
#Mann= 3 , 0 , 0
       0      .1       0  271.42    .045       0  311.24      .1       0
#XS Ineff= 2 , 0
          212.55  203.32
Permanent Ineff=
       F       F
Bank Sta=271.42,311.24
XS Rating Curve= 0 ,0
Exp/Cntr=0.3,0.1

Type RM Length L Ch R = 1 ,6450.878,114.21,112.43,112.7
XS GIS Cut Line= 2
1567919.81494705744621.6463388061567513.59439537744839.989885345
#Sta/Elev= 30
       0  208.08   39.74  205.73   63.58  203.53  103.31  201.81   135.1  201.03
  158.94   201.2  174.84  200.29  190.73  198.69  214.57  197.32  238.41  196.96
  254.31  197.32  278.15  195.04  294.04  194.71  301.99  194.14  313.33  192.21
  317.88   191.1  325.83   190.3  333.78  190.32  341.73  190.85  349.67  192.23
  365.57  197.91  373.51  200.31  381.46  201.56  397.36  202.59   405.3  204.25
   421.2  206.45  429.14  209.67  445.04  218.19  452.98   221.1  461.18  222.98
#Mann= 3 , 0 , 0
       0     .08       0  313.33    .045       0  349.67      .1       0
Bank Sta=313.33,349.67
XS Rating Curve= 0 ,0
Exp/Cntr=0.3,0.1

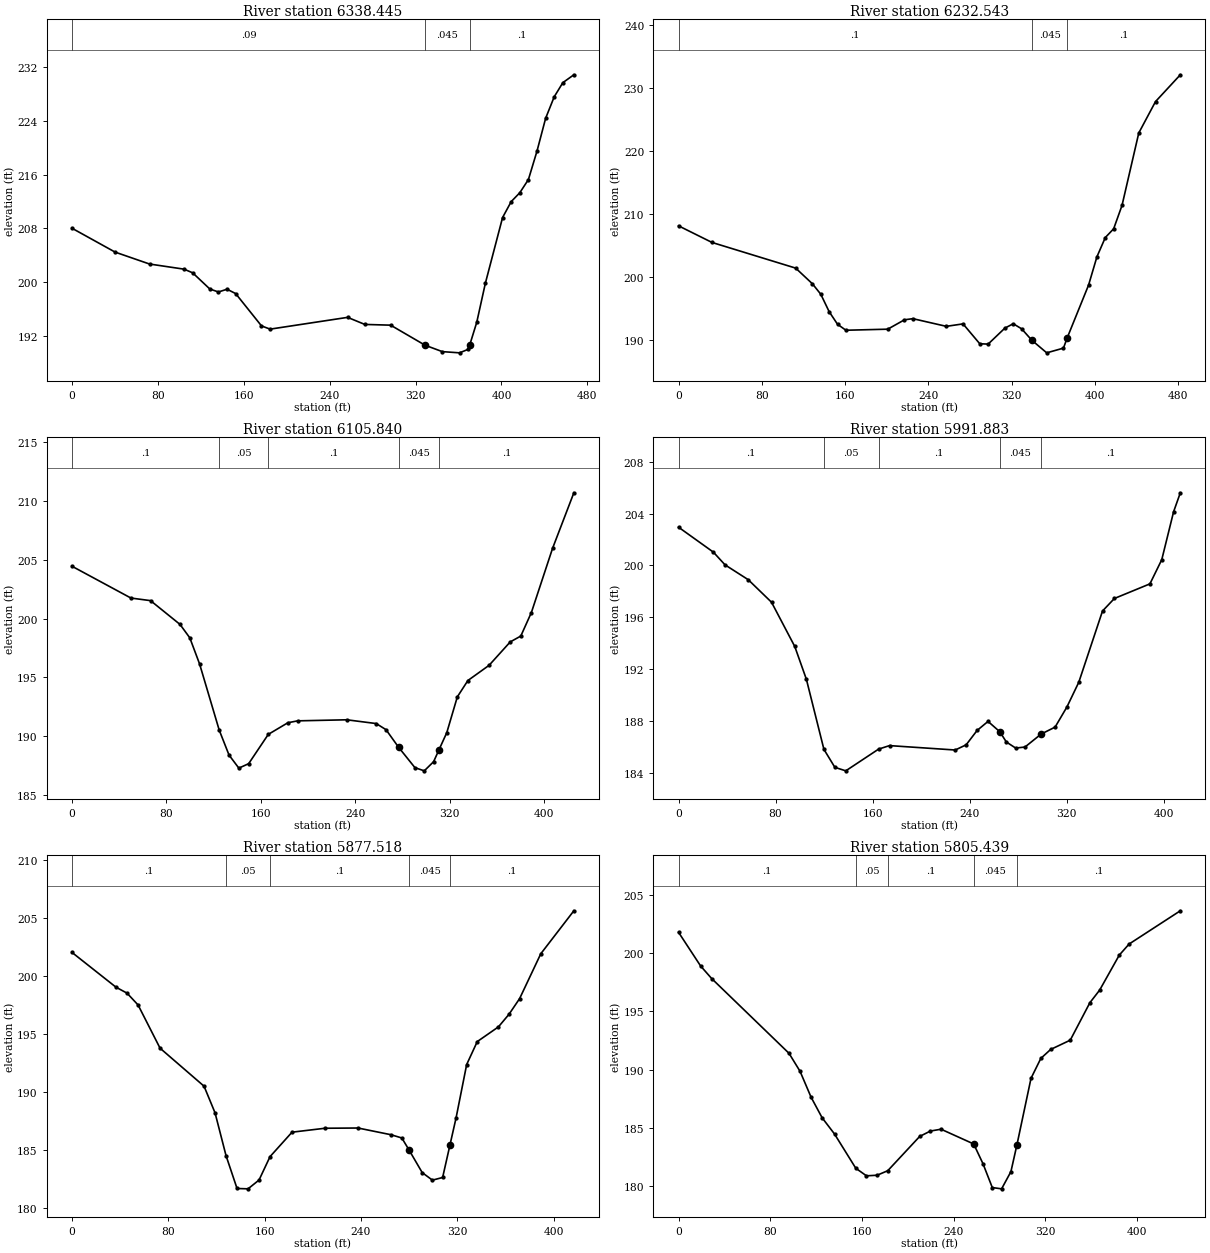
Type RM Length L Ch R = 1 ,6338.445,106.12,105.9,105.53
XS GIS Cut Line= 2
1567883.97640699744506.7441920491567476.03398353744734.897557765
#Sta/Elev= 30
       0  208.02    40.1  204.48   72.18  202.71  104.27  201.95  112.29  201.41
  128.33     199  136.35  198.56  144.37  198.97  152.39  198.32  176.45  193.52
  184.47  193.04  256.65  194.79  272.69  193.74  296.75  193.63  328.84  190.65
  344.88   189.7  360.92  189.52  368.94  190.04  370.36  190.66  376.96  194.06
  384.98  199.86  401.02  209.62  409.04  211.98  417.06   213.3  425.08  215.26
   433.1   219.5  441.12  224.36  449.14  227.56  457.16  229.65  467.41  230.82
#Mann= 3 , 0 , 0
       0     .09       0  328.84    .045       0  370.36      .1       0
Bank Sta=328.84,370.36
XS Rating Curve= 0 ,0
Exp/Cntr=0.3,0.1

Type RM Length L Ch R = 1 ,6232.543,128.87,126.7,125.21
XS GIS Cut Line= 2
1567841.95600794744408.3805491921567422.19477125744645.342537671
#Sta/Elev= 30
       0  208.09   32.15  205.45  112.54  201.37  128.61  198.88  136.65  197.22
  144.69  194.45  152.73  192.45  160.77   191.5  200.96  191.67  217.04  193.16
  225.07  193.34  257.23  192.12   273.3  192.51  289.38  189.35  297.42   189.3
   313.5  191.84  321.53  192.53  329.57  191.73   339.4  189.91  353.69  187.91
  369.76  188.66  373.43  190.32  393.88  198.67  401.92  203.17  409.96  206.23
  417.99  207.62  426.03  211.34  442.11  222.84  458.19  227.83  482.03  232.09
#Mann= 3 , 0 , 0
       0      .1       0   339.4    .045       0  373.43      .1       0
Bank Sta=339.4,373.43
XS Rating Curve= 0 ,0
Exp/Cntr=0.3,0.1

Type RM Length L Ch R = 1 ,6105.840,145.03,113.96,96.54
XS GIS Cut Line= 4
1567726.26670723744312.235562295 1567494.9591475744460.482680097
1567457.10881954744480.4592420611567372.99697964   744547.748714
#Sta/Elev= 30
       0  204.44   49.89  201.74   66.51  201.52   91.46   199.5   99.77  198.36
  108.09  196.13  124.71  190.51  133.03  188.39  141.34  187.28  149.66  187.66
  166.29  190.15  182.91  191.14  191.23   191.3   232.8  191.39  257.74  191.07
  266.06  190.55  276.67  189.06  290.57  187.32  298.48  187.05   306.4  187.83
  310.99  188.85  317.54  190.29   326.5  193.34  335.46  194.73  353.39  196.02
  371.32  198.01  380.29  198.51  389.25  200.51  407.18  205.96  425.25  210.69
#Mann= 5 ,-1 , 0
       0      .1       0  124.71     .05       0  166.29      .1       0
  276.67    .045       0  310.99      .1       0
Bank Sta=276.67,310.99
XS Rating Curve= 0 ,0
Exp/Cntr=0.3,0.1

Type RM Length L Ch R = 1 ,5991.883,98.14,114.36,116.55
XS GIS Cut Line= 5
1567581.17378336744175.553822443 1567505.4731275744256.511468336
1567409.79590961744374.2680441891567394.02493963 744408.96417816
 1567313.0672937744487.819028065
#Sta/Elev= 30
       0  202.96   28.75  201.03   38.33  200.05    57.5   198.9   76.67  197.16
   95.83  193.74  105.42   191.2  119.86  185.79  128.88   184.4  137.89  184.13
  164.95  185.81  173.97  186.08  228.09  185.74  237.11  186.14  246.13  187.25
  255.15  187.95  264.89  187.15  270.25  186.36  277.94  185.89  285.63  185.97
  298.89  186.97  310.45  187.51  320.22  189.07  329.99  190.98  349.53  196.48
  359.31  197.45  388.62  198.58  398.39  200.45  408.16  204.16  413.69  205.62
#Mann= 5 ,-1 , 0
       0      .1       0  119.86     .05       0  164.95      .1       0
  264.89    .045       0  298.89      .1       0
Bank Sta=264.89,298.89
XS Rating Curve= 0 ,0
Exp/Cntr=0.3,0.1

Type RM Length L Ch R = 1 ,5877.518,71.07,72.08,74.6
XS GIS Cut Line= 4
1567500.05371034744118.9484061451567324.02480461744328.829024494
1567286.78792068744354.217808962 1567227.5474236744432.076748043
#Sta/Elev= 30
       0  202.04   36.54  199.04   45.68  198.53   54.82  197.51   73.09  193.78
  109.63   190.5  118.77   188.2  127.91   184.5  137.04  181.67  146.18  181.64
  155.31   182.4  164.45  184.42  182.72  186.53  210.13  186.87  237.54  186.89
  264.95  186.31  273.93  186.03  279.94  184.99  290.87  183.04  299.34  182.39
  307.82  182.62  313.96  185.45     319  187.77  327.79  192.37  336.59  194.35
  354.18  195.62  362.98  196.71  371.77  198.06  389.36  201.93  416.83  205.64
#Mann= 5 ,-1 , 0
       0      .1       0  127.91     .05       0  164.45      .1       0
  279.94    .045       0  313.96      .1       0
Bank Sta=279.94,313.96
XS Rating Curve= 0 ,0
Exp/Cntr=0.3,0.1

Type RM Length L Ch R = 1 ,5805.439,75.27,69.7,62.77
XS GIS Cut Line= 5
1567455.00602354744081.9794005451567361.43160166744180.810812443
1567281.52535377744272.2824383231567245.77782182744293.310398296
1567165.87157388744406.861382172
#Sta/Elev= 30
       0  201.81   19.28  198.91   28.92  197.83    96.4   191.4  106.04  189.85
  115.68  187.62  125.32  185.85   136.1  184.46  154.69  181.51  163.99  180.86
  173.28  180.91  182.58   181.3  210.46  184.25  219.76  184.71  229.05  184.87
  257.56   183.6  265.68   181.9   273.8  179.85  281.92  179.74  290.05  181.22
  295.35  183.55  307.59  189.25  316.15  190.96  324.71  191.73  341.83  192.53
  358.95  195.75  367.51  196.84  384.63  199.85  393.19   200.8  437.88  203.66
#Mann= 5 ,-1 , 0
       0      .1       0  154.69     .05       0  182.58      .1       0
  257.56    .045       0  295.35      .1       0
Bank Sta=257.56,295.35
XS Rating Curve= 0 ,0
Exp/Cntr=0.3,0.1

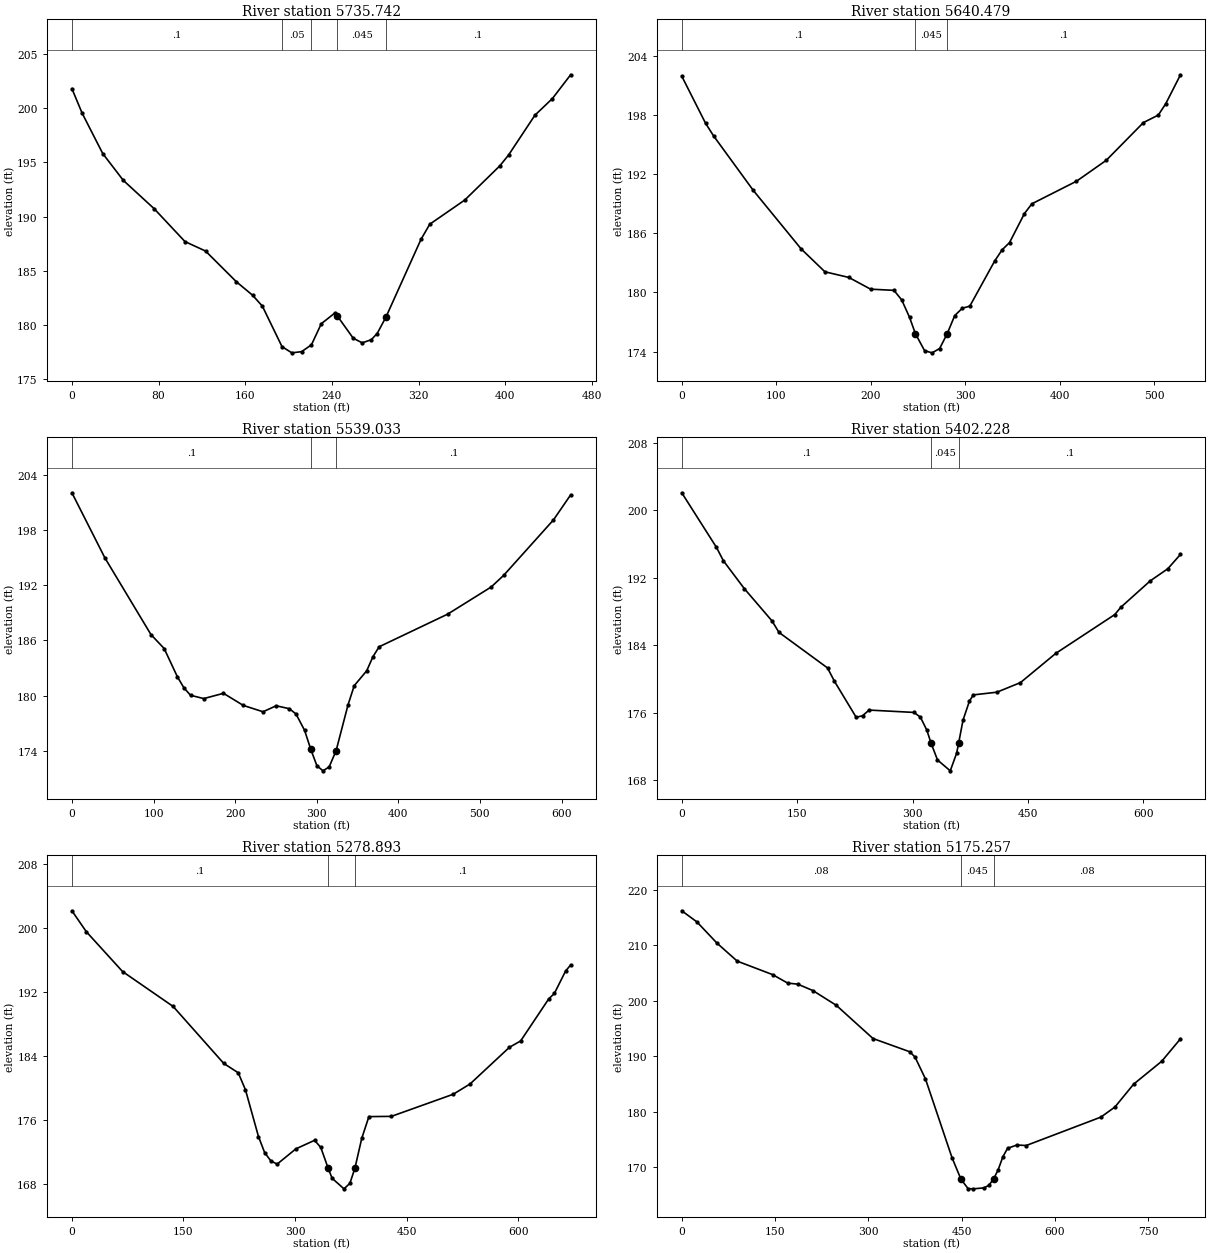
Type RM Length L Ch R = 1 ,5735.742,106.61,95.26,82.58
XS GIS Cut Line= 5
1567402.43612361744032.5636946111567289.93653776744155.577260464
 1567241.5722298744214.4555484061567208.97889185744235.483508378
1567119.61006194744390.039014176
#Sta/Elev= 30
       0  201.78    9.49  199.51   28.46   195.8   47.43  193.33   75.89  190.72
  104.34  187.69  123.32  186.82  151.77  183.99   166.7  182.75  175.76  181.74
  193.88  178.01  202.93  177.44  211.99  177.55  221.05  178.18  230.11  180.12
  242.89  181.13  244.83  180.85  259.56  178.79  267.89  178.36  276.22  178.65
  281.68  179.22  289.77  180.73  322.11  187.89   330.2  189.29  362.54  191.52
  394.89  194.67  402.97  195.67  427.23  199.33   443.4  200.87  460.22  203.06
#Mann= 5 ,-1 , 0
       0      .1       0  193.88     .05       0  221.05      .1       0
  244.83    .045       0  289.77      .1       0
Bank Sta=244.83,289.77
XS Rating Curve= 0 ,0
Exp/Cntr=0.3,0.1

Type RM Length L Ch R = 1 ,5640.479,105.12,101.44,97.59
XS GIS Cut Line= 5
 1567305.7075077743934.7836807521567203.72190185744087.236390546
1567169.02576788744142.9604844751567133.27823593744208.147160411
1567039.70381406744390.039014176
#Sta/Elev= 30
       0  201.94   25.27  197.15   33.69  195.88    75.8  190.34  126.33  184.42
  151.59  182.09  176.86  181.52  199.91  180.33  224.65  180.21   232.9  179.23
  241.14  177.47  247.33  175.82  257.05  174.09  265.03  173.87  273.01  174.31
     281  175.81  288.98  177.65  296.96  178.39  304.95  178.61  331.28  183.19
  339.15  184.32  347.02  185.06  362.77     188  370.64  188.99  417.87  191.28
  449.36   193.4  488.72  197.23  504.46  197.99  512.34  199.14  527.96  202.08
#Mann= 3 , 0 , 0
       0      .1       0  247.33    .045       0     281      .1       0
Bank Sta=247.33,281
XS Rating Curve= 0 ,0
Exp/Cntr=0.3,0.1

Type RM Length L Ch R = 1 ,5539.033,129.74,136.8,142.38
XS GIS Cut Line= 4
1567217.39190978743851.519876301 1567075.2147167744098.637378573
1567058.28886037744140.9520193641566946.57820871744398.225035399
#Sta/Elev= 30
       0  202.02   40.38  194.96   96.91  186.63  113.06  185.12  129.21  182.06
  137.29  180.85  145.37  180.05  161.52  179.69  185.75  180.26  209.97  178.95
   234.2  178.26  250.35  178.91   266.5  178.59  274.58  178.02   285.1  176.25
  292.64   174.2  300.18  172.41  307.72  171.85  315.26  172.28  323.79  174.05
   338.3  178.99  345.94  181.09   361.2   182.7  368.83  184.22  376.46  185.31
  460.41  188.85  513.83   191.8  529.09  193.06  590.14  199.08  611.15  201.79
#Mann= 3 , 0 , 0
       0      .1       0  292.64    .045       0  323.79      .1       0
Bank Sta=292.64,323.79
XS Rating Curve= 0 ,0
Exp/Cntr=0.3,0.1

Type RM Length L Ch R = 1 ,5402.228,126.61,123.33,121.42
XS GIS Cut Line= 5
1567149.04920591743784.4337669161567016.57305811743947.400456727
1566954.54057617744043.0776746121566925.10143219744089.339186549
1566815.75604033744335.366318241
#Sta/Elev= 30
       0  202.07   45.11  195.59   54.13     194   81.19  190.71  117.27  186.87
   126.3  185.51  189.44  181.29  198.46   179.7   226.7  175.43  235.05  175.62
  243.39  176.29  301.79  176.01  310.13  175.45  318.47  173.91  324.05  172.35
  332.34  170.37  348.94  169.08  357.23  171.18  359.75  172.34  365.53   175.1
  373.83  177.35  378.88  178.09  409.52  178.41  440.16  179.55  486.12  183.02
  562.73  187.62  570.39  188.47  608.69  191.61  631.67  193.06  648.11  194.76
#Mann= 3 , 0 , 0
       0      .1       0  324.05    .045       0  359.75      .1       0
Bank Sta=324.05,359.75
XS Rating Curve= 0 ,0
Exp/Cntr=0.3,0.1

Type RM Length L Ch R = 1 ,5278.893,101.19,103.64,104.11
XS GIS Cut Line= 5
1567077.55414201743726.6068769991566903.02207422 743894.83055678
 1566848.3493783743977.8909987061566821.01303034 744028.35810262
1566719.02742447744279.642224312
#Sta/Elev= 30
       0  202.19   19.44  199.56   68.06  194.58  136.11   190.2  204.17  183.06
  223.61  181.89  233.33  179.75  250.79   173.9  259.17  171.87  267.55  170.84
  275.93  170.45  301.07  172.36  326.21  173.43  334.59  172.53  344.33  169.96
  349.81  168.67  365.73  167.35  373.69  168.04  380.46  169.95  389.61  173.67
  399.24   176.4  429.46  176.43  512.56   179.2  535.22  180.49   588.1  185.08
  603.21  185.88  640.99  191.15  648.54  191.83  663.65  194.64  670.43   195.4
#Mann= 3 , 0 , 0
       0      .1       0  344.33    .045       0  380.46      .1       0
Bank Sta=344.33,380.46
XS Rating Curve= 0 ,0
Exp/Cntr=0.3,0.1

Type RM Length L Ch R = 1 ,5175.257,107.78,101.68,96.31
XS GIS Cut Line= 5
1567095.72684357743617.7587180881566888.57782382743738.962931797
1566785.00331391743893.2228401011566745.33648038  743948.3156645
1566633.86418654744235.483508378
#Sta/Elev= 30
       0  216.21   24.33  214.21   56.77  210.37   89.21  207.14  145.98  204.72
  170.31  203.19  186.53     203  210.86  201.84  248.43  199.19  307.45  193.21
  366.47  190.83  374.91  189.89  391.77  185.94  434.43  171.77  448.76   167.9
  460.31  166.18  468.94  166.15  486.19  166.33   493.7  166.79   501.2   167.9
  508.71   169.6  516.22  171.92  523.73  173.44  538.75  174.04  553.77  173.95
  673.91  179.07  696.44  180.89  726.47     185  771.53  189.11  801.74  193.16
#Mann= 3 , 0 , 0
       0     .08       0  448.76    .045       0   501.2     .08       0
Bank Sta=448.76,501.2
XS Rating Curve= 0 ,0
Exp/Cntr=0.3,0.1

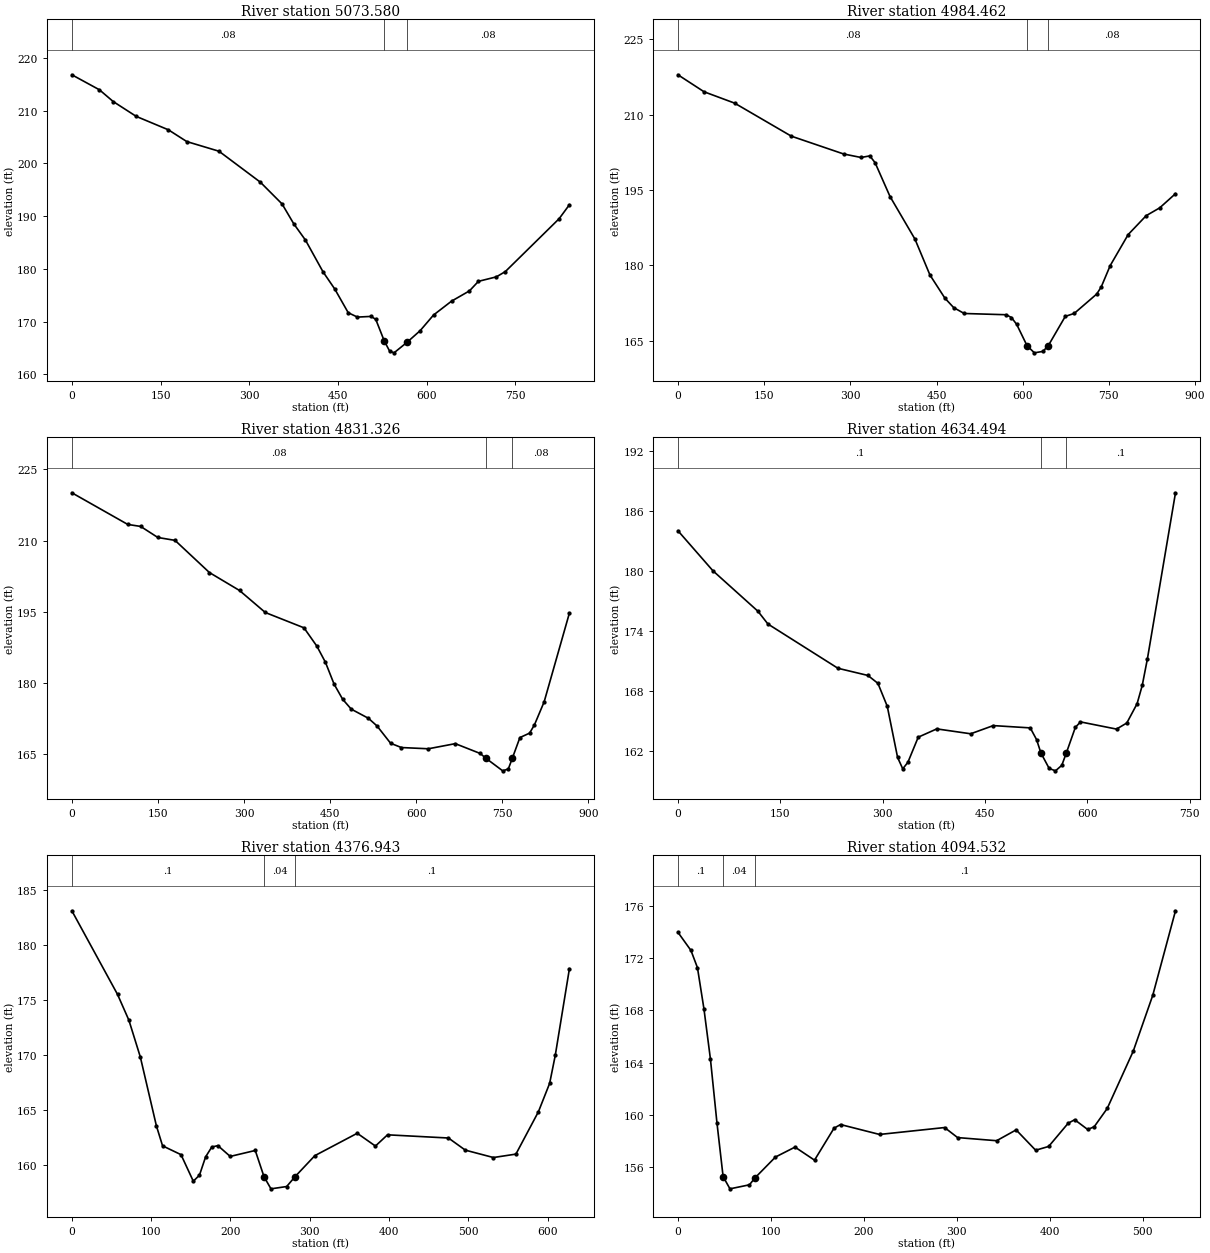
Type RM Length L Ch R = 1 ,5073.580,76.71,89.12,89.38
XS GIS Cut Line= 6
1567082.81113201743589.9251371471566789.47109035   743731.863867
1566694.84527044743826.4896868911566667.50892253743883.265178815
1566650.68655451 743931.629486741566547.64955068744178.708016455
#Sta/Elev= 30
       0  216.82   46.66  213.97   69.99  211.74  108.87  208.93   163.3  206.38
  194.41  204.15  248.84  202.32  318.83  196.45  355.57  192.32  375.37  188.55
  395.17  185.46  424.87  179.44  444.67  176.19  467.47  171.69     483  170.86
  506.31  170.99  514.08  170.42  528.45  166.33  537.53   164.4  544.94  164.08
  567.18   166.1  589.09  168.28  611.84  171.26  642.18  173.88  672.51  175.83
  687.68  177.64  718.02  178.49  733.19  179.49   824.2  189.52  841.62  192.17
#Mann= 3 , 0 , 0
       0     .08       0  528.45    .045       0  567.18     .08       0
Bank Sta=528.45,567.18
XS Rating Curve= 0 ,0
Exp/Cntr=0.3,0.1

Type RM Length L Ch R = 1 ,4984.462,130.19,153.14,164.17
XS GIS Cut Line= 6
1567084.91392802743556.700960413 1566768.4431304743689.177108243
1566658.04634051743770.1347541361566582.34568459743860.554982021
1566561.31772466743917.3304739591566468.79470077744103.007360533
#Sta/Elev= 30
       0  217.96   45.53  214.57   98.65  212.31   197.3  205.73  288.37  202.18
  318.72  201.48   333.9   201.8  343.08  200.45  369.12   193.7  412.52  185.21
  438.57  178.07  464.61  173.45  479.98  171.56  498.24   170.4  571.27  170.15
   580.4   169.6  589.53  168.23  607.52  163.99   620.3  162.56  635.23  162.85
  644.51  163.99  674.09  169.82  689.73  170.42  728.84  174.28  736.66  175.69
   752.3  179.95  783.58  186.13  814.87  189.89  838.33  191.44   865.9  194.27
#Mann= 3 , 0 , 0
       0     .08       0  607.52    .045       0  644.51     .08       0
Bank Sta=607.52,644.51
XS Rating Curve= 0 ,0
Exp/Cntr=0.3,0.1

Type RM Length L Ch R = 1 ,4831.326,205.52,196.83,186.31
XS GIS Cut Line= 5
  1567098.582102743482.0517024991566597.06525661743673.406138256
1566466.69190475743790.111316115 1566418.3275968743839.527022049
1566369.96328884 743911.02208598
#Sta/Elev= 30
       0  220.07    97.4   213.4  119.88  212.98  149.84  210.65  179.81  210.04
  239.75  203.26   292.2  199.48  337.15  194.84  404.58  191.61  427.06  187.74
  442.04  184.33  457.03  179.75  472.01  176.55  486.99  174.47  516.96  172.54
  531.95  170.92  555.57  167.28  574.36  166.38  621.34  166.12  668.31   167.2
  711.76  165.13  721.55  164.13  750.94  161.47  760.73  161.87  767.75  164.14
  780.91  168.48  797.81  169.42  806.26  171.16  823.16  176.01  867.22  194.73
#Mann= 3 , 0 , 0
       0     .08       0  721.55     .04       0  767.75     .08       0
Bank Sta=721.55,767.75
XS Rating Curve= 0 ,0
Exp/Cntr=0.3,0.1

Type RM Length L Ch R = 1 ,4634.494,256.15,257.55,212.9
XS GIS Cut Line= 6
 1566511.7429049743190.2384006981566421.39067286 743483.33222653
1566397.14983009743542.8324768841566344.26071869743626.573569968
1566275.94561642743705.9072371131566218.64907902743849.148580581
#Sta/Elev= 30
       0  184.02   51.28  180.01   117.2  175.96  131.85  174.68   234.4  170.25
  278.35  169.53     293  168.74   306.7  166.44  321.82  161.32  329.38  160.18
  336.94  160.84  352.06  163.35  379.23  164.18  428.91  163.69  462.02  164.51
  516.19  164.28  525.42  163.11  531.85  161.76   543.9  160.22  553.14  159.98
  562.37  160.53  568.99  161.76  582.23  164.33  589.77  164.88  642.54  164.16
  657.62  164.77   672.7   166.7  680.24  168.53  687.78  171.18  728.97  187.82
#Mann= 3 , 0 , 0
       0      .1       0  531.85     .04       0  568.99      .1       0
Bank Sta=531.85,568.99
XS Rating Curve= 0 ,0
Exp/Cntr=0.3,0.1

Type RM Length L Ch R = 1 ,4376.943,304.17,282.41,214.6
XS GIS Cut Line= 6
1566275.29607885743228.4597195241566250.68203071743332.190351009
1566197.05856867743444.711714014 1566160.1374964743481.632786229
1566109.15125382743598.549514979  1566074.867401743812.164290041
#Sta/Elev= 30
       0   183.1   57.55  175.52   71.94  173.17   86.33  169.84  106.61  163.59
  114.37  161.78  137.63  160.98  153.14  158.57  160.89  159.12  168.65  160.78
   176.4  161.67  184.15   161.8  199.66  160.82  231.26  161.36  242.29  158.98
  251.06  157.88  270.85  158.09  281.49  158.99  306.38  160.89  359.84  162.92
  382.75  161.76  398.02  162.78  474.83  162.49   496.1  161.39  531.54  160.72
   559.9  161.03  588.26  164.87  602.44  167.45  609.53  169.99  627.37  177.85
#Mann= 3 , 0 , 0
       0      .1       0  242.29     .04       0  281.49      .1       0
Bank Sta=242.29,281.49
XS Rating Curve= 0 ,0
Exp/Cntr=0.3,0.1

Type RM Length L Ch R = 1 ,4094.532,301.19,298.88,282.18
XS GIS Cut Line= 2
1565929.96267915743278.3869197521565932.16639215743813.889172971
#Sta/Elev= 30
       0  173.99      14   172.6      21  171.28      28  168.12      35  164.26
      42  159.38   48.62  155.26      56  154.32      77  154.63   82.79  155.15
     105  156.76     126  157.52     147  156.52     168  158.97     175  159.25
     217  158.49     287  159.02     301  158.25     343  158.01     364  158.84
     385  157.28     399  157.57     420  159.35     427  159.62     441  158.87
     448  159.08     462  160.48     490  164.87     511  169.15  535.51  175.64
#Mann= 3 , 0 , 0
       0      .1       0   48.62     .04       0   82.79      .1       0
Bank Sta=48.62,82.79
XS Rating Curve= 0 ,0
Exp/Cntr=0.3,0.1

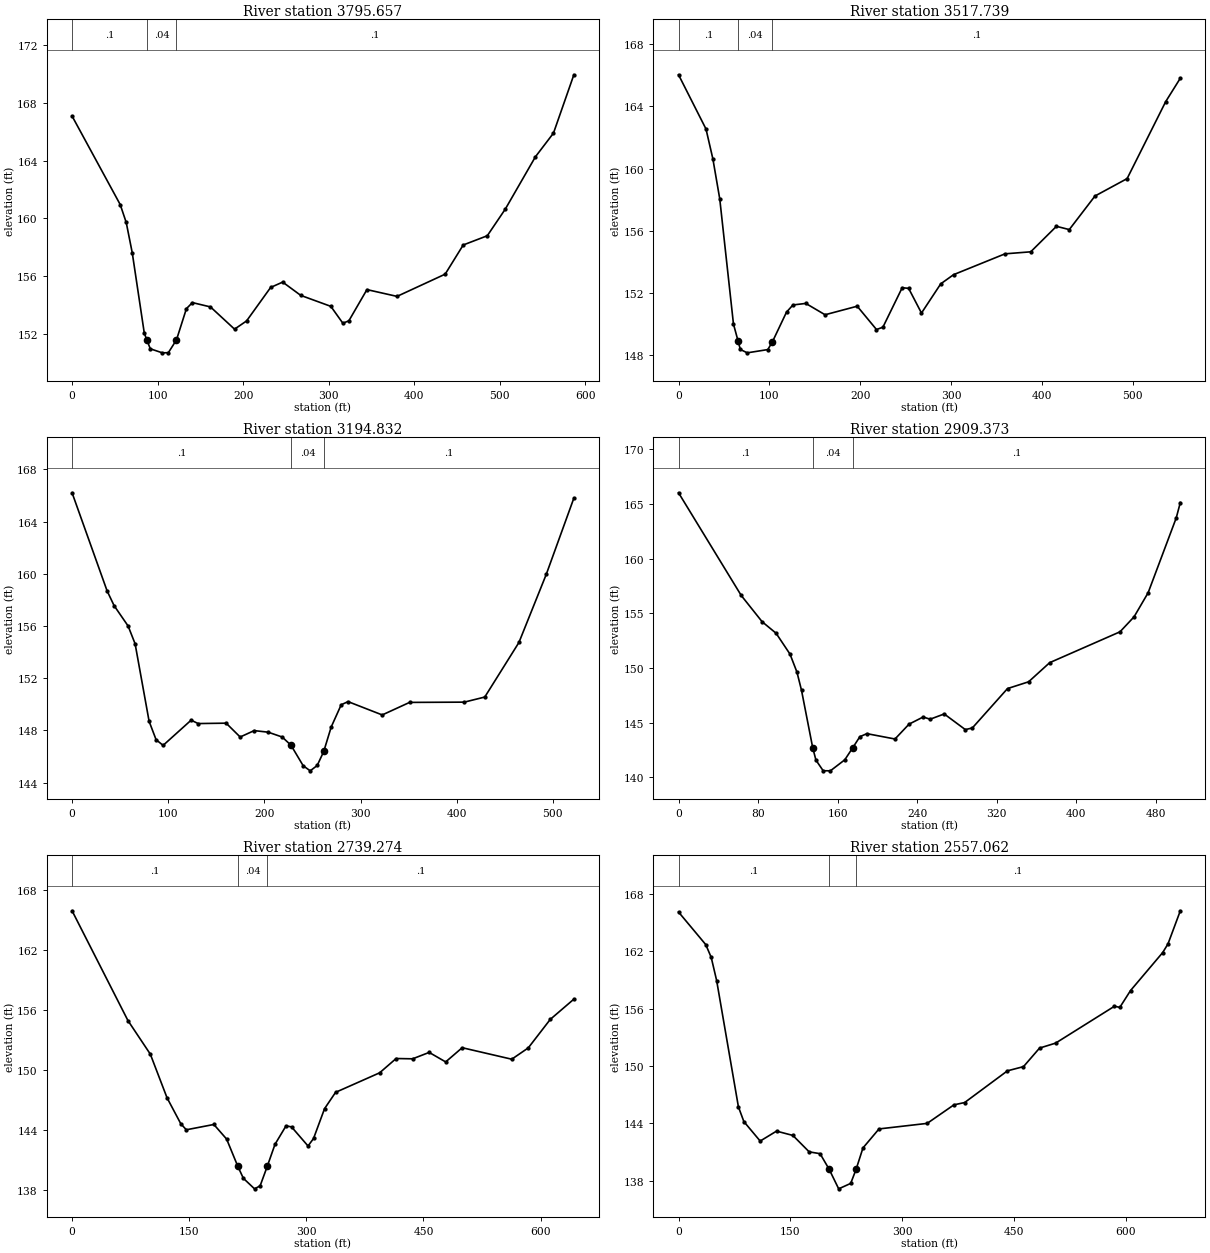
Type RM Length L Ch R = 1 ,3795.657,284.31,277.92,270.22
XS GIS Cut Line= 2
1565628.29824165743295.2692787951565688.95428891743878.973849311
#Sta/Elev= 30
       0  167.08    56.3  160.95   63.34  159.71   70.38  157.61   84.45  152.05
   87.47  151.57   91.49  150.96  105.57  150.68   112.6  150.69  122.12  151.58
  133.72  153.74  140.75  154.16  161.87  153.86  190.02  152.32  204.09  152.89
  232.24  155.21  246.32  155.58  267.43  154.66  302.62   153.9   316.7  152.73
  323.73   152.9  344.85  155.06  380.04  154.59  436.34  156.13  457.45  158.15
   485.6  158.79  506.71  160.64   541.9  164.26  563.02   165.9  586.85  169.94
#Mann= 3 , 0 , 0
       0      .1       0   87.47     .04       0  122.12      .1       0
Bank Sta=87.47,122.12
XS Rating Curve= 0 ,0
Exp/Cntr=0.3,0.1

Type RM Length L Ch R = 1 ,3517.739,268.66,322.91,273.22
XS GIS Cut Line= 3
1565337.16388857743377.5540036561565376.83072211 743474.51737462
1565442.94211143743917.463682845
#Sta/Elev= 30
       0  166.03   30.25  162.54   37.82  160.62   45.38  158.05    60.5  149.99
   65.71  148.87   68.07  148.36   75.63  148.14   98.32  148.35  103.39  148.85
  118.92  150.76     126  151.22  140.15  151.32  161.38  150.59  196.77  151.14
     218  149.64  225.08  149.79  246.31  152.33  253.39  152.29  267.55   150.7
  288.78  152.58  302.93  153.17  359.55  154.51  387.87  154.64  416.18  156.28
  430.33  156.07  458.64  158.23  494.03  159.35  536.49   164.3  552.62  165.81
#Mann= 3 , 0 , 0
       0      .1       0   65.71     .04       0  103.39      .1       0
Bank Sta=65.71,103.39
XS Rating Curve= 0 ,0
Exp/Cntr=0.3,0.1

Type RM Length L Ch R = 1 ,3194.832,239.3,285.46,267.31
XS GIS Cut Line= 3
1565098.21713318743440.3163482551565175.57557023743709.312731683
1565217.77108131743947.541554868
#Sta/Elev= 30
       0   166.2   36.42  158.69    43.7  157.56   58.27     156   65.55  154.64
   80.12   148.7    87.4  147.29   94.69  146.86  123.82  148.79  131.11  148.53
  160.24  148.56  174.81   147.5  189.38  147.99  203.94  147.87  218.51   147.5
  227.68  146.87  240.36   145.3  247.65  144.91  254.93  145.32  261.75   146.4
   269.5  148.27   279.9  149.97  287.01  150.21  322.55  149.19  350.99  150.15
  407.86  150.17  429.19  150.56  464.73  154.74  493.17  159.96  521.84  165.79
#Mann= 3 , 0 , 0
       0      .1       0  227.68     .04       0  261.75      .1       0
Bank Sta=227.68,261.75
XS Rating Curve= 0 ,0
Exp/Cntr=0.3,0.1

Type RM Length L Ch R = 1 ,2909.373,153.08,170.1,167.9
XS GIS Cut Line= 4
1564890.23341452743462.3630844951564897.09758936743585.918232068
 1564910.8259391743635.6834998281564958.87516314743961.731805921
#Sta/Elev= 30
       0  166.01    63.1  156.62   84.13  154.22   98.15  153.17  112.17  151.26
  119.18  149.61  123.75  147.95  134.98  142.72  138.27  141.57  145.53   140.6
  152.79  140.59  167.31   141.6  175.37  142.71  182.45  143.71  189.52  143.99
  217.82   143.5  231.97  144.86  246.13  145.51   253.2  145.31  267.35  145.79
  288.58  144.36  295.65  144.51  331.03  148.11  352.26  148.73  373.49  150.48
  444.24   153.3  458.39  154.67  472.54  156.87  500.85  163.72  504.94  165.12
#Mann= 3 , 0 , 0
       0      .1       0  134.98     .04       0  175.37      .1       0
Bank Sta=134.98,175.37
XS Rating Curve= 0 ,0
Exp/Cntr=0.3,0.1

Type RM Length L Ch R = 1 ,2739.274,156.88,182.21,201.16
XS GIS Cut Line= 5
 1564779.1766821743455.5521655681564751.70782211743584.884714544
1564743.69607133743650.1232569521564756.28596546743710.783656046
1564710.50453217744090.769552216
#Sta/Elev= 30
       0  165.93   71.56  154.96  100.19  151.61  121.65  147.24  139.27  144.65
  146.32  144.05  181.59  144.58  197.95  143.12  212.24   140.4  219.39   139.2
  233.69  138.15  240.84  138.45  250.04  140.41   259.9   142.6     274  144.44
  281.05  144.34   302.2  142.43  309.25  143.18  323.35  146.16  337.46  147.79
  393.86  149.74  415.01  151.17  436.16  151.14  457.32  151.78  478.47  150.83
  499.62  152.25  563.08   151.1  584.23  152.23  612.43  155.08  642.63   157.1
#Mann= 3 , 0 , 0
       0      .1       0  212.24     .04       0  250.04      .1       0
Bank Sta=212.24,250.04
XS Rating Curve= 0 ,0
Exp/Cntr=0.3,0.1

Type RM Length L Ch R = 1 ,2557.062,234.27,225.89,202.17
XS GIS Cut Line= 4
1564644.83916308 743424.610122711564588.20972043 743615.09097524
1564567.61719584743651.1278932691564471.51874772744073.274647489
#Sta/Elev= 30
       0  166.12   36.51  162.71   43.82  161.38   51.12  158.95   80.33  145.73
   87.63  144.19  109.54  142.15  131.45  143.19  153.36  142.74  175.27  141.02
  189.87  140.83  201.98  139.21  214.85  137.15  230.97  137.72  238.24   139.2
  247.41  141.43  268.94  143.42  333.55     144  369.45  145.94  383.81  146.18
  441.24   149.5  462.78  149.94  484.31  151.88  505.85   152.4  584.82  156.26
     592  156.14  606.36   157.9  649.43  161.87  656.61  162.78  673.17  166.25
#Mann= 3 , 0 , 0
       0      .1       0  201.98     .04       0  238.24      .1       0
Bank Sta=201.98,238.24
XS Rating Curve= 0 ,0
Exp/Cntr=0.3,0.1

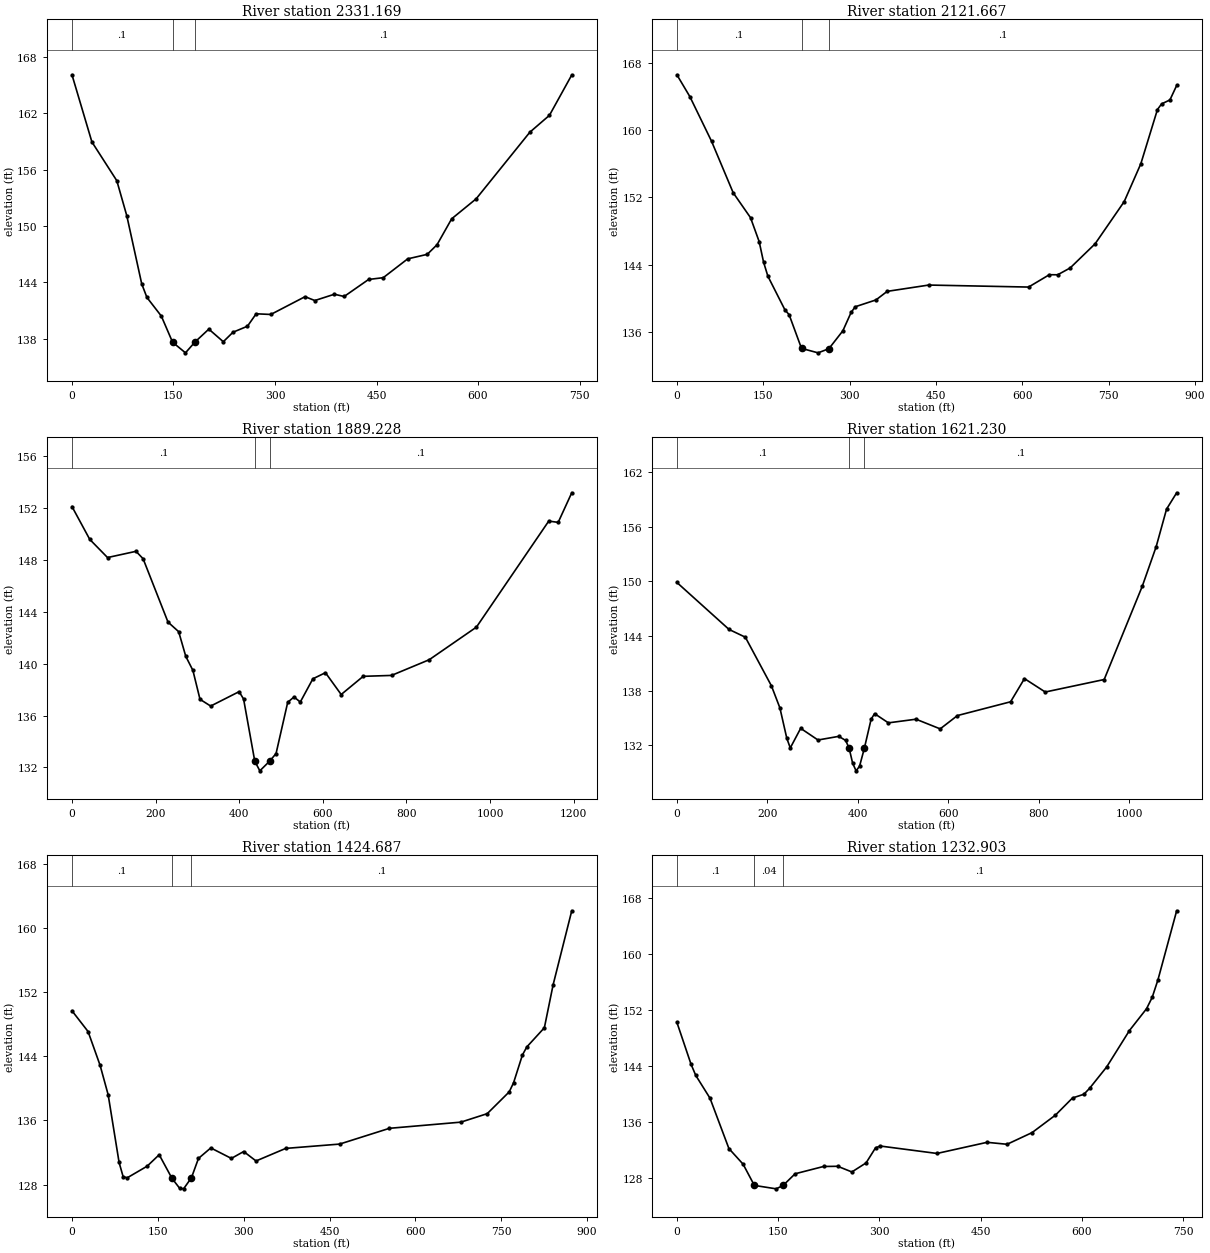
Type RM Length L Ch R = 1 ,2331.169,199.59,209.5,213.44
XS GIS Cut Line= 6
1564414.06975174743394.8917664591564379.73367682743500.189062983
1564374.01099761743535.6696737711564376.30006929743576.872963741
1564361.42110348743652.4123286161564244.67844863744111.371197164
#Sta/Elev= 30
       0  166.08   29.45  158.94   66.26  154.82   80.99   151.1  103.08  143.85
  110.75  142.41  132.03  140.43  148.66  137.65  167.73  136.52  181.75  137.67
  202.23  139.04  223.63   137.7   237.9  138.71  259.31  139.35  272.17  140.67
  293.84   140.6   344.4  142.49  358.85  142.08  387.74  142.75  402.19  142.51
   438.3  144.32  459.97  144.51  496.08  146.51  524.98  146.99  539.42  148.01
  561.09  150.77   597.2  152.89  676.66  159.98  705.55  161.77  738.52  166.06
#Mann= 3 , 0 , 0
       0      .1       0  148.66     .04       0  181.75      .1       0
Bank Sta=148.66,181.75
XS Rating Curve= 0 ,0
Exp/Cntr=0.3,0.1

Type RM Length L Ch R = 1 ,2121.667,214.46,232.44,248.98
XS GIS Cut Line= 4
1564246.71702087743326.7956308871564183.22340333743488.103740215
1564140.32231045743675.1525052931564016.76716287744162.508920744
#Sta/Elev= 30
       0  166.57   22.57  163.97   60.18  158.67    97.8  152.54  127.89  149.58
  142.93  146.73  150.46  144.32  157.98  142.63  187.72  138.61   194.9  138.05
  216.44  134.04  245.17  133.51  263.97     134  288.26  136.13  302.63  138.32
  309.81  138.99  345.72   139.8  365.26  140.82  437.47  141.57  610.79  141.33
   646.9   142.8  661.34  142.79     683   143.6  726.33  146.47  776.88  151.49
  805.77  155.99  834.65  162.44  841.88  163.11  856.32  163.58  868.03   165.3
#Mann= 3 , 0 , 0
       0      .1       0  216.44     .04       0  263.97      .1       0
Bank Sta=216.44,263.97
XS Rating Curve= 0 ,0
Exp/Cntr=0.3,0.1

Type RM Length L Ch R = 1 ,1889.228,273.98,268,266.42
XS GIS Cut Line= 4
 1564198.6359262743111.9167928251563965.28474005743449.704873517
1563926.12090459743531.2961973551563671.55597422 744177.49948214
#Sta/Elev= 30
       0   152.1   42.54  149.57   85.08  148.17  153.14  148.65  170.16  148.08
  229.71   143.2  255.24  142.46  272.25  140.56  289.27  139.48  306.28  137.25
  331.81  136.73  399.87  137.84  410.55  137.27  437.27  132.49  449.38  131.74
  472.67  132.48   488.2  133.07   516.1  137.02  531.15  137.43   546.2  137.04
  576.29  138.83  606.39   139.3     644  137.62  696.67  139.02  764.38  139.09
  854.66   140.3  967.52  142.81 1140.56  150.98 1163.13  150.88 1195.59  153.16
#Mann= 3 , 0 , 0
       0      .1       0  437.27     .04       0  472.67      .1       0
Bank Sta=437.27,472.67
XS Rating Curve= 0 ,0
Exp/Cntr=0.3,0.1

Type RM Length L Ch R = 1 ,1621.230,218.32,196.54,168.2
XS GIS Cut Line= 5
1563839.63410135742979.7388482091563787.41565406743193.508116663
1563705.82433023743377.904508516 1563594.8601298743632.469438896
1563430.04565567744002.894049108
#Sta/Elev= 30
       0  149.87  115.29  144.72  151.32  143.87  208.97  138.54  227.71  136.12
  243.02  132.78  250.67  131.73  273.64  133.88  311.91   132.6  357.84     133
  373.15  132.55   380.8  131.69  388.46  130.07  396.11  129.22  403.77  129.72
  414.39  131.69  429.33  134.87  436.97  135.49  467.51  134.48   528.6  134.88
  582.05  133.82  620.23  135.28   737.7  136.79  768.35  139.33  814.32  137.86
  944.57  139.23 1028.84  149.46 1059.49  153.79 1082.47  157.91 1104.83   159.7
#Mann= 3 , 0 , 0
       0      .1       0   380.8     .04       0  414.39      .1       0
Bank Sta=380.8,414.39
XS Rating Curve= 0 ,0
Exp/Cntr=0.3,0.1

Type RM Length L Ch R = 1 ,1424.687,191.82,191.78,171.06
XS GIS Cut Line= 6
1563532.85072371743095.5985280571563539.37802961743170.662545994
1563536.11437666743262.0448286681563495.31871475743464.391311795
1563441.46844099 743663.474141971563320.71328172743931.093684152
#Sta/Elev= 30
       0   149.7   28.11  147.11   49.18  142.88   63.24  139.21   82.35  130.75
   89.36  128.99   96.36  128.83  131.38  130.29   152.4  131.72  174.74  128.77
  187.94  127.55  194.99  127.46   208.8  128.85  221.03  131.26  242.58  132.57
   278.5  131.26  300.06  132.12  321.61  130.94  373.43  132.51   467.7  133.05
  554.72  135.02   679.5  135.79  725.58  136.85  763.98  139.57  771.66  140.72
  787.02  144.17   794.7  145.18  825.42  147.58  840.78  152.97  873.27  162.19
#Mann= 3 , 0 , 0
       0      .1       0  174.74     .04       0   208.8      .1       0
Bank Sta=174.74,208.8
XS Rating Curve= 0 ,0
Exp/Cntr=0.3,0.1

Type RM Length L Ch R = 1 ,1232.903,147.89,152.91,173.36
XS GIS Cut Line= 4
1563350.96394707743141.209482551 1563335.4978075743452.066822171
1563258.27584027743671.7204178721563148.44904239743834.744570926
#Sta/Elev= 30
       0  150.27   21.03  144.27   28.03  142.68   49.06  139.44    77.1  132.25
   98.12  130.02   114.8  126.99  147.18   126.5  157.45  126.99  175.22  128.65
  217.27  129.69  238.29  129.72  259.32  128.91  280.35   130.2  294.36  132.35
  301.37  132.61  385.44  131.55  459.64  133.14  489.32  132.86  526.42  134.53
  560.95  137.02  586.28  139.47  603.16     140   611.6  140.85  636.92   143.9
  670.68   149.1     696  152.21  704.44  153.85  712.88  156.33  740.64  166.19
#Mann= 3 , 0 , 0
       0      .1       0   114.8     .04       0  157.45      .1       0
Bank Sta=114.8,157.45
XS Rating Curve= 0 ,0
Exp/Cntr=0.3,0.1