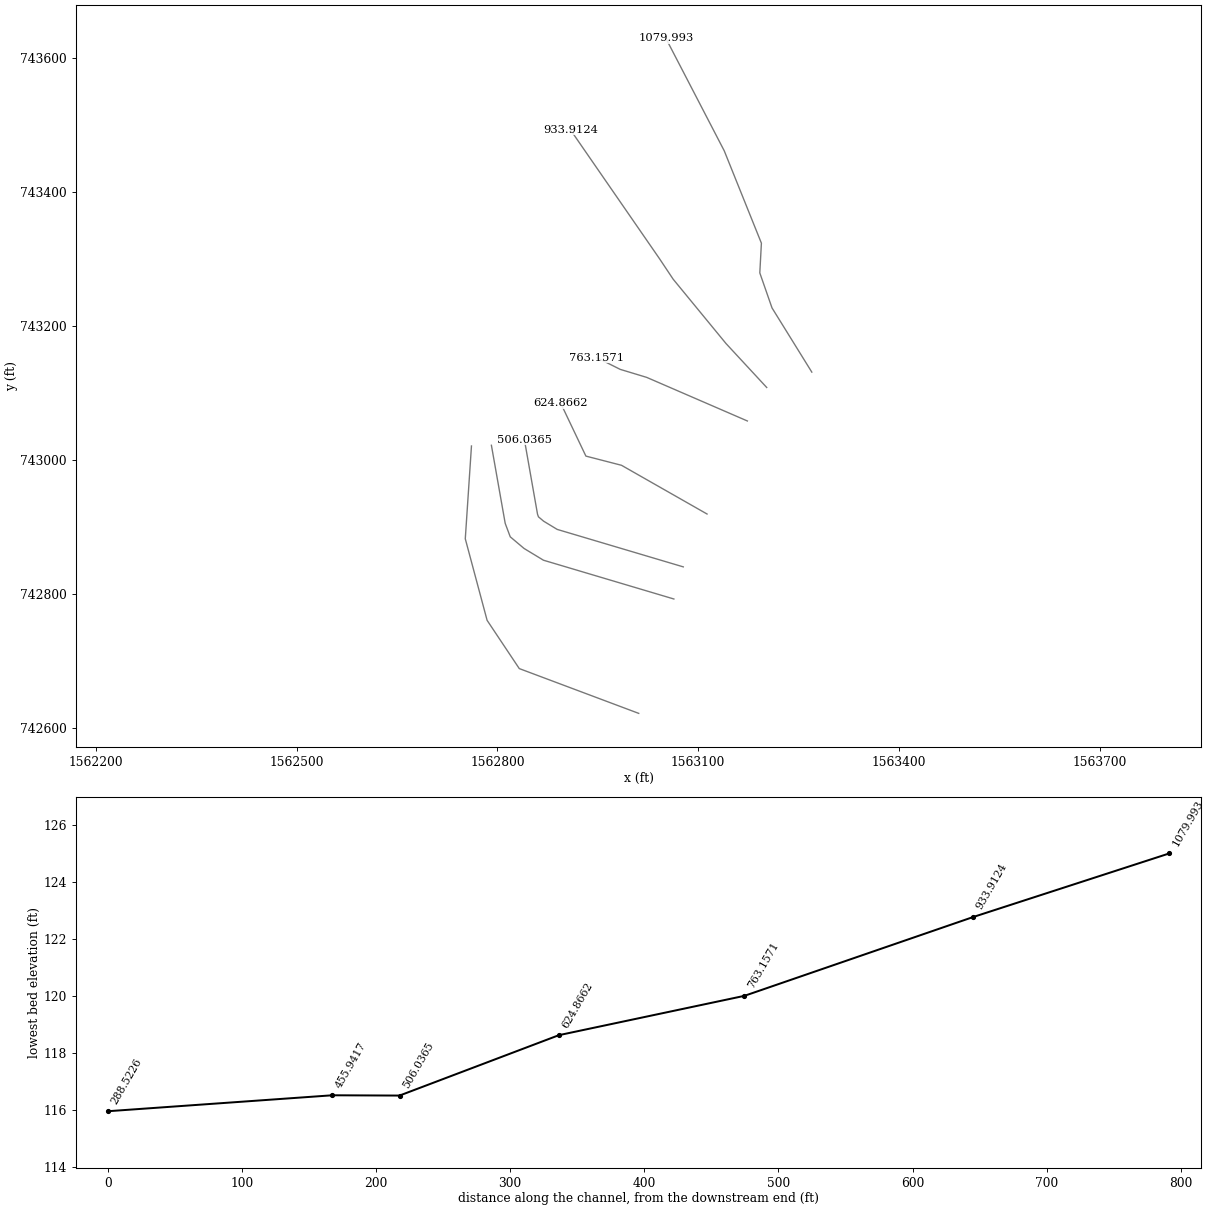
HEC-RAS study StoneRun.prj: StoneRun

--- StoneRun.g01 (geometry) --- (continued)

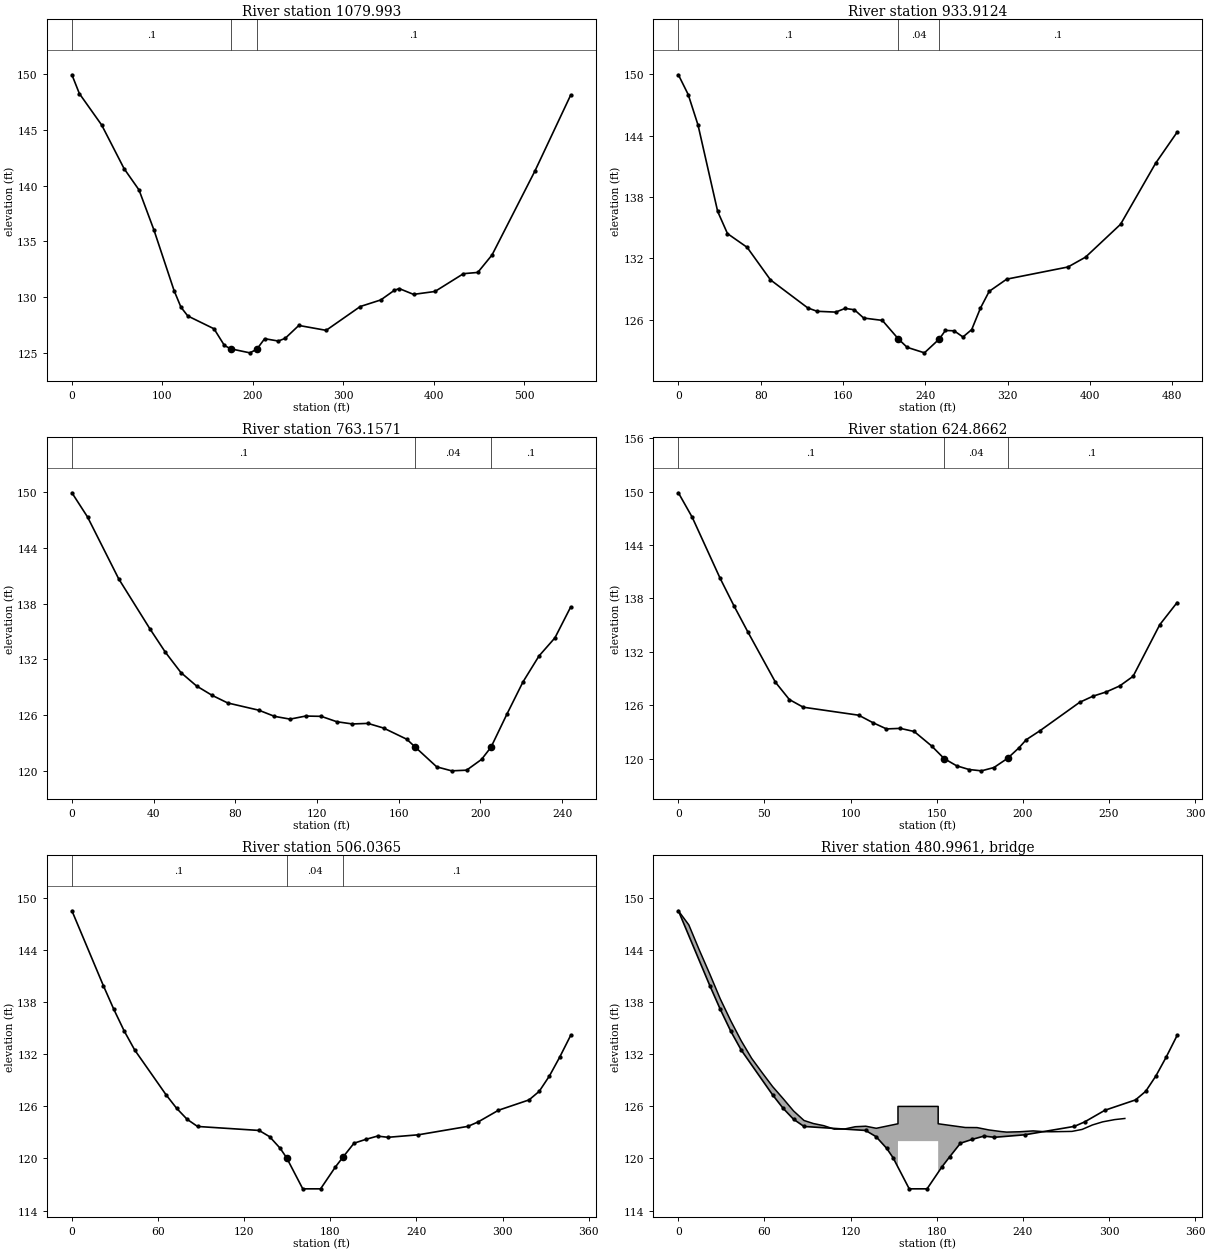
Type RM Length L Ch R = 1 ,1079.993,107.53,146.08,165.31
XS GIS Cut Line= 6
1563269.77650072 743131.363915891563210.31349349743227.297567591
1563192.07817128743279.6250139621563194.45669158 743324.02405937
 1563138.9578848743461.9782361981563051.74547419743630.060336664
#Sta/Elev= 30
       0  149.97    8.24  148.28   32.94  145.45   57.65  141.54   74.12  139.63
   90.59  136.04  112.87  130.59  120.46   129.1  128.04  128.31  156.99  127.16
  168.49  125.66   175.5  125.36  196.53     125  204.15  125.31  212.95  126.27
  228.04  126.06  235.59   126.3  250.68  127.46  280.86  127.02  318.58  129.16
  341.22  129.75  356.31  130.62  361.65  130.77  377.42  130.25  401.08  130.51
  432.63  132.11   448.4  132.22  464.17  133.79  511.49  141.32  551.01  148.14
#Mann= 3 , 0 , 0
       0      .1       0   175.5     .04       0  204.15      .1       0
Bank Sta=175.5,204.15
XS Rating Curve= 0 ,0
Exp/Cntr=0.3,0.1

Type RM Length L Ch R = 1 ,933.9124,122.43,170.76,207.56
XS GIS Cut Line= 5
1563202.38584302743108.4198320061563141.58486755743174.067740142
1563062.64685662 743270.166188241563042.05433197743301.054975137
1562909.25234461743493.272594422
#Sta/Elev= 30
       0  149.94    9.54  148.01   19.08  145.03   38.16  136.59   47.71  134.42
   66.79  133.08   89.48   129.9  125.71  127.16  134.77  126.83  152.89  126.75
  161.95  127.11  171.01  126.98  180.07  126.17  198.18  125.94  213.84  124.12
  222.25  123.31  239.08  122.77   253.5  124.12  259.47  124.96  267.98  124.92
  276.49  124.32     285  125.04  293.51  127.14  302.01  128.78  319.03  129.97
  378.59  131.16   395.6  132.12  429.64  135.33  463.67  141.29   484.6  144.33
#Mann= 3 , 0 , 0
       0      .1       0  213.84     .04       0   253.5      .1       0
Bank Sta=213.84,253.5
XS Rating Curve= 0 ,0
Exp/Cntr=0.3,0.1

Type RM Length L Ch R = 1 ,763.1571,140.39,138.29,132.65
XS GIS Cut Line= 4
1563173.48872285743058.3835552191563023.02078521743123.525162369
1562983.56882599743135.4524988831562948.70430383743152.884759963
#Sta/Elev= 30
       0  149.95    7.63  147.35   22.88  140.69   38.14  135.31   45.77  132.77
   53.39  130.58   61.02  129.14   68.65  128.13   76.28  127.31   91.53  126.53
   99.16  125.87  106.79  125.57  114.42   125.9  122.05  125.87  129.67  125.29
   137.3  125.05  144.93  125.11  152.56  124.61  163.96   123.4  167.92  122.59
  178.59  120.43   185.9     120  193.22  120.07  200.53  121.23  205.18  122.55
  213.01  126.13  220.83  129.58  228.66  132.37  236.48  134.33  244.16  137.64
#Mann= 3 , 0 , 0
       0      .1       0  167.92     .04       0  205.18      .1       0
Bank Sta=167.92,205.18
XS Rating Curve= 0 ,0
Exp/Cntr=0.3,0.1

Type RM Length L Ch R = 1 ,624.8662,113.35,118.83,105.94
XS GIS Cut Line= 4
1563113.23898058742919.367003068 1562985.4248894742992.167106196
1562932.22753416743005.8954559421562894.57254578743084.990690529
#Sta/Elev= 30
       0  149.86    8.06   147.1   24.17  140.28   32.22  137.18   40.28  134.25
   56.39  128.57   64.45  126.63    72.5  125.77  104.73  124.87  112.78  124.05
  120.84  123.33  128.89  123.39  136.95  123.04  147.09  121.41  154.32     120
  161.55  119.19  168.78  118.77  176.01  118.62  183.24  118.99  191.13  120.02
   197.7  121.19  202.03  122.12  209.79   123.1  233.04  126.32   240.8  127.01
  248.55  127.49   256.3  128.16  264.06  129.24  279.56  135.04  289.63  137.53
#Mann= 3 , 0 , 0
       0      .1       0  154.32     .04       0  191.13      .1       0
Bank Sta=154.32,191.13
XS Rating Curve= 0 ,0
Exp/Cntr=0.5,0.3

Type RM Length L Ch R = 1 ,506.0365,50.74,50.1,57.68
BEGIN DESCRIPTION:
Center of channel lowered 1.0 ft based on bridge survey info.
END DESCRIPTION:
XS GIS Cut Line= 6
1563077.73423174742840.3813607391562889.34417446742896.370759904
1562869.10668992742908.6359020471562861.43094644742915.099686041
1562860.00905649742918.8913925291562840.36681816743030.362320513
#Sta/Elev= 30
       0  148.55   21.88  139.93   29.17   137.2   36.47  134.68   43.76   132.5
   65.64  127.33   72.93  125.79   80.23  124.52   87.52  123.69  130.44  123.23
  137.75  122.51  145.07  121.18  149.59  120.08  160.84   116.5  173.26   116.5
  183.61  119.03  188.93  120.17  196.54  121.76  204.72   122.2  212.91  122.58
   220.2  122.44  241.41  122.73   275.9   123.7     283  124.21   297.2  125.56
  318.49  126.75  325.59  127.74  332.69  129.51  339.79  131.66  347.48  134.18
#Mann= 3 , 0 , 0
       0      .1       0  149.59     .04       0  188.93      .1       0
Bank Sta=149.59,188.93
XS Rating Curve= 0 ,0
Exp/Cntr=0.5,0.3

Type RM Length L Ch R = 3 ,480.9961,,,
BEGIN DESCRIPTION:
Horse Shoe Road, MDE Bridge #: CE042407PF-2
Top of road obtained from DEM.
Opening from MDE2 bridge/culvert surveys.
END DESCRIPTION:
Bridge Culvert--1,0,-1,-1, 0
Deck Dist Width WeirC Skew NumUp NumDn MinLoCord MaxHiCord MaxSubmerge Is_Ogee
12,26,2.6,0, 40, 37, , , 0.98, 0, 2,2,,
       0    7.29   14.59   21.88   29.17   36.47   43.76   51.05   58.35   65.64
   72.93   80.23   87.52   93.99   101.3  108.61  115.92  123.23  130.55  137.86
     153     153     181     181  199.91  208.09  216.28  224.46  228.68  237.83
   247.2  254.68  259.95  267.07   274.2  281.32  288.44  295.57  303.96  311.06
  148.55  146.92  144.02  141.26   138.4  135.88  133.57  131.54  129.89  128.29
  126.91  125.48  124.38  124.03  123.78  123.38   123.4  123.66  123.72  123.48
     124     126     126     124  123.57  123.56  123.29  123.11  123.04  123.08
  123.18  123.09  123.08   123.1  123.12  123.35  123.86  124.22  124.48  124.61
                                                                                
                                                                                
             122     122
                                                                                
       0    7.29   14.59   21.88   29.17   36.47   43.76   51.05   58.35   65.64
   72.93   80.23   87.52   93.99   101.3  108.61  115.92  123.23  130.55  137.86
     153     153     181     181  199.91  208.09  216.28  224.46  228.68  237.83
   247.2  254.68  259.95  267.07   274.2  281.32  306.98
  148.55  146.92  144.02  141.26   138.4  135.88  133.57  131.54  129.89  128.29
  126.91  125.48  124.38  124.03  123.78  123.38   123.4  123.66  123.72  123.48
     124     126     126     124  123.57  123.56  123.29  123.11  123.04  123.08
  123.18  123.09  123.08   123.1  123.12  123.35   123.6
                                                                                
                                                                                
             122     122
                                                        
BR Coef=-1 , 0 , 0 ,, 0 ,,,0.8,0,,0,
WSPro=,,,, 1 ,,,, 0 ,,,, 0 ,,,,-1 ,-1 ,-1 , 0 , 0 , 0 , 0 , 0
BC Design=,, 0 ,, 0 ,,,,,,
BC Use User HTab Curves=0
BC User HTab FreeFlow(D)= 0

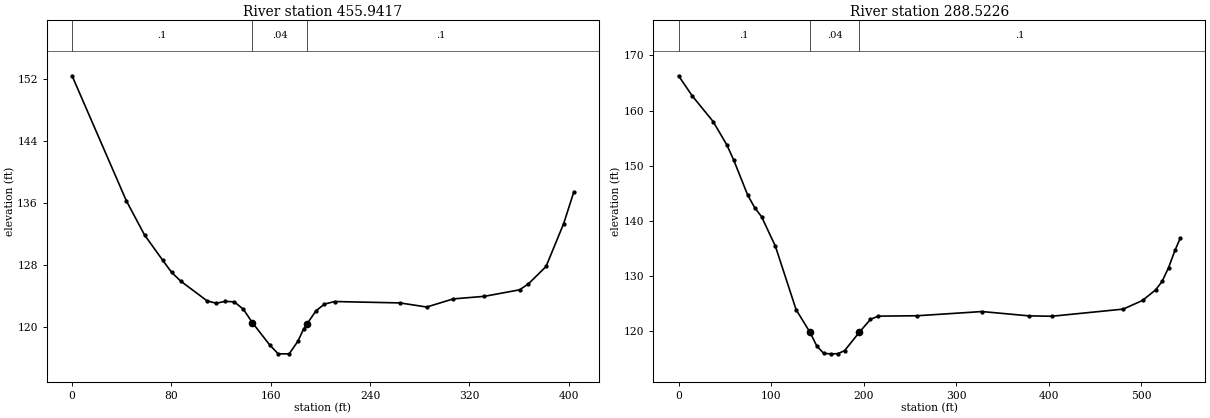
Type RM Length L Ch R = 1 ,455.9417,169.53,167.42,68.68
BEGIN DESCRIPTION:
Center of channel lowered 1.0 ft based on bridge survey info.
END DESCRIPTION:
XS GIS Cut Line= 6
1563063.69557332742792.3926530031562868.84680003742850.327406853
1562839.87043905742867.8888377851562819.21093823742885.286312178
1562811.68485621742905.3558641821562791.06122097743022.058219954
#Sta/Elev= 30
       0  152.39   43.76  136.24   58.35  131.85   72.93   128.6   80.23  127.01
   87.52  125.89  108.71  123.35  116.03  123.04  123.34  123.28  130.65  123.22
  137.96  122.26  145.27  120.52  159.26  117.64     166  116.51  174.85  116.51
  181.85  118.13  186.42   119.7  189.14  120.36  196.45  122.06  203.28  122.93
  211.47  123.26  264.17  123.08  285.61  122.55  306.98   123.6  332.03  123.93
  360.42  124.77  367.52  125.54  381.72  127.78  395.92  133.32  404.12  137.42
#Mann= 3 , 0 , 0
       0      .1       0  145.27     .04       0  189.14      .1       0
Bank Sta=145.27,189.14
XS Rating Curve= 0 ,0
Exp/Cntr=0.5,0.3

Type RM Length L Ch R = 1 ,288.5226,317.86,288.52,170.65
XS GIS Cut Line= 5
1563011.16554509742621.5016634611562832.69699863742688.427368417
1562784.64777455742760.5012045061562752.04294395742882.340308368
1562761.28052369743020.990619957
#Sta/Elev= 30
       0  166.32   14.95  162.65   37.38  158.03   52.33  153.76   59.81  150.98
   74.76   144.7   82.24  142.45   89.71   140.8  104.66  135.45  127.09  123.94
  142.04  119.86  149.52  117.34     157  116.02  164.47  115.95  171.95  115.97
  179.42  116.52  195.35  119.85  207.43   122.2  215.84  122.78  257.91  122.85
  327.95  123.61  378.67  122.83  403.35  122.76  480.52  124.05  501.57  125.63
   515.6  127.54  522.62  129.07  529.63  131.58  536.65  134.75  542.31  136.93
#Mann= 3 , 0 , 0
       0      .1       0  142.04     .04       0  195.35      .1       0
Bank Sta=142.04,195.35
XS Rating Curve= 0 ,0
Exp/Cntr=0.3,0.1

Chan Stop Cuts=-1
Use User Specified Reach Order=0
User Specified Reach Order=StoneRun        ,Reach1