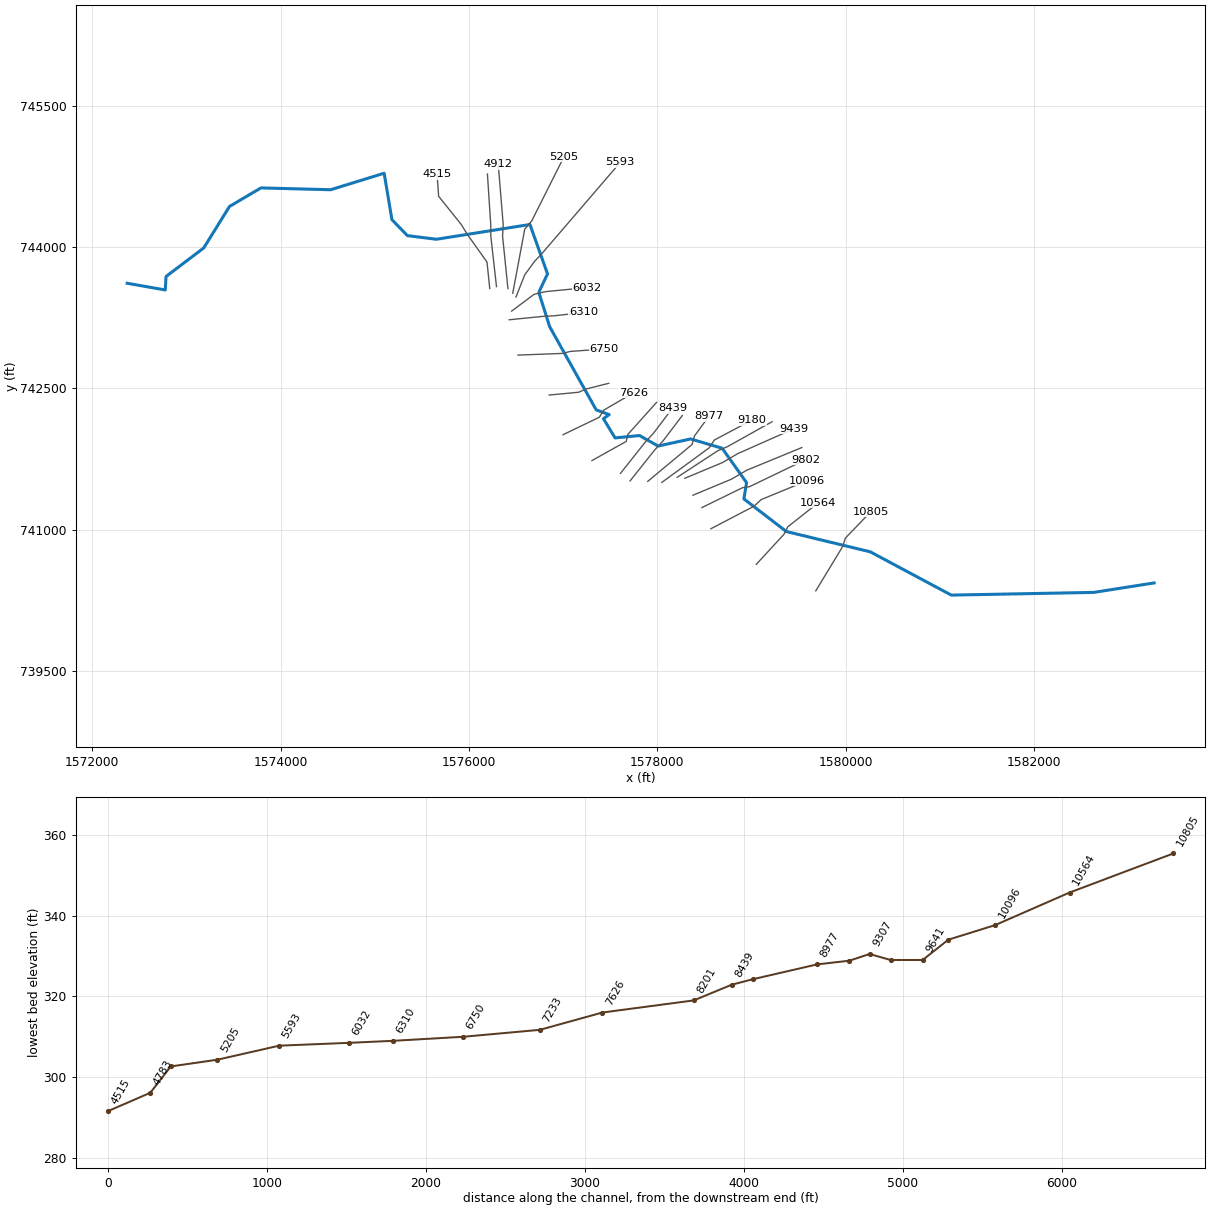
--- StoneRunTrib1.prj (project) ---

Proj Title=StoneRunTrib1
Current Plan=p01
Default Exp/Contr=0.3,0.1
English Units
Geom File=g01
Flow File=f01
Flow File=f02
Plan File=p01
Plan File=p02
Y Axis Title=Elevation
X Axis Title(PF)=Main Channel Distance
X Axis Title(XS)=Station
BEGIN DESCRIPTION:
Stone Run Trib1 - Georeferenced HEC-RAS model.  MD Stateplane.  Horizontal Datum: NAD83.  Vertical Datum: NAVD88.  Units: Feet.  Created by: Jodell Kormanik-Sonterre, USACE - St. Paul District as part of FEMA Map Modernization study for Cecil County, MD.
END DESCRIPTION:
DSS Export Rating Curves= 0
DSS Export Rating Curve Sorted= 0
DSS Export Volume Flow Curves= 0
DXF OffsetX= 0
DXF OffsetY= 0
DXF ScaleX= 1
DXF ScaleY= 10

--- StoneRunTrib1.p01 (plan) ---

Plan Title=Stone Run Trib 1 Frequency Profiles
Program Version=4.00
Short Identifier=freq
Geom File=g01
Flow File=f01
Subcritical Flow
K Sum by GR= 0
Std Step Tol= 0.01
Critical Tol= 0.01
Num of Std Step Trials= 20
Max Error Tol= 0.3
Flow Tol Ratio= 0.001
Split Flow NTrial= 30
Split Flow Tol= 0.02
Split Flow Ratio= 0.02
Log Output Level= 0
Friction Slope Method= 1
Unsteady Friction Slope Method= 2
Unsteady Bridges Friction Slope Method= 1
Parabolic Critical Depth
Global Vel Dist= 0 , 0 , 0
Global Log Level= 0
CheckData=True
Encroach Param=-1 ,0,0, 0
Computation Interval=1HOUR
Output Interval=1HOUR
Run HTab= 0
Run UNet= 0
Run PostProcess= 0
Run WQNet= 0
UNET Theta= 1
UNET Theta Warmup= 1
UNET ZTol= 0.02
UNET ZSATol= 0.05
UNET MxIter= 20
UNET MaxInSteps= 0
UNET DtIC= 0
UNET DtMin= 0
UNET MaxCRTS= 20
UNET WFStab= 2
UNET SFStab= 1
UNET WFX= 1
UNET SFX= 1
UNET DSS MLevel= 4
UNET DZMax Abort= 100
UNET Convert EG Bridges= 0
UNET Use Existing IB Tables=-1
UNET Froude Reduction=False
UNET Froude Limit= 1
UNET Froude Power= 10
UNET Time Slicing=0,0, 5
Instantaneous Interval=1HOUR
Write IC File= 0
Echo Input=False
Echo Output=False
Write Detailed= 0
Detailed Automatic Start=False, 10
WQ ULTIMATE=-1
WQ Max Comp Step=1HOUR
WQ Output Interval=15MIN
WQ Output Selected Increments= 0
WQ Output face flow=0
WQ Output face velocity=0
WQ Output face area=0
WQ Output face dispersion=0
WQ Output cell volume=0
WQ Output cell surface area=0
WQ Output cell continuity=0
WQ Output face conc=0
WQ Output face dconc_dx=0
WQ Output face courant=0
WQ Output face peclet=0
WQ Output face adv mass=0
WQ Output face disp mass=0
WQ Output cell mass=0
WQ Output cell source sink temp=0
WQ Output cell source sink nsm=0
WQ Output MaxMinRange=-1
WQ Daily Max Min Mean=-1
WQ Daily Range=0
WQ Daily Time=0
WQ Create Restart=0
WQ Fixed Restart=0
WQ System Summary=False
Sorting and Armoring Iterations= 10
XS Update Threshold= 0.02
Hydraulics Update Threshold= 0.02
Energy Slope Method= 1
Volume Change Method= 0
XS Weighting Method= 0
Number of US Weighted Cross Sections= 1
Number of DS Weighted Cross Sections= 1
Upstream XS Weight=0.25
Main XS Weight=0.5
Downstream XS Weight=0.25
Number of DS XS's Weighted with US Boundary= 1
Upstream Boundary Weight= 1
Weight of XSs Associated with US Boundary= 0
Number of US XS's Weighted with DS Boundary= 1
Downstream Boundary Weight= 0.5
Weight of XSs Associated with DS Boundary= 0.5
Sediment Output Level= 4
Mass or Volume Output= 0
Output Increment Type= 1
Profile and TS Output Increment= 10
XS Output Flag= 0
XS Output Increment= 10
Disregard all LS=0
Disregard all Conn=0
Disregard all Breaches=0
Disregard all Pumps=0

--- StoneRunTrib1.p02 (plan) ---

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Plan Title=Stone Run Trib 1 Floodway
Short Identifier=floodway
Geom File=g01
Flow File=f02
Encroach Param=-1 ,0,0, 2
Encroach River=StoneRunTrib1
Encroach Reach=Reach1
Encroach Node=10805
       1  587.54  609.59
Encroach Node=10564
       1     455     504
Encroach Node=10096
       1     547  577.95
Encroach Node=9802
       1     460     560
Encroach Node=9641
       1     460     585
Encroach Node=9439
       1     440  547.45
Encroach Node=9307
       1     530  600.81
Encroach Node=9180
       1     640     710
Encroach Node=8977
       1  643.09     710
Encroach Node=8575
       1  460.69  570.55
Encroach Node=8439
       1  425.48  501.75
Encroach Node=8201
       1  399.01  465.22
Encroach Node=7626
       1     440     540
Encroach Node=7233
       1     310     450
Encroach Node=6750
       1     465     560
Encroach Node=6310
       1     290     480
Encroach Node=6032
       1     300     480
Encroach Node=5593
       1     361     705
Encroach Node=5205
       1     700     850
Encroach Node=4912
       1     570     660
Encroach Node=4783
       1     525     650
Encroach Node=4515
       1     575     750
Encroach Node=4419
       1     575     750
Encroach Node=4255
       1     400     575
Encroach Node=4139
       1  365.59     575
Encroach Node=3998
       1     450     605
Encroach Node=3874
       1     465     580
Encroach Node=3583
       1  337.03  649.81
Encroach Node=3233
       1     285     615
Encroach Node=2994
       1     415     660
Encroach Node=2704
       1     465     595
Encroach Node=2373
       1     385     495
Encroach Node=1912
       1     560     610
Encroach Node=1334
       1     460     575
Encroach Node=897
       1     540     680
Encroach Node=424
       1     485     685
Encroach Node=-141
       1     560     750

--- StoneRunTrib1.f01 (steady flow) ---

Flow Title=Stone Run Trib 1 Frequency Flows
Program Version=4.00
Number of Profiles= 5
Profile Names=10yr,50yr,100yr,500yr,100ult
River Rch & RM=StoneRunTrib1,Reach1          ,10805
     252     553     750    1450     906
River Rch & RM=StoneRunTrib1,Reach1          ,9802
     689    1460    1950    3640    2370
River Rch & RM=StoneRunTrib1,Reach1          ,6750
     806    1700    2270    4220    2660
River Rch & RM=StoneRunTrib1,Reach1          ,5205
    1190    2430    3200    5800    4430
River Rch & RM=StoneRunTrib1,Reach1          ,424
    1260    2580    3390    6140    4730
River Rch & RM=StoneRunTrib1,Reach1          ,-141
    1600    3250    4270    7670    5740
Boundary for River Rch & Prof#=StoneRunTrib1,Reach1          , 1
Up Type= 0
Dn Type= 3
Dn Slope=0.005
DSS Import GetInterval= 0
DSS Import GetPeak= 0
DSS Import FillOption= 0

--- StoneRunTrib1.f02 (steady flow) ---

Flow Title=Stone Run Trib 1 Floodway Flows
Program Version=4.00
Number of Profiles= 2
Profile Names=100yr,100fldwy
River Rch & RM=StoneRunTrib1,Reach1          ,10805
     750     750
River Rch & RM=StoneRunTrib1,Reach1          ,9802
    1950    1950
River Rch & RM=StoneRunTrib1,Reach1          ,6750
    2270    2270
River Rch & RM=StoneRunTrib1,Reach1          ,5205
    3200    3200
River Rch & RM=StoneRunTrib1,Reach1          ,424
    3390    3390
River Rch & RM=StoneRunTrib1,Reach1          ,-141
    4270    4270
Boundary for River Rch & Prof#=StoneRunTrib1,Reach1          , 1
Up Type= 0
Dn Type= 3
Dn Slope=0.005
Boundary for River Rch & Prof#=StoneRunTrib1,Reach1          , 2
Up Type= 0
Dn Type= 1
Dn Known WS=272.86
DSS Import GetInterval= 0
DSS Import GetPeak= 0
DSS Import FillOption= 0

--- StoneRunTrib1.g01 (geometry) ---

Geom Title=Stone Run Trib 1 Geometry
Program Version=4.00

River Reach=StoneRunTrib1   ,Reach1
Reach XY= 30
1583273.60552369740433.8073868161582633.19706269740333.230416968
1581120.43733269 740304.494139881580260.40161106740764.274573416
1579369.57702106740979.7966516171578918.00695243741326.684568003
1578946.74322952741499.1022305641578688.11673568741864.463467941
1578352.76802905741963.5342798381578007.72197296 741888.40328376
1577810.15527955741999.7084631321577550.44319433741974.664797768
1577427.07995385742178.7242932921577488.29780252742222.318821892
1577350.09387146742272.4061526361576856.71115397743154.589306861
1576740.45169254743521.6480163631576833.17622508743717.175834998
1576646.71928465744242.278894231 1575653.4916466744085.333097026
1575345.63613336744123.8150361781575181.12584342744293.135568485
1575098.38967426744786.6664382221574530.78107168744611.573615044
1573790.00374286744630.8145846131573456.17292064744433.594646424
1573182.95115258743992.9764430521572782.73898536743689.931172162
1572774.08054905 743546.585948811572369.46980819743617.888713524

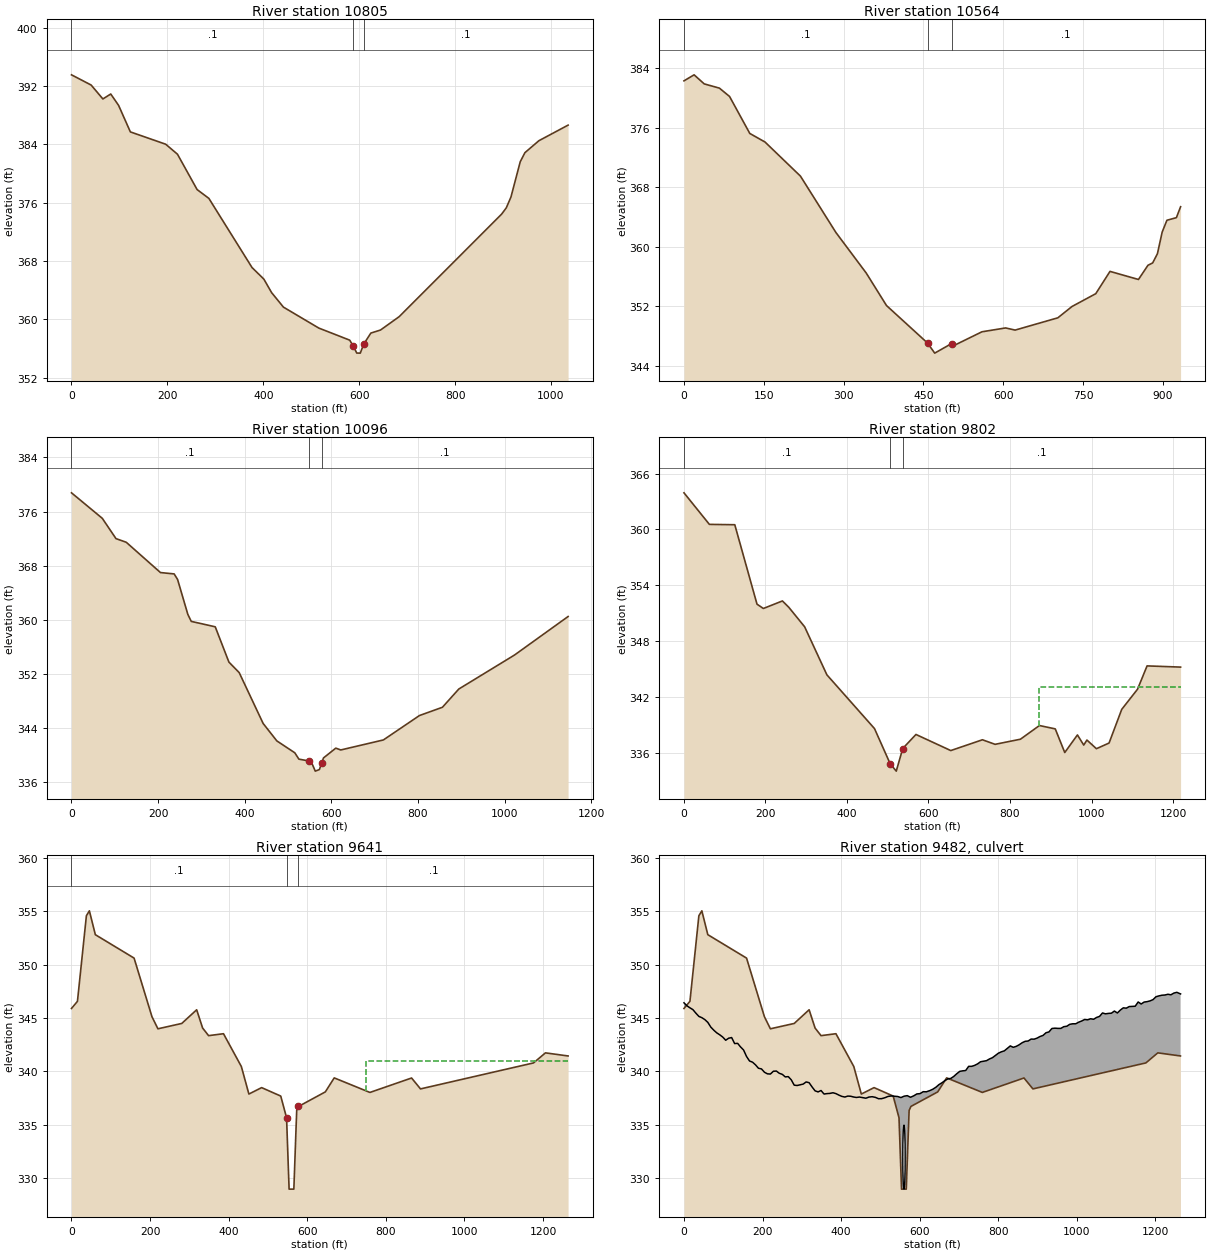
Type RM Length L Ch R = 1 ,10805   ,633.52,653.76,615.32
XS GIS Cut Line= 4
1579681.51297623740349.4490907491579966.98997152740820.486132964
1579995.53767104740909.6976939891580266.74081655741191.606226847
#Sta/Elev= 30
       0  393.55   40.93  392.15   65.48  390.24   81.85  390.92   98.22  389.36
  122.78  385.72  196.45  384.03     221  382.66  261.93  377.81  286.48   376.6
  376.52  367.11  401.08  365.53  417.45  363.66     442  361.68  515.67  358.81
  580.19  357.15  587.54  356.35  594.89  355.38  602.24  355.37  609.59  356.62
  624.29  358.12  644.46  358.54  683.31  360.37  897.01  374.44  906.72   375.3
  916.44  376.78  935.86  381.63  945.58  382.87  974.72  384.51 1035.64  386.65
#Mann= 3 , 0 , 0
       0      .1       0  587.54    .035       0  609.59      .1       0
Bank Sta=587.54,609.59
XS Rating Curve= 0 ,0
Exp/Cntr=0.3,0.1

Type RM Length L Ch R = 1 ,10564   ,441.77,468.61,415.2
XS GIS Cut Line= 4
1579049.89512417740631.3576235771579342.50904432740948.950780854
1579385.33059365   741031.0254171579706.49221332741284.386250317
#Sta/Elev= 30
       0  382.32   19.04  383.13   38.07  381.91   66.63  381.34   85.66  380.22
  123.74  375.24  152.29  374.09  218.92   369.5  285.54  361.92  342.65  356.45
  380.73  352.08  457.78  347.04  471.32  345.68   502.9  346.96   510.8  346.82
  560.08  348.55  604.66  349.07  622.49  348.78  702.74  350.43  729.49  351.96
  774.07  353.68  800.81  356.68  854.31  355.59  872.14   357.5  881.06  357.82
  889.97  359.06  898.89  361.97  907.81  363.56  925.64  363.91  933.49  365.38
#Mann= 3 , 0 , 0
       0      .1       0  457.78    .035       0   502.9      .1       0
Bank Sta=457.78,502.9
XS Rating Curve= 0 ,0
Exp/Cntr=0.3,0.1

Type RM Length L Ch R = 1 ,10096   ,247.65,293.92,189.15
XS GIS Cut Line= 4
1578568.15269461741009.6146423371579024.91588707741248.701625898
1579103.42206079741320.0708747211579588.73295277741519.904771417
#Sta/Elev= 30
       0  378.77   71.11     375  102.71     372  126.42  371.46  205.43  366.98
  237.03  366.78  244.93  365.96  268.63  360.79  276.53  359.76  331.84  358.96
  363.44  353.74  387.15  352.19  442.45  344.67  474.06  342.09  515.55  340.33
  525.01  339.39  547.79  339.13  553.39  339.01  562.85  337.62  572.31  337.85
  577.95  338.87  581.77  339.57  610.16  341.02  621.65  340.75  720.06  342.23
  803.34  345.84  856.33  347.06  894.18  349.76 1022.87  354.79 1146.49  360.48
#Mann= 3 , 0 , 0
       0      .1       0  547.79    .035       0  577.95      .1       0
Bank Sta=547.79,577.95
XS Rating Curve= 0 ,0
Exp/Cntr=0.3,0.1

Type RM Length L Ch R = 1 ,9802    ,138.84,161.16,177.24
XS GIS Cut Line= 4
1578473.44087665741235.0311808141578903.22642474741445.272596106
1578977.64816467741456.4358570721579576.74317108741744.820099309
#Sta/Elev= 30
       0  363.93   62.34  360.54  124.68   360.5  179.23  351.96  194.82   351.5
  241.57  352.31  257.16  351.63  296.12  349.53  350.67  344.37  467.56  338.59
  506.08   334.8  520.92  334.02  536.79  336.45  569.24  337.96   654.7  336.23
  732.39  337.39  763.46   336.9  825.62  337.45  872.23  338.92  911.07  338.56
  934.38  336.02  965.45  337.91  980.99  336.82  988.76  337.36 1012.07  336.43
 1043.14  337.04 1074.22  340.66 1113.06  342.83 1136.37  345.33  1218.6   345.2
#Mann= 3 , 0 , 0
       0      .1       0  506.08    .035       0  536.79      .1       0
#XS Ineff= 2 , 0
       0                     870       0   343.1
Permanent Ineff=
       F       F
Bank Sta=506.08,536.79
XS Rating Curve= 0 ,0
Exp/Cntr=0.5,0.3

Type RM Length L Ch R = 1 ,9641    ,206.88,201.57,204.5
BEGIN DESCRIPTION:
Ground elevation lowered to accomodate culvert opening.
END DESCRIPTION:
XS GIS Cut Line= 4
1578377.19791883741365.6504551321578786.34324965741536.322507411
 1578948.1196543741631.0772586911579533.44162759741872.092188865
#Sta/Elev= 30
       0  345.89   15.17  346.56   37.92  354.56   45.51  355.02   60.68  352.79
  159.28   350.6  204.78  345.12  219.95  343.99  280.63  344.49  318.55  345.77
  333.72  344.06  348.89  343.35  386.82  343.53  432.32  340.46  451.43  337.89
  483.88  338.49  532.55   337.7  547.35  335.67  553.78     329  565.87     329
  573.11  336.35  577.68  336.73  645.94  338.09  668.65   339.4  759.49  338.04
  865.48  339.39  888.19  338.37 1175.85   340.8 1206.13  341.74  1263.8  341.45
#Mann= 3 , 0 , 0
       0      .1       0  547.35    .035       0  577.68      .1       0
#XS Ineff= 2 , 0
       0                     750       0  341.01
Permanent Ineff=
       F       F
Bank Sta=547.35,577.68
XS Rating Curve= 0 ,0
Exp/Cntr=0.5,0.3

Type RM Length L Ch R = 2 ,9482    ,,,
BEGIN DESCRIPTION:
E. Main St/Telegraph Rd. MDE Bridge #:
Road Profile taken from DEM
Structure detail from bridge surveys.
Circular Culvert on upstream.....then flows into a trapezoid channel on downstream.
No capability to model that in RAS, therefore modeled circular dimensions.
END DESCRIPTION:
Bridge Culvert--1,0,-1,-1, 0
Deck Dist Width WeirC Skew NumUp NumDn MinLoCord MaxHiCord MaxSubmerge Is_Ogee
15,155,2.6,0, 166, 166, , , 0.98, 0, 0,0,,
       0    7.58   15.17   22.75   30.34   37.92   45.51   53.09   60.68   68.26
   75.85   83.43   91.02    98.6  106.18  113.77  121.35  128.94  136.52  144.11
  151.69  159.28  166.86  174.45  182.03  189.62   197.2  204.78  212.37  219.95
  227.54  235.12  242.71  250.29  257.88  265.46  273.05  280.63  288.22   295.8
  303.38  310.97  318.55  326.14  333.72  341.31  348.89  356.48  364.06  371.65
  379.23  386.82   394.4  401.98  409.57  417.15  424.74  432.32   438.6  446.71
  454.82  462.93  471.05  479.16  487.27  495.38  503.49  511.61  519.72  527.83
  535.94  544.06  552.17  560.28  568.39  576.51  584.62  592.73  600.84  608.96
  617.07  626.24  633.81  641.38  648.95  656.52  664.09  671.66  679.23   686.8
  694.37  701.94  709.51  717.08  724.65  732.22  739.79  747.36  754.93   762.5
  770.07  777.65  785.22  792.79  800.36  807.93   815.5  823.07  830.64  838.21
  845.78  853.35  860.92  868.49  876.06  883.63   891.2  898.77  906.34  913.91
  921.48  929.05  936.62  944.19  951.76  959.33   966.9  974.47  982.04  989.61
  997.18 1004.75 1012.32 1019.89 1027.46 1035.03  1042.6 1050.17 1057.74 1065.31
 1072.88 1080.45 1088.02 1095.59 1103.16 1110.73  1118.3 1125.87 1133.44 1141.01
 1148.58 1156.15 1163.72 1171.29 1178.87 1186.44 1194.01 1201.58 1209.15 1216.72
 1224.29 1231.86 1239.43    1247 1254.57 1264.12
  346.42  346.14  345.95  345.78  345.45  345.15  345.03  344.85  344.59  344.15
  343.86  343.61  343.43  343.22  342.92  343.11  343.17  342.61  342.63  342.29
  342.01   341.4  340.98  340.87  340.62   340.3  340.24  339.93  339.78  339.76
  340.02  340.04  339.83  339.73  339.49  339.52  339.22  338.72  338.69  338.76
  338.82  339.02  338.95  338.55  338.19  338.09  338.22  337.89  337.93  337.95
  338.01  337.93  337.79  337.67  337.61   337.7  337.68  337.61  337.57  337.61
  337.55   337.5  337.61  337.64  337.58  337.45  337.46  337.55  337.67  337.71
  337.69  337.66  337.56  337.69  337.74  337.59  337.72   337.9  337.93  338.11
   338.1  338.22  338.35  338.53  338.77  338.94  339.14  339.31  339.35  339.54
  339.79  340.01  340.06  340.09  340.48  340.48  340.57  340.71  340.91  340.96
  341.01  341.17  341.29   341.5  341.71  341.84  341.93  342.16  342.39  342.26
  342.35   342.5  342.69  342.82  342.85  343.03  343.02  343.12  343.27  343.37
  343.62   343.7  344.02  344.05  344.03  344.03  344.19  344.23  344.41  344.46
  344.46  344.61  344.72  344.86  344.83  344.93  344.88  345.05  345.15  345.47
  345.39  345.43  345.45  345.65  345.47  345.74  345.95  345.92  346.07  346.09
   346.1   346.5  346.31  346.49  346.53   346.6  346.72  346.99  347.07  347.13
  347.15  347.22  347.17  347.33   347.4  347.25
                                                                                
                                                                                
                                                                                
                                                                                
                                                                                
                                                                                
                                                                                
                                                                                
                                                                                
                                                                                
                                                                                
                                                                                
                                                                                
                                                                                
                                                                                
                                                                                
                                                
       0    7.58   15.17   22.75   30.34   37.92   45.51   53.09   60.68   68.26
   75.85   83.43   91.02    98.6  106.18  113.77  121.35  128.94  136.52  144.11
  151.69  159.28  166.86  174.45  182.03  189.62   197.2  204.78  212.37  219.95
  227.54  235.12  242.71  250.29  257.88  265.46  273.05  280.63  288.22   295.8
  303.38  310.97  318.55  326.14  333.72  341.31  348.89  356.48  364.06  371.65
  379.23  386.82   394.4  401.98  409.57  417.15  424.74  432.32   438.6  446.71
  454.82  462.93  471.05  479.16  487.27  495.38  503.49  511.61  519.72  527.83
  535.94  544.06  552.17  560.28  568.39  576.51  584.62  592.73  600.84  608.96
  617.07  626.24  633.81  641.38  648.95  656.52  664.09  671.66  679.23   686.8
  694.37  701.94  709.51  717.08  724.65  732.22  739.79  747.36  754.93   762.5
  770.07  777.65  785.22  792.79  800.36  807.93   815.5  823.07  830.64  838.21
  845.78  853.35  860.92  868.49  876.06  883.63   891.2  898.77  906.34  913.91
  921.48  929.05  936.62  944.19  951.76  959.33   966.9  974.47  982.04  989.61
  997.18 1004.75 1012.32 1019.89 1027.46 1035.03  1042.6 1050.17 1057.74 1065.31
 1072.88 1080.45 1088.02 1095.59 1103.16 1110.73  1118.3 1125.87 1133.44 1141.01
 1148.58 1156.15 1163.72 1171.29 1178.87 1186.44 1194.01 1201.58 1209.15 1216.72
 1224.29 1231.86 1239.43    1247 1254.57 1264.12
  346.42  346.14  345.95  345.78  345.45  345.15  345.03  344.85  344.59  344.15
  343.86  343.61  343.43  343.22  342.92  343.11  343.17  342.61  342.63  342.29
  342.01   341.4  340.98  340.87  340.62   340.3  340.24  339.93  339.78  339.76
  340.02  340.04  339.83  339.73  339.49  339.52  339.22  338.72  338.69  338.76
  338.82  339.02  338.95  338.55  338.19  338.09  338.22  337.89  337.93  337.95
  338.01  337.93  337.79  337.67  337.61   337.7  337.68  337.61  337.57  337.61
  337.55   337.5  337.61  337.64  337.58  337.45  337.46  337.55  337.67  337.71
  337.69  337.66  337.56  337.69  337.74  337.59  337.72   337.9  337.93  338.11
   338.1  338.22  338.35  338.53  338.77  338.94  339.14  339.31  339.35  339.54
  339.79  340.01  340.06  340.09  340.48  340.48  340.57  340.71  340.91  340.96
  341.01  341.17  341.29   341.5  341.71  341.84  341.93  342.16  342.39  342.26
  342.35   342.5  342.69  342.82  342.85  343.03  343.02  343.12  343.27  343.37
  343.62   343.7  344.02  344.05  344.03  344.03  344.19  344.23  344.41  344.46
  344.46  344.61  344.72  344.86  344.83  344.93  344.88  345.05  345.15  345.47
  345.39  345.43  345.45  345.65  345.47  345.74  345.95  345.92  346.07  346.09
   346.1   346.5  346.31  346.49  346.53   346.6  346.72  346.99  347.07  347.13
  347.15  347.22  347.17  347.33   347.4  347.25
                                                                                
                                                                                
                                                                                
                                                                                
                                                                                
                                                                                
                                                                                
                                                                                
                                                                                
                                                                                
                                                                                
                                                                                
                                                                                
                                                                                
                                                                                
                                                                                
                                                
BR Coef=-1 , 0 , 0 ,, 0 ,,,0.8,0,,0,
WSPro=,,,, 1 ,,,, 0 ,,,, 0 ,,,,-1 ,-1 ,-1 , 0 , 0 , 0 , 0 , 0
Culvert=1,6,,155,0.014,0.5,1,1,1,329,560,329,520,Culvert #1  , 0 ,15
Culvert Bottom n=0.014
BC Design=,, 0 ,, 0 ,,,,,,
BC Use User HTab Curves=0
BC User HTab FreeFlow(D)= 0

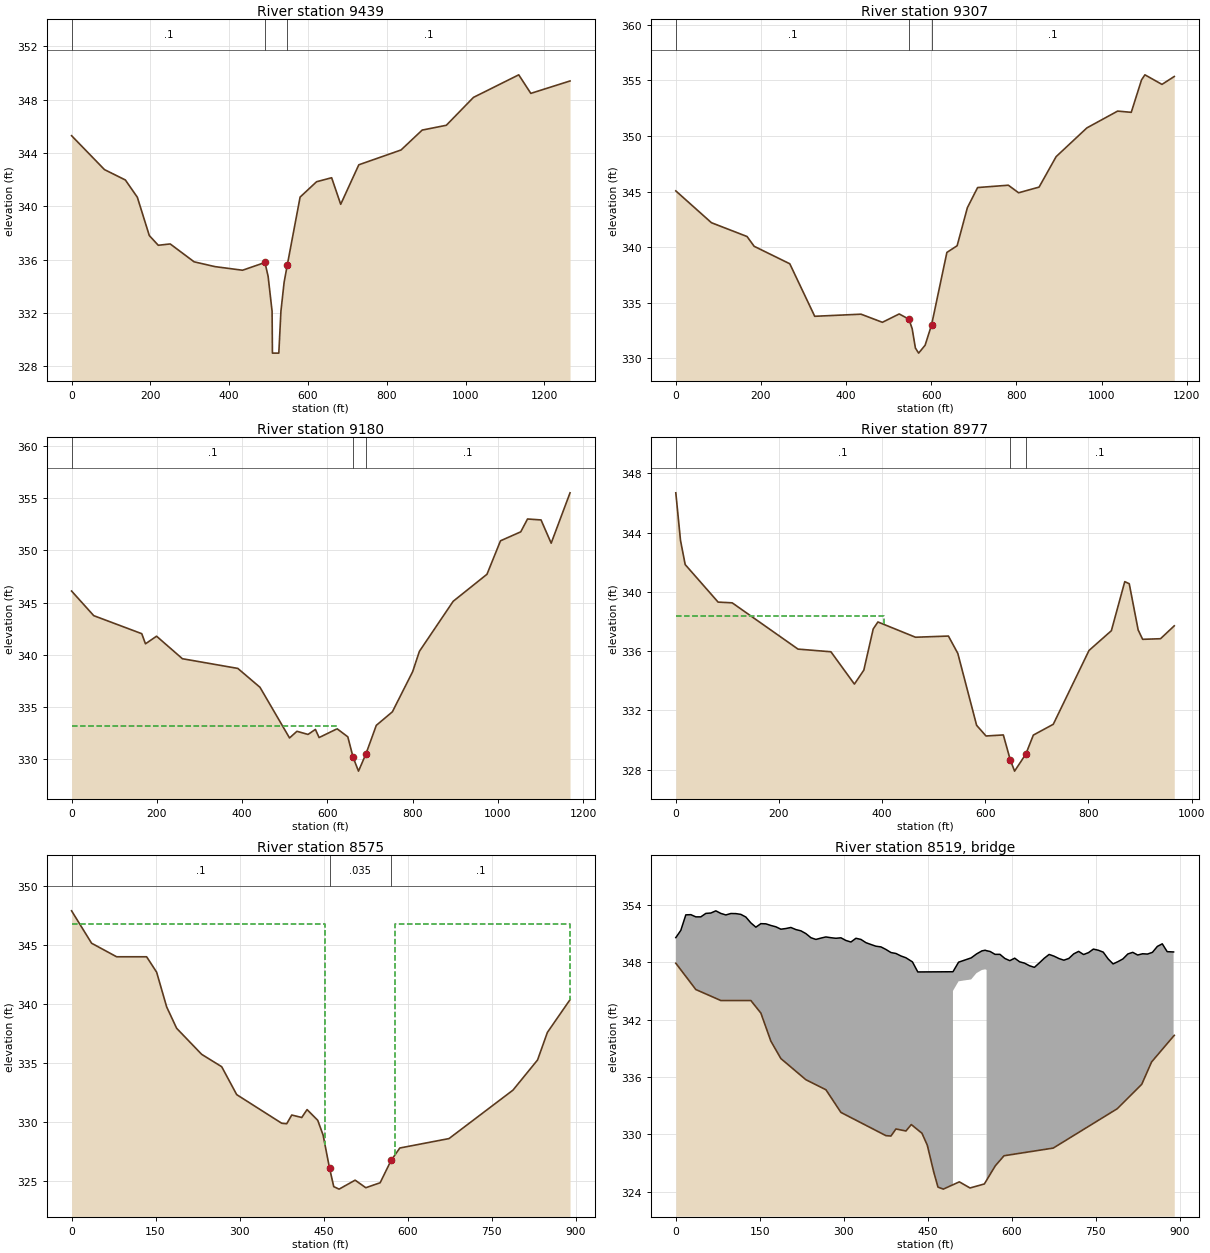
Type RM Length L Ch R = 1 ,9439    ,140.02,132.67,127.02
BEGIN DESCRIPTION:
Ground elevation lowered to accomodate culvert opening.
END DESCRIPTION:
XS GIS Cut Line= 4
 1578291.2879452741545.9280194191578691.72097154741712.965796098
1578853.77590981741807.8836885241579450.00848998742072.340082288
#Sta/Elev= 30
       0  345.29   83.43  342.75  136.52  341.97  166.86  340.68   197.2  337.81
  219.95  337.08  250.29  337.18  310.97  335.84  364.06  335.48  433.88  335.21
  490.66  335.79  498.77  334.75  508.81  332.13  509.66     329  525.89     329
  531.22  332.13  539.34  334.31  547.45  335.61   579.9  340.69  621.68  341.84
  659.97  342.14  682.94  340.15  728.89  343.11   836.1  344.22   889.7  345.71
  950.96  346.07 1019.88  348.16 1134.75  349.85 1165.38  348.46 1264.93  349.39
#Mann= 3 , 0 , 0
       0      .1       0  490.66    .035       0  547.45      .1       0
Bank Sta=490.66,547.45
XS Rating Curve= 0 ,0
Exp/Cntr=0.5,0.3

Type RM Length L Ch R = 1 ,9307    ,79.09,126.45,136.73
XS GIS Cut Line= 4
 1578209.1460977 741555.463309021578641.83353543 741838.73350206
1578744.55789113741882.3135317561579217.71249931742146.906569228
#Sta/Elev= 30
       0  345.06   83.67   342.2  167.33  340.96  184.07  340.08  267.73  338.51
   326.3  333.79  435.07  333.98  485.27  333.25  524.77     334  547.58  333.53
  555.19  332.68  562.79  330.94  570.39  330.48   585.6  331.19  600.81  333.02
  636.77  339.53  660.83  340.13  684.89  343.55  708.95  345.36  781.14  345.57
   805.2  344.89  853.32   345.4  893.42  348.14   965.6  350.72 1037.78  352.23
 1069.86  352.12 1093.92  355.03 1101.94  355.49 1142.04  354.63 1170.86  355.34
#Mann= 3 , 0 , 0
       0      .1       0  547.58    .035       0  600.81      .1       0
Bank Sta=547.58,600.81
XS Rating Curve= 0 ,0
Exp/Cntr=0.3,0.1

Type RM Length L Ch R = 1 ,9180    ,155.78,202.93,206.88
XS GIS Cut Line= 4
1578047.15717824741502.0624592161578550.31038244741869.614090636
1578603.83731902741951.6887267831578999.93664998742162.228010789
#Sta/Elev= 30
       0   346.1   52.01  343.74  164.71  342.01  173.38  341.04  199.38  341.77
  260.06  339.61  390.09  338.68  442.11  336.87  511.46  332.01  528.79  332.65
   554.8  332.35  572.14  332.83  580.81  332.05   623.1  332.89  648.17  332.12
  660.74  330.14  673.25  328.83  690.81  330.49  715.03  333.22   752.8  334.52
  800.36  338.37  816.22  340.32  895.49  345.12  974.77  347.71 1006.48  350.92
 1054.04  351.78  1069.9  353.01 1101.61  352.92 1125.39  350.69 1169.67  355.52
#Mann= 3 , 0 , 0
       0      .1       0  660.74    .035       0  690.81      .1       0
#XS Ineff= 2 , 0
          623.17  333.19
Permanent Ineff=
       F       F
Bank Sta=660.74,690.81
XS Rating Curve= 0 ,0
Exp/Cntr=0.3,0.1

Type RM Length L Ch R = 1 ,8977    ,391.76,401.77,301.15
XS GIS Cut Line= 4
1577897.28175573741512.7678465251578368.31879792741905.298715055
1578393.29803501741994.5102760791578546.74191996742205.049560085
#Sta/Elev= 30
       0  346.68    9.11  343.47   18.22  341.84   82.01  339.31  109.34  339.26
  236.91  336.14  300.69  335.96  346.25  333.78  364.48  334.72   382.7   337.5
  391.81  337.97  464.71  336.94  528.49  337.02  546.72  335.85  583.17     331
  601.39  330.28  634.96  330.35   648.4  328.67  656.77  327.91  678.55  329.06
  693.11  330.34  731.78  331.07  801.08  336.05  844.38  337.38  870.37  340.69
  879.03  340.55  896.36  337.43  905.02   336.8  939.66  336.84  966.32  337.71
#Mann= 3 , 0 , 0
       0      .1       0   648.4    .035       0  678.55      .1       0
#XS Ineff= 2 , 0
          403.46  338.35
Permanent Ineff=
       F       F
Bank Sta=648.4,678.55
XS Rating Curve= 0 ,0
Exp/Cntr=0.5,0.3

Type RM Length L Ch R = 1 ,8575    ,156.14,136,167.9
XS GIS Cut Line= 4
1577709.73353453741517.5549036261577971.15436007741847.016765937
1578059.73420259741942.8276160211578264.68447948742213.071786448
#Sta/Elev= 30
       0  347.89   35.74  345.14   80.42  343.99  134.04  343.99  151.91  342.68
  169.78  339.74  187.65  337.92  232.33  335.71  268.08  334.66  294.89  332.29
  375.31  329.86  384.24  329.82  393.18  330.56  411.05  330.35  420.58  331.02
  439.64  330.11  449.18  328.86  460.69  326.05  468.24  324.48  477.78  324.27
  506.38  325.03  525.44  324.39  551.06  324.81  570.55   326.7   586.2  327.76
  674.06  328.56  788.27  332.67  832.19  335.23  849.76  337.57  890.23  340.35
#Mann= 3 , 0 , 0
       0      .1       0  460.69    .035       0  570.55      .1       0
#XS Ineff= 2 , 0
       0  452.73   346.8   577.9       0   346.8
Permanent Ineff=
       F       F
Bank Sta=460.69,570.55
XS Rating Curve= 0 ,0
Exp/Cntr=0.5,0.3

Type RM Length L Ch R = 3 ,8519    ,,,
BEGIN DESCRIPTION:
Railroad  MDE Bridge #:
Road Profile taken from DEM
Adjustments made to top of road to fill in gap in DEM.
Structure was not surveyed.
Opening assumed to be 60ft and a 2 ft deck.......this is a Railroad bridge.
END DESCRIPTION:
Bridge Culvert--1,0,-1,-1, 0
Deck Dist Width WeirC Skew NumUp NumDn MinLoCord MaxHiCord MaxSubmerge Is_Ogee
35,25,2.6,0, 94, 93, , , 0.98, 0, 0,0,,
       0    8.94   17.87   26.81   35.74   44.68   53.62   62.55   71.49   80.42
   89.36    98.3  107.23  116.17   125.1  134.04  142.97  151.91  160.85  169.78
  178.72  187.65  196.59  205.53  214.46   223.4  232.33  241.27  250.21  259.14
  268.08  277.01  285.95  294.89  303.82  312.76  321.69  330.63  339.57   348.5
  357.44  366.37  375.31  384.24  393.18  402.12  411.05  422.65  432.19     495
     505  527.52  537.05  546.59  552.53     555  561.32  570.11  578.89  587.68
  596.46  605.25  614.03  622.82   631.6  640.39  649.17  657.96  666.74  675.53
  684.31   693.1  701.89  710.67  719.46  728.24  737.03  745.81   754.6  763.38
  772.17  780.95  789.74  798.52  807.31  816.09  824.88  833.67  842.45  851.24
  860.02  868.81  877.59  889.02
  350.57  351.33  352.95  352.97  352.74  352.74   353.1  353.14  353.37   353.1
  352.94  353.09  353.08     353  352.72  352.11  351.66  352.03  352.01  351.84
   351.7  351.45  351.52  351.63  351.41  351.28  350.99  350.56  350.38  350.52
  350.64  350.56   350.5  350.55  350.27  350.11   350.5  350.38  350.04  349.85
  349.67   349.6  349.33  349.01  348.91  348.65  348.46  348.03  346.98     347
     348  348.45  348.86  349.18  349.25   349.2  349.12  348.82  348.82  348.39
  348.16  348.42  348.04   347.9  347.63  347.46  347.92  348.41  348.81  348.63
  348.38  348.21  348.39  348.87  349.13   348.8     349  349.37  349.25  349.05
  348.34  347.82  348.06  348.34  348.86  349.03  348.75  348.88  348.85  349.03
  349.65  349.92   349.1  349.07
                                                                                
                                                                                
                                                                                
                                                                                
                                                                             345
     346   346.2  346.86  347.18  347.25   347.2
                                                                                
                                                                                
                                                                                
                                
       0    8.94   17.87   26.81   35.74   44.68   53.62   62.55   71.49   80.42
   89.36    98.3  107.23  116.17   125.1  134.04  142.97  151.91  160.85  169.78
  178.72  187.65  196.59  205.53  214.46   223.4  232.33  241.27  250.21  259.14
  268.08  277.01  285.95  294.89  303.82  312.76  321.69  330.63  339.57   348.5
  357.44  366.37  375.31  384.24  393.18  402.12  411.05  422.65  432.19     435
     495  527.52  537.05  546.59  552.53  561.32  570.11  578.89  587.68  596.46
  605.25  614.03  622.82   631.6  640.39  649.17  657.96  666.74  675.53  684.31
   693.1  701.89  710.67  719.46  728.24  737.03  745.81   754.6  763.38  772.17
  780.95  789.74  798.52  807.31  816.09  824.88  833.67  842.45  851.24  860.02
  868.81  877.59  889.02
  350.57  351.33  352.95  352.97  352.74  352.74   353.1  353.14  353.37   353.1
  352.94  353.09  353.08     353  352.72  352.11  351.66  352.03  352.01  351.84
   351.7  351.45  351.52  351.63  351.41  351.28  350.99  350.56  350.38  350.52
  350.64  350.56   350.5  350.55  350.27  350.11   350.5  350.38  350.04  349.85
  349.67   349.6  349.33  349.01  348.91  348.65  348.46  348.03  346.98     347
     348  348.45  348.86  349.18  349.25  349.12  348.82  348.82  348.39  348.16
  348.42  348.04   347.9  347.63  347.46  347.92  348.41  348.81  348.63  348.38
  348.21  348.39  348.87  349.13   348.8     349  349.37  349.25  349.05  348.34
  347.82  348.06  348.34  348.86  349.03  348.75  348.88  348.85  349.03  349.65
  349.92   349.1  349.07
                                                                                
                                                                                
                                                                                
                                                                                
                                                                             345
     346
                                                                                
                                                                                
                                                                                
                        
BR Coef=-1 , 0 , 0 ,, 0 ,,,0.8,0,,0,
WSPro=,,,, 1 ,,,, 0 ,,,, 0 ,,,,-1 ,-1 ,-1 , 0 , 0 , 0 , 0 , 0
BC Design=,, 0 ,, 0 ,,,,,,
BC Use User HTab Curves=0
BC User HTab FreeFlow(D)= 0

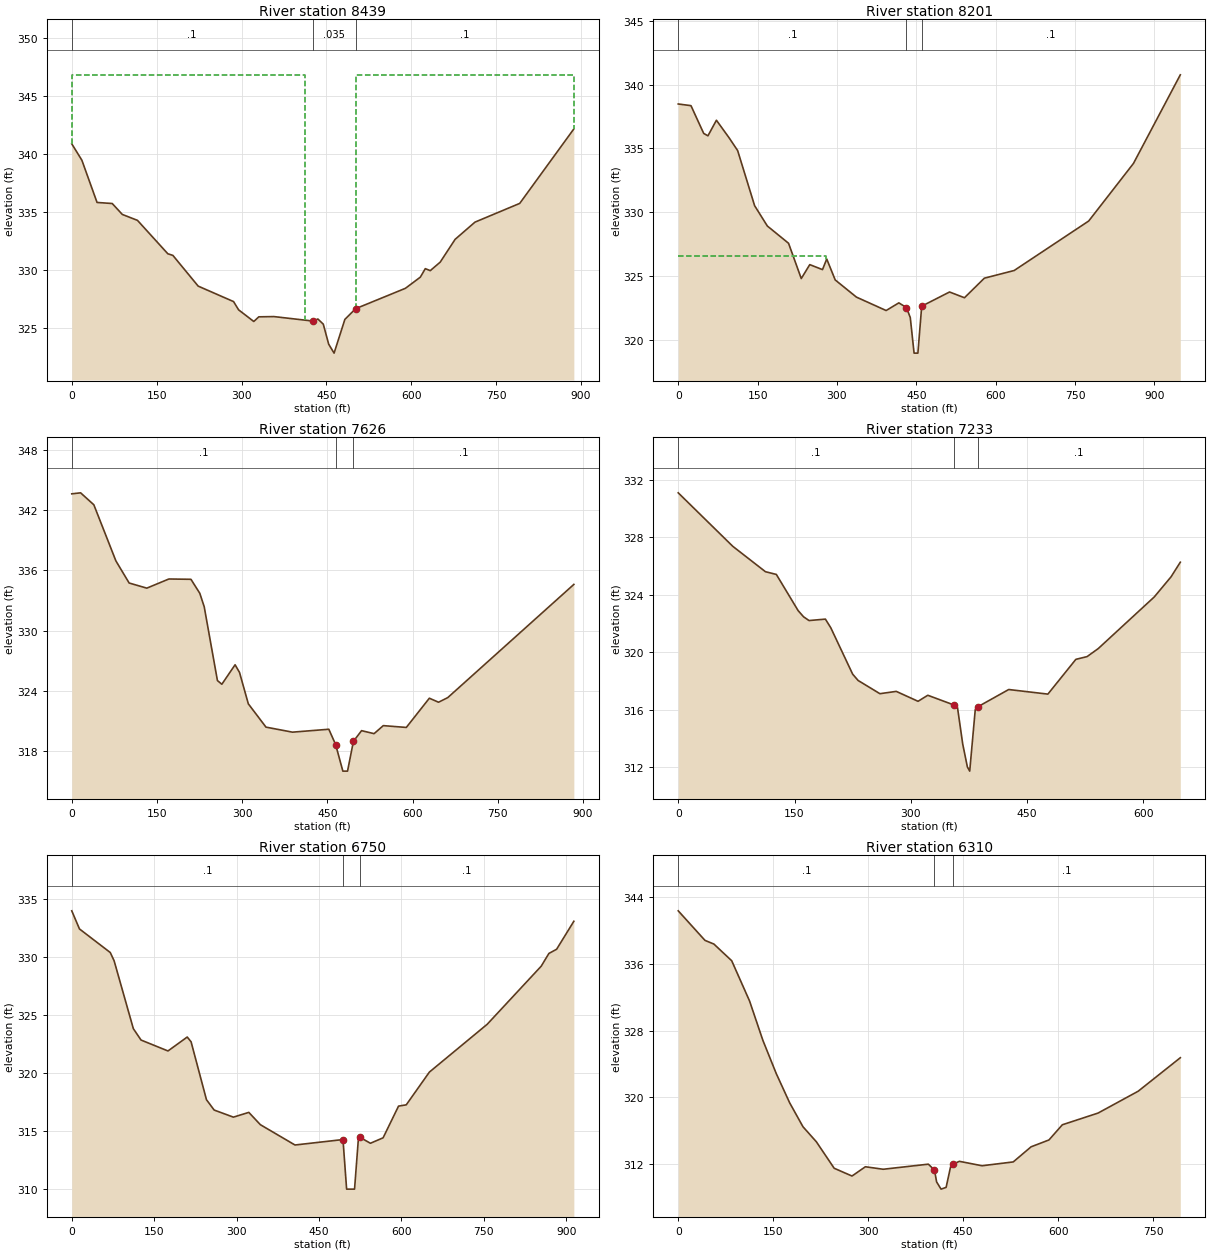
Type RM Length L Ch R = 1 ,8439    ,211.41,238.58,207.17
XS GIS Cut Line= 4
1577607.89742218741598.3596449791577872.36809237741931.665147066
 1577959.9796384742026.4286560571578161.10307282742291.626812994
#Sta/Elev= 30
       0  340.87   17.87  339.46   44.68  335.83   71.49  335.74   89.36   334.8
  116.17  334.29  169.78  331.42  178.72  331.28   223.4  328.64  285.95  327.31
  294.89   326.6  321.69   325.6  330.63     326  357.44  326.02  425.48  325.64
  435.02  325.81  444.55  325.37  454.08  323.65  463.62  322.88  482.68  325.78
  501.75   326.7  589.68  328.45  616.04  329.41  624.83  330.14  633.61  329.97
  651.18   330.7  677.54  332.66  712.68  334.14  791.75  335.75  887.38  342.15
#Mann= 3 , 0 , 0
       0      .1       0  425.48    .035       0  501.75      .1       0
#XS Ineff= 2 , 0
       0  411.45   346.8     502       0   346.8
Permanent Ineff=
       F       F
Bank Sta=425.48,501.75
XS Rating Curve= 0 ,0
Exp/Cntr=0.5,0.3

Type RM Length L Ch R = 1 ,8201    ,387.21,574.82,345.03
XS GIS Cut Line= 4
1577304.91699049741734.0125178841577668.90015949741937.414877012
1577686.74247167742012.3525882961577990.06177919742351.356520161
#Sta/Elev= 30
       0  338.48   24.06  338.35   48.11  336.18   56.13  335.99   72.17  337.21
   96.23  335.83  112.26  334.84  144.34  330.53   168.4  328.94  208.49  327.59
  232.55  324.83  248.58  325.92  272.64  325.53  280.66  326.36   296.7  324.72
  336.79  323.38  392.92  322.33  416.96  322.93  431.35  322.56  438.55  321.78
  445.74     319  452.94     319  460.14  322.67  512.78  323.78  540.96  323.33
  578.53  324.86  634.89  325.46  775.78  329.33  860.32  333.83  948.89  340.76
#Mann= 3 , 0 , 0
       0      .1       0  431.35    .035       0  460.14      .1       0
#XS Ineff= 2 , 0
       0     280   326.6               0
Permanent Ineff=
       F       F
Bank Sta=431.35,460.14
XS Rating Curve= 0 ,0
Exp/Cntr=0.3,0.1

Type RM Length L Ch R = 1 ,7626    ,342.03,393.15,269.73
XS GIS Cut Line= 4
1576998.02922055742008.784125835 1577383.4231642742194.344172776
1577429.81317592 742269.281884031577747.40633321742454.841930971
#Sta/Elev= 30
       0  343.61   15.54  343.71   38.85  342.52   77.69  336.93     101  334.73
  132.08  334.22  170.92  335.13  209.77   335.1   225.3  333.71  233.07  332.38
  256.38  325.02  264.15  324.65  287.46  326.59  295.23  325.83  310.77   322.7
  341.84  320.38  388.46  319.88  452.44  320.17  464.47  318.64  477.14     316
  485.37     316  495.76  318.97  510.07  320.03  532.09  319.73   548.3  320.53
  588.84  320.35  629.38  323.26  645.59  322.86   661.8  323.32   883.7  334.59
#Mann= 3 , 0 , 0
       0      .1       0  464.47    .035       0  495.76      .1       0
Bank Sta=464.47,495.76
XS Rating Curve= 0 ,0
Exp/Cntr=0.3,0.1

Type RM Length L Ch R = 1 ,7233    ,484.07,483.19,455.76
XS GIS Cut Line= 4
1576851.21921989742430.2713512331577164.09263791742459.846450448
1577240.13465713742493.5187930611577482.76641381742554.733227089
#Sta/Elev= 30
       0  331.09   70.31  327.37   112.5   325.6  126.56  325.41  154.69  322.89
  161.72  322.46  168.75   322.2  189.84   322.3  196.87  321.69     225  318.47
  232.03  318.03  260.15  317.11  281.25  317.27  309.37  316.58  321.92     317
  355.83  316.32   360.2  316.16     367   313.6     373  312.01     376  311.72
  383.17  316.01   386.2  316.19  426.31   317.4  476.84  317.08  512.94   319.5
  527.38  319.69  541.82  320.25  614.01  323.84  635.67  325.24  647.67  326.26
#Mann= 3 , 0 , 0
       0      .1       0  355.83    .035       0   386.2      .1       0
Bank Sta=355.83,386.2
XS Rating Curve= 0 ,0
Exp/Cntr=0.3,0.1

Type RM Length L Ch R = 1 ,6750    ,426.99,440.06,417.23
XS GIS Cut Line= 4
1576519.85525349742854.5097243641576990.89229567742872.352036566
1577076.53539427742893.7628111991577429.81317592742918.742048293
#Sta/Elev= 30
       0  333.97   14.01  332.41   70.05  330.38   77.06  329.67  112.08  323.82
  126.09  322.84  175.13   321.9  210.15   323.1  217.16  322.69  245.18   317.7
  259.19  316.81  294.21   316.2  322.23  316.61  343.25  315.55  406.29   313.8
  493.64  314.27  500.24     310  514.67     310  521.88  314.47  524.62  314.46
  543.53  313.95  566.67  314.42  594.74  317.15  608.78  317.26  650.88  320.08
  756.14   324.2  854.39   329.2  868.42   330.3  882.46  330.66  913.81  333.07
#Mann= 3 , 0 , 0
       0      .1       0  493.64    .035       0  524.62      .1       0
Bank Sta=493.64,524.62
XS Rating Curve= 0 ,0
Exp/Cntr=0.3,0.1

Type RM Length L Ch R = 1 ,6310    ,246.59,278.02,265.33
XS GIS Cut Line= 4
1576426.18100812743229.7950826291576777.25122733743265.346497223
1576903.90314186743272.0123874691577214.97801962743307.563802063
#Sta/Elev= 30
       0  342.34   42.21   338.8   56.29  338.36   84.43  336.36  112.57  331.55
  133.68  326.82  154.79  322.84  175.89  319.35     197  316.47  218.11  314.67
  246.25   311.5   274.4  310.57   295.5  311.68  323.65  311.38  394.92  311.99
  404.64  311.28     408  309.86     415     309     423  309.21  429.97  311.65
  434.61  312.02  443.99  312.33  479.69   311.8  529.01  312.26  557.19  314.07
  585.38  314.89  606.51  316.71  662.88  318.11  726.29  320.73  792.79  324.74
#Mann= 3 , 0 , 0
       0      .1       0  404.64    .035       0  434.61      .1       0
Bank Sta=404.64,434.61
XS Rating Curve= 0 ,0
Exp/Cntr=0.3,0.1

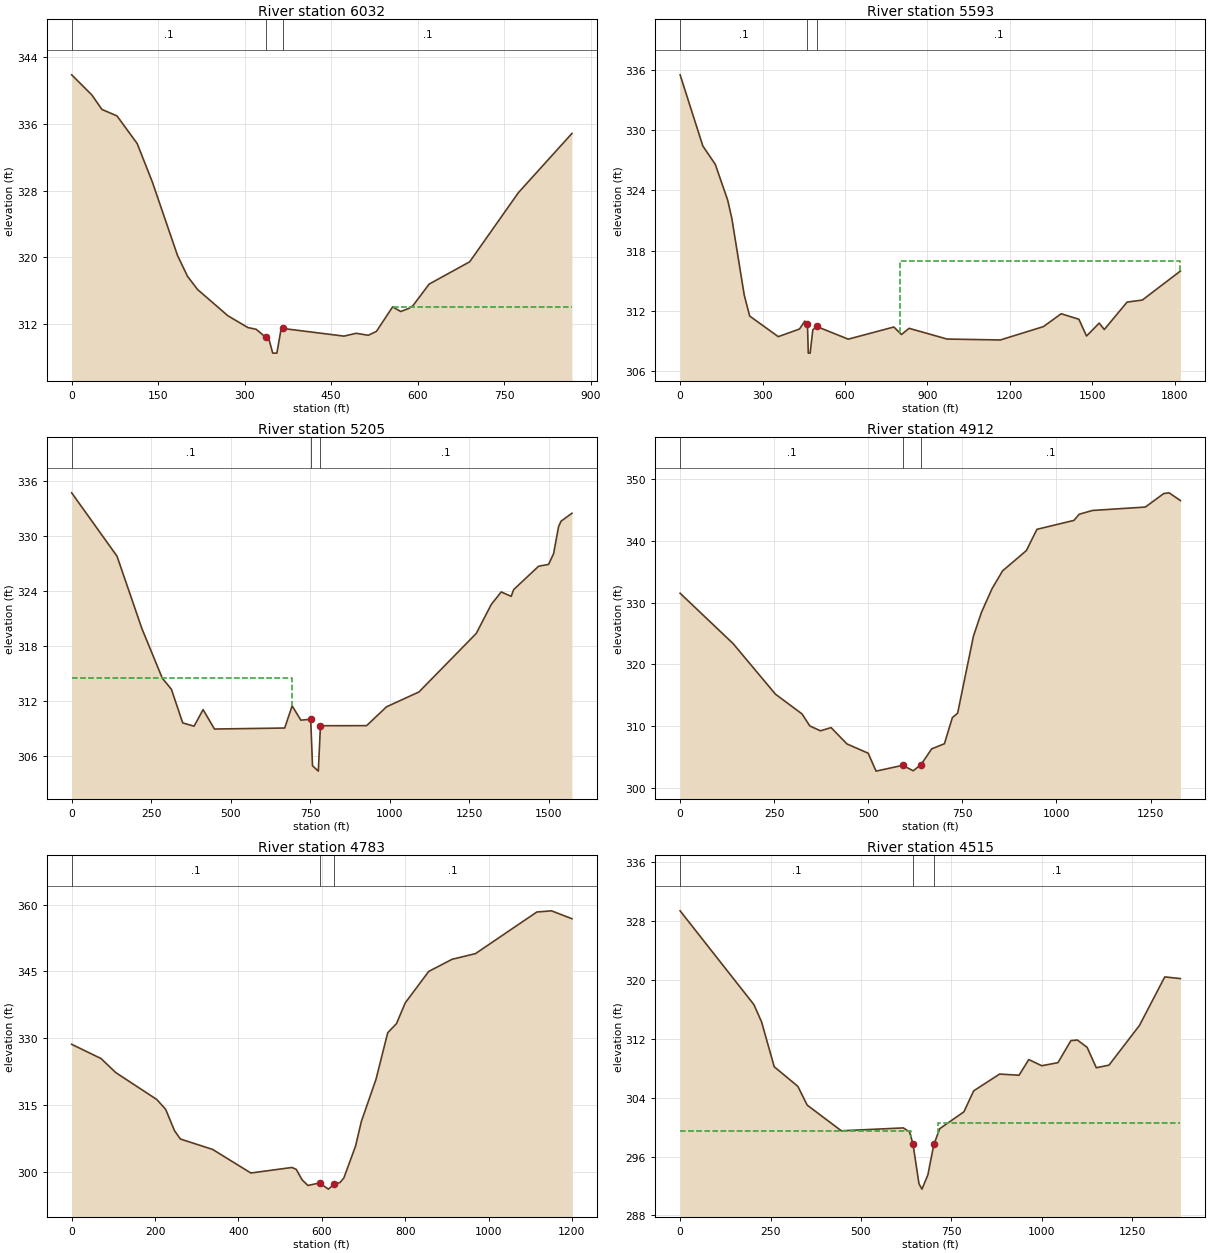
Type RM Length L Ch R = 1 ,6032    ,308,438.41,522.62
XS GIS Cut Line= 4
1576452.05446707743321.9783041331576691.14145066743500.401426196
1576812.46917364743528.949125722 1577254.9585163743571.770675018
#Sta/Elev= 30
       0  341.89   34.94  339.48   52.41  337.74   78.61  336.96  113.55  333.65
  139.75  329.06  183.42  320.24  200.89  317.71  218.36  316.13  270.77  312.99
  305.52  311.57   319.9  311.36  336.25  310.42  341.47  310.32  348.66   308.5
  355.85   308.5  363.04  311.35  366.18  311.46  472.19  310.54  493.29  310.88
  514.39  310.64  528.46  311.11  556.59  314.05  570.65  313.49  584.72  313.87
  591.75  314.19  619.88  316.78  690.21  319.46   774.6  327.75  867.52  334.86
#Mann= 3 , 0 , 0
       0      .1       0  336.25    .035       0  366.18      .1       0
#XS Ineff= 2 , 0
                          556.89          314.06
Permanent Ineff=
       F       F
Bank Sta=336.25,366.18
XS Rating Curve= 0 ,0
Exp/Cntr=0.3,0.1

Type RM Length L Ch R = 1 ,5593    ,246.97,388.03,326.03
XS GIS Cut Line= 5
1576498.44447882 743471.853726671576591.22450228743707.372247785
1576698.27837552743853.6792078471576769.64762431 743928.61691913
1577605.25140043 744901.78701815
#Sta/Elev= 30
       0   335.5   82.76  328.41   127.9  326.59  173.04  323.03  188.09  321.22
  233.23  313.59  253.13  311.49  357.22  309.44  434.42   310.2  453.76  310.99
  463.42  310.65  466.38   307.8  473.09   307.8  482.76  310.11  496.29  310.46
  611.72  309.19   777.8   310.4  805.48  309.65  833.15  310.27  971.55   309.2
  1165.3  309.11 1322.15  310.44 1386.73  311.72 1451.32  311.17    1479   309.5
 1525.13  310.79 1543.58  310.15 1626.62  312.88 1681.98  313.08  1820.6  315.97
#Mann= 3 , 0 , 0
       0      .1       0  463.42    .035       0  496.29      .1       0
#XS Ineff= 2 , 0
       0                     800       0     317
Permanent Ineff=
       F       F
Bank Sta=463.42,496.29
XS Rating Curve= 0 ,0
Exp/Cntr=0.3,0.1

Type RM Length L Ch R = 1 ,5205    ,208.13,293.45,324.14
XS GIS Cut Line= 4
1576463.87622641743511.6840610651576591.22450228744192.683139756
1576666.16221356744281.8947007661577008.73460791744963.471027017
#Sta/Elev= 30
       0  334.74  142.43  327.82  220.76   319.9  284.85  314.48  313.34  313.28
  348.95   309.6  384.55  309.24  413.04  311.05  448.64  308.93  669.41  309.04
   692.8  311.46  720.23   309.9  751.17     310   756.8  304.92  775.08  304.33
  781.83  309.29  926.83   309.3  989.51  311.36 1091.35  312.98 1271.55  319.38
 1318.55  322.54 1349.89  323.91 1381.23  323.43 1389.06  324.17 1467.41  326.72
 1498.75  326.92 1514.42  328.09 1530.08  331.04 1537.92  331.64 1572.14  332.51
#Mann= 3 , 0 , 0
       0      .1       0  751.17    .035       0  781.83      .1       0
#XS Ineff= 2 , 0
          693.06  314.49
Permanent Ineff=
       F       F
Bank Sta=751.17,781.83
XS Rating Curve= 0 ,0
Exp/Cntr=0.3,0.1

Type RM Length L Ch R = 1 ,4912    ,124.85,128.99,134.4
XS GIS Cut Line= 4
1576412.80138023743561.0652876791576355.70598118744121.313890934
1576362.84290604744239.0731514991576309.31596942744884.964853302
#Sta/Elev= 30
       0  331.52  140.73  323.36  253.31  315.15  323.67  311.96  344.78  309.99
  372.92  309.21  401.07  309.73  443.28  307.08  499.57  305.58  520.68  302.67
   591.2  303.61  619.25  302.73  640.29  303.74  668.34  306.28   702.2  307.11
  723.27  311.34  737.32  312.07  779.46  324.59  800.53  328.41  828.63  332.25
  856.72  335.15  919.94  338.44  948.04  341.89 1046.37  343.34 1060.42  344.34
 1095.54  344.95 1236.02   345.5 1285.19   347.7 1299.24  347.81 1329.23  346.56
#Mann= 3 , 0 , 0
       0      .1       0   591.2    .035       0  640.29      .1       0
Bank Sta=591.2,640.29
XS Rating Curve= 0 ,0
Exp/Cntr=0.3,0.1

Type RM Length L Ch R = 1 ,4783    ,169.56,267.69,285.77
XS GIS Cut Line= 4
1576291.47365725743582.4760623431576230.80979571744117.745428488
1576230.80979571744231.9362266061576195.12517132744777.910980091
#Sta/Elev= 30
       0  328.65   70.45  325.46  105.67  322.31   204.3  316.26  225.43  314.06
  246.57  309.29  260.66   307.4  338.15  305.06  429.73  299.77  528.36  301.01
   538.7  300.58   552.7  298.24   566.7  296.97   594.7  297.54   615.7  296.15
   629.7  297.26   643.7  297.64  652.89  298.66  680.95  305.81  694.98  311.37
  730.05  320.81  758.11  331.25  779.16   333.3   800.2  337.96  856.32     345
  912.44  347.73  968.56     349 1115.87  358.35 1150.95  358.61 1200.03  356.84
#Mann= 3 , 0 , 0
       0      .1       0   594.7    .035       0   629.7      .1       0
Bank Sta=594.7,629.7
XS Rating Curve= 0 ,0
Exp/Cntr=0.5,0.3

Type RM Length L Ch R = 1 ,4515    ,92.66,96.16,106.3
XS GIS Cut Line= 6
1576219.84677832743561.5326458071576190.61977248743842.810697526
1575981.30582523744137.6190738981575917.01103809744242.327727214
 1575676.9014892744542.1255255641575660.88127597744774.248171508
#Sta/Elev= 30
       0  329.36  204.09  316.63  225.21  314.29  260.39  308.19  325.72  305.53
  351.47  302.99  445.91   299.5   617.6  299.89  634.77  299.34  644.35  297.67
  660.78  292.31  668.99  291.58  685.42  293.52  701.85  297.64  718.28  299.79
  785.16  302.08  812.06  304.92  883.81   307.2  937.62  307.04  964.53  309.17
  1000.4  308.33 1045.24  308.75 1081.11  311.74 1099.05  311.82 1125.96  310.83
 1151.32  308.06  1186.4  308.41  1270.6  313.79 1340.77  320.39 1383.99  320.16
#Mann= 3 , 0 , 0
       0      .1       0  644.35    .035       0  701.85      .1       0
#XS Ineff= 2 , 0
       0  638.34  299.47  713.14       0   300.5
Permanent Ineff=
       F       F
Bank Sta=644.35,701.85
XS Rating Curve= 0 ,0
Exp/Cntr=0.5,0.3