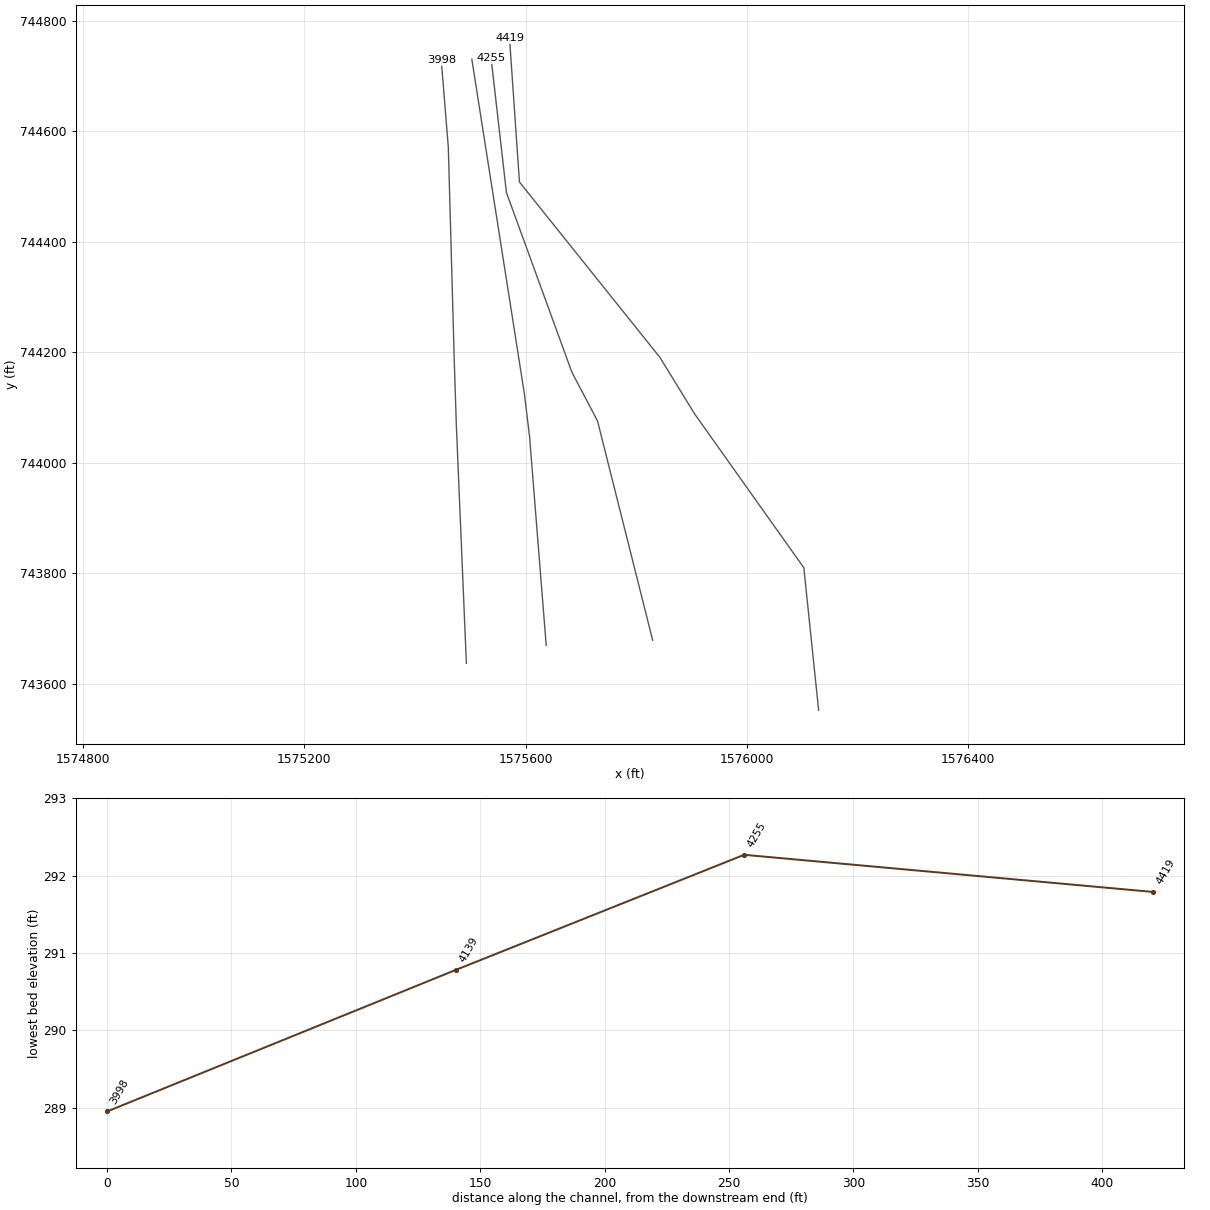
HEC-RAS study StoneRunTrib1.prj: StoneRunTrib1

--- StoneRunTrib1.g01 (geometry) --- (continued)

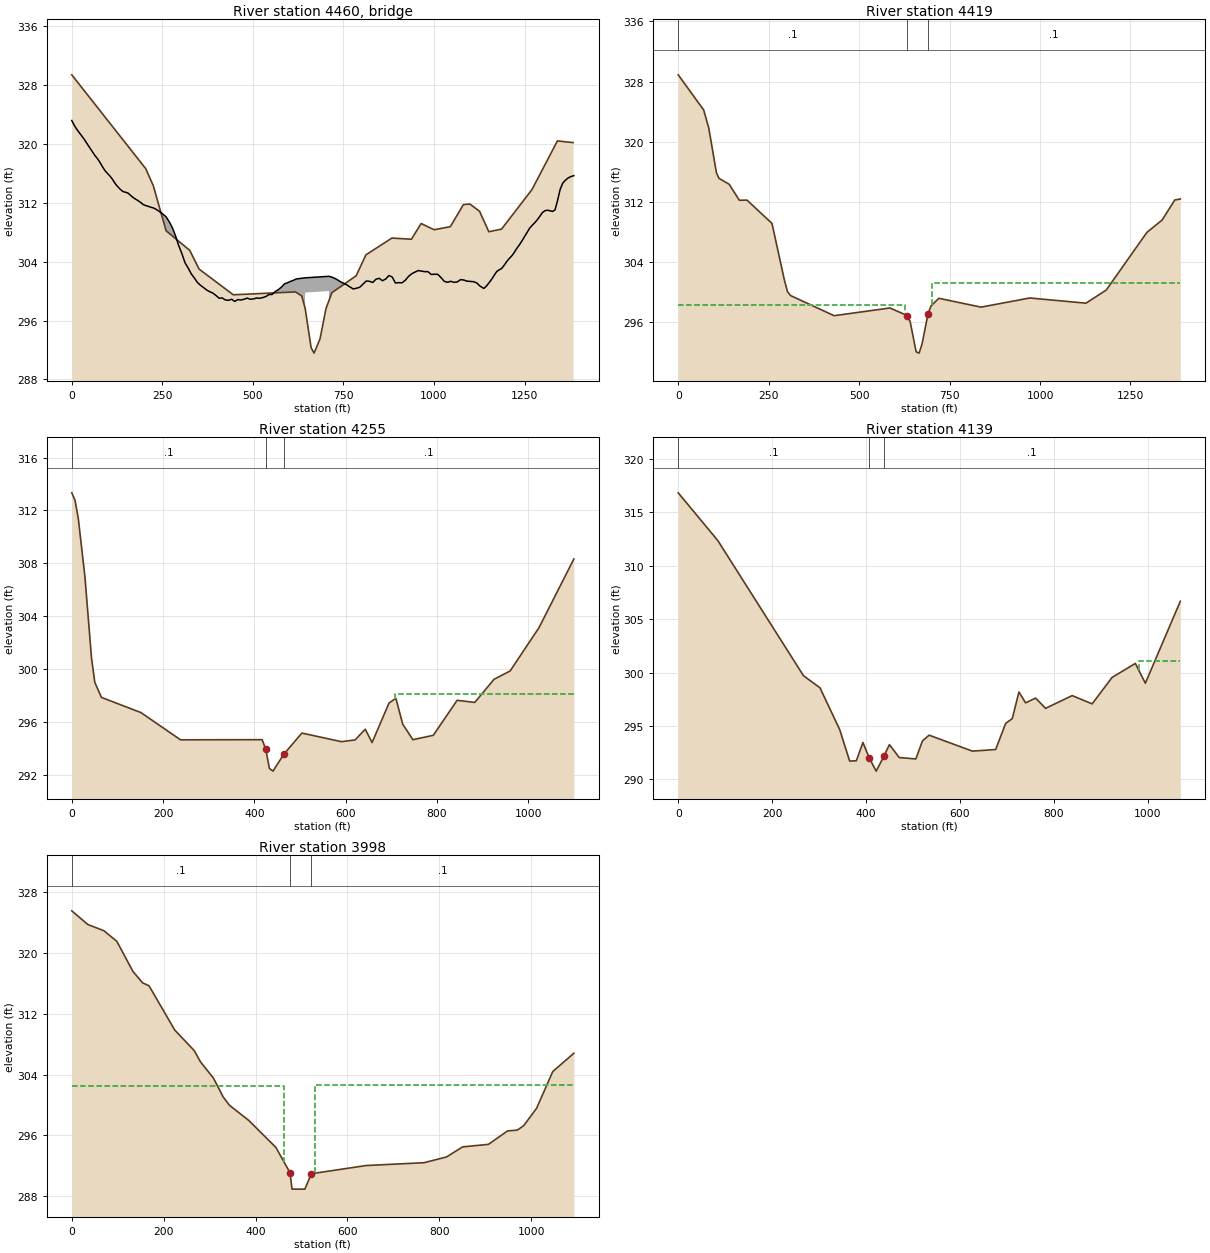
Type RM Length L Ch R = 3 ,4460    ,,,
BEGIN DESCRIPTION:
N. Walnut Street.  MDE Bridge #:CE 042407FS-9
Road Profile taken from DEM
Structure from surveys
END DESCRIPTION:
Bridge Culvert--1,0,-1,-1, 0
Deck Dist Width WeirC Skew NumUp NumDn MinLoCord MaxHiCord MaxSubmerge Is_Ogee
35,24,2.6,0, 165, 166, , , 0.98, 0, 0,0,,
       0    7.04   14.08   21.11   28.15   35.19   42.23   49.26    56.3   63.34
   70.38   77.41   84.45   91.49   98.53  105.57   112.6  119.64  126.68  133.72
  140.75  147.79  154.83  161.87   168.9  175.94  182.98  190.02  197.06  204.09
  211.13  218.17  225.21  232.24  239.28  246.32  253.36  260.39  269.66  278.24
  286.83  295.41     304  312.58  321.16  329.75  338.33  346.92   355.5  364.09
  372.67  381.26  389.84  398.43  407.01   415.6  424.18  432.77  441.35  449.94
  458.52  467.11  475.69  484.28  492.86  501.45  510.03  518.62   527.2  535.79
  544.37  552.96  561.54  570.13  578.71   587.3  595.88  604.47  613.05  619.75
   644.1   710.1  718.32  726.53  734.75  741.17  750.14   759.1  768.07  777.04
  786.01  794.98  803.95  812.91  821.88  830.85  839.82  848.79  857.76  866.72
  875.69  884.66  893.63   902.6  911.57  920.53   929.5  938.47  947.44  956.41
  965.38  974.34  983.31  992.28 1001.25 1010.22 1019.19 1028.15 1037.12 1046.09
 1055.06 1064.03    1073 1081.96 1090.93  1099.9 1108.87 1117.84 1126.81 1137.79
  1144.8 1151.82 1158.84 1165.85 1172.87 1179.89  1186.9 1193.92 1200.94 1207.95
 1214.97 1221.99    1229 1236.02 1243.04 1250.05 1257.07 1264.09  1271.1 1278.12
 1285.14 1292.15 1299.17 1306.19  1313.2 1320.22 1327.24 1334.25 1341.27 1348.29
  1355.3 1362.32 1369.34 1376.35  1386.1
  323.16  322.49  321.95  321.48  321.03  320.55  320.01   319.5  318.97  318.45
  318.01  317.51  316.91  316.37  315.97  315.61  315.16  314.61  314.19  313.83
  313.53  313.43  313.32  313.01  312.72  312.49  312.28  312.04  311.76  311.61
  311.51  311.38  311.29  311.12   310.9  310.64  310.38  310.08  309.37  308.54
  307.45  306.15  305.09  303.86  303.15  302.35  301.79  301.17  300.78  300.47
  300.14  299.91  299.72  299.39  299.03  299.07  298.79  298.75  298.89   298.6
  298.85  298.79  298.89  299.05  298.89  298.94  299.06  299.02  299.12  299.26
  299.53  299.54  299.94  300.19  300.54  300.98  301.14  301.33  301.49  301.65
   301.8  302.01  301.89  301.72  301.49  301.29  301.07  300.85  300.56  300.29
  300.39  300.52  300.94  301.37  301.33  301.17  301.62  301.73  301.41  301.64
  302.12  301.91   301.1  301.15  301.12  301.46  301.99  302.35  302.58  302.79
  302.71  302.64  302.64  302.26  302.29  302.28  301.85  301.33   301.2  301.33
  301.19  301.24  301.55  301.51  301.35  301.31  301.28  301.12  300.69  300.36
  300.69  301.12  301.58  302.11  302.64  302.89  303.08  303.52  304.02  304.43
   304.8  305.27  305.83   306.3  306.83  307.39  307.97  308.54  308.93  309.28
  309.68  310.15  310.65  310.91  310.98  310.91  310.81  311.04  312.33  313.81
  314.64  315.03  315.32  315.52  315.67
                                                                                
                                                                                
                                                                                
                                                                                
                                                                                
                                                                                
                                                                                
                                                                                
   299.8  300.01
                                                                                
                                                                                
                                                                                
                                                                                
                                                                                
                                                                                
                                                                                
                                        
       0    7.04   14.08   21.11   28.15   35.19   42.23   49.26    56.3   63.34
   70.38   77.41   84.45   91.49   98.53  105.57   112.6  119.64  126.68  133.72
  140.75  147.79  154.83  161.87   168.9  175.94  182.98  190.02  197.06  204.09
  211.13  218.17  225.21  232.24  239.28  246.32  253.36  260.39  269.66  278.24
  286.83  295.41     304  312.58  321.16  329.75  338.33  346.92   355.5  364.09
  372.67  381.26  389.84  398.43  407.01   415.6  424.18  432.77  441.35  449.94
  458.52  467.11  475.69  484.28  492.86  501.45  510.03  518.62   527.2  535.79
  544.37  552.96  561.54  570.13  578.71   587.3  595.88  604.47  613.05  619.75
     632     698   710.1  718.32  726.53  734.75  741.17  750.14   759.1  768.07
  777.04  786.01  794.98  803.95  812.91  821.88  830.85  839.82  848.79  857.76
  866.72  875.69  884.66  893.63   902.6  911.57  920.53   929.5  938.47  947.44
  956.41  965.38  974.34  983.31  992.28 1001.25 1010.22 1019.19 1028.15 1037.12
 1046.09 1055.06 1064.03    1073 1081.96 1090.93  1099.9 1108.87 1117.84 1126.81
 1137.79  1144.8 1151.82 1158.84 1165.85 1172.87 1179.89  1186.9 1193.92 1200.94
 1207.95 1214.97 1221.99    1229 1236.02 1243.04 1250.05 1257.07 1264.09  1271.1
 1278.12 1285.14 1292.15 1299.17 1306.19  1313.2 1320.22 1327.24 1334.25 1341.27
 1348.29  1355.3 1362.32 1369.34 1376.35  1386.1
  323.16  322.49  321.95  321.48  321.03  320.55  320.01   319.5  318.97  318.45
  318.01  317.51  316.91  316.37  315.97  315.61  315.16  314.61  314.19  313.83
  313.53  313.43  313.32  313.01  312.72  312.49  312.28  312.04  311.76  311.61
  311.51  311.38  311.29  311.12   310.9  310.64  310.38  310.08  309.37  308.54
  307.45  306.15  305.09  303.86  303.15  302.35  301.79  301.17  300.78  300.47
  300.14  299.91  299.72  299.39  299.03  299.07  298.79  298.75  298.89   298.6
  298.85  298.79  298.89  299.05  298.89  298.94  299.06  299.02  299.12  299.26
  299.53  299.54  299.94  300.19  300.54  300.98  301.14  301.33  301.49  301.65
   301.8     302  302.01  301.89  301.72  301.49  301.29  301.07  300.85  300.56
  300.29  300.39  300.52  300.94  301.37  301.33  301.17  301.62  301.73  301.41
  301.64  302.12  301.91   301.1  301.15  301.12  301.46  301.99  302.35  302.58
  302.79  302.71  302.64  302.64  302.26  302.29  302.28  301.85  301.33   301.2
  301.33  301.19  301.24  301.55  301.51  301.35  301.31  301.28  301.12  300.69
  300.36  300.69  301.12  301.58  302.11  302.64  302.89  303.08  303.52  304.02
  304.43   304.8  305.27  305.83   306.3  306.83  307.39  307.97  308.54  308.93
  309.28  309.68  310.15  310.65  310.91  310.98  310.91  310.81  311.04  312.33
  313.81  314.64  315.03  315.32  315.52  315.67
                                                                                
                                                                                
                                                                                
                                                                                
                                                                                
                                                                                
                                                                                
                                                                                
   299.8     300
                                                                                
                                                                                
                                                                                
                                                                                
                                                                                
                                                                                
                                                                                
                                                
BR Coef=-1 , 0 , 0 ,, 0 ,,,0.8,0,,0,
WSPro=,,,, 1 ,,,, 0 ,,,, 0 ,,,,-1 ,-1 ,-1 , 0 , 0 , 0 , 0 , 0
BC Design=,, 0 ,, 0 ,,,,,,
BC Use User HTab Curves=0
BC User HTab FreeFlow(D)= 0

Type RM Length L Ch R = 1 ,4419    ,230.75,164.26,215.35
XS GIS Cut Line= 6
 1576130.3287372743552.2310159951576103.54566087 743809.98891212
1575906.18228668744087.9654954671575843.25376631744190.449085757
1575589.05363965744507.8402043731575571.09485865744768.051457942
#Sta/Elev= 30
       0  328.89   70.38   324.2   84.45  321.79  105.57  315.84   112.6  315.09
  140.75   314.3   168.9  312.17  190.02  312.19  259.15  309.08  293.49  301.52
  302.07  299.98  310.66  299.46  430.84  296.78  585.37  297.81  632.92   296.8
  641.13  295.97  657.56  291.97  665.78  291.79  673.99  293.01  690.42  297.03
  698.63  298.07  720.32   299.1  836.91  297.92  971.44  299.14 1126.96  298.45
 1183.09   300.2 1295.36  307.88 1337.46  309.53 1372.54   312.2 1387.79  312.34
#Mann= 3 , 0 , 0
       0      .1       0  632.92    .035       0  690.42      .1       0
#XS Ineff= 2 , 0
       0  626.89  298.21  702.46       0  301.12
Permanent Ineff=
       F       F
Bank Sta=632.92,690.42
XS Rating Curve= 0 ,0
Exp/Cntr=0.5,0.3

Type RM Length L Ch R = 1 ,4255    ,161.6,115.97,82.05
XS GIS Cut Line= 5
1575830.04062507 743678.919162751575730.27052701744075.679320082
1575683.86583026744163.8482439371575565.53385347 744488.68112129
1575537.69103545744732.305779293
#Sta/Elev= 30
       0  313.33    7.22  312.76   14.44  311.35   28.87  306.96   43.31  300.81
   50.53  298.98   64.96  297.85  151.58   296.7  238.19  294.64  417.02  294.65
  424.93  293.92  432.84  292.48  440.75  292.27  464.48  293.55  504.04  295.15
   590.7   294.5   620.5  294.63  642.85  295.44  657.75  294.43     695  297.43
   709.9  297.78   724.8  295.83  747.15  294.65  791.85  294.98     844  297.63
  882.65  297.47  924.92  299.22  960.15  299.85 1023.56  303.14 1099.67  308.32
#Mann= 3 , 0 , 0
       0      .1       0  424.93    .035       0  464.48      .1       0
#XS Ineff= 2 , 0
                          707.86           298.1
Permanent Ineff=
       F       F
Bank Sta=424.93,464.48
XS Rating Curve= 0 ,0
Exp/Cntr=0.3,0.1

Type RM Length L Ch R = 1 ,4139    ,145.71,140.09,104.61
XS GIS Cut Line= 4
 1575637.4611335743669.6382233951575607.29808061744047.836502016
1575598.01714124 744124.404251681575502.88751286744729.985544458
#Sta/Elev= 30
       0   316.8   84.27  312.34  266.84   299.7  301.96  298.57  344.09  294.65
  365.16  291.72   379.4  291.75   393.5  293.46  407.28  291.97  421.71  290.78
   438.4   292.2  449.91  293.26   470.7  292.05  506.13  291.92   520.3  293.61
  534.47  294.14  626.59  292.65  676.19   292.8  697.45  295.24  711.62  295.69
  725.79  298.18  739.96  297.16  761.22  297.61  782.48  296.65  839.16  297.84
  881.68  297.07  924.19  299.54  973.79  300.85  995.05     299 1069.53  306.66
#Mann= 3 , 0 , 0
       0      .1       0  407.28    .035       0   438.4      .1       0
#XS Ineff= 2 , 0
                          981.09          301.09
Permanent Ineff=
       F       F
Bank Sta=407.28,438.4
XS Rating Curve= 0 ,0
Exp/Cntr=0.5,0.3

Type RM Length L Ch R = 1 ,3998    ,130.18,124.98,173.95
XS GIS Cut Line= 5
1575493.04649384743636.9526758491575474.90597114744066.883065209
1575471.28915881744179.0042476951575460.35632363744570.764173254
1575447.51938044744728.475190192
#Sta/Elev= 30
       0  325.51   35.03  323.71   70.06  322.89   98.09   321.5  133.12  317.55
  154.14  316.05  168.15  315.66   224.2  309.84  266.24  307.17  280.25  305.66
  308.27  303.54  329.29  301.08  343.31  299.96  385.34  297.97  444.32  294.42
  474.97  291.11  479.34  288.95  507.31  288.95  521.36  290.97  640.53  292.05
  766.58  292.42   815.6  293.18  850.61   294.5  906.64  294.83  948.45   296.6
  969.52   296.7  983.57  297.29 1011.66  299.58 1046.78   304.4 1092.64   306.8
#Mann= 3 , 0 , 0
       0      .1       0  474.97    .035       0  521.36      .1       0
#XS Ineff= 2 , 0
          461.74  302.51  529.37          302.57
Permanent Ineff=
       F       F
Bank Sta=474.97,521.36
XS Rating Curve= 0 ,0
Exp/Cntr=0.5,0.3