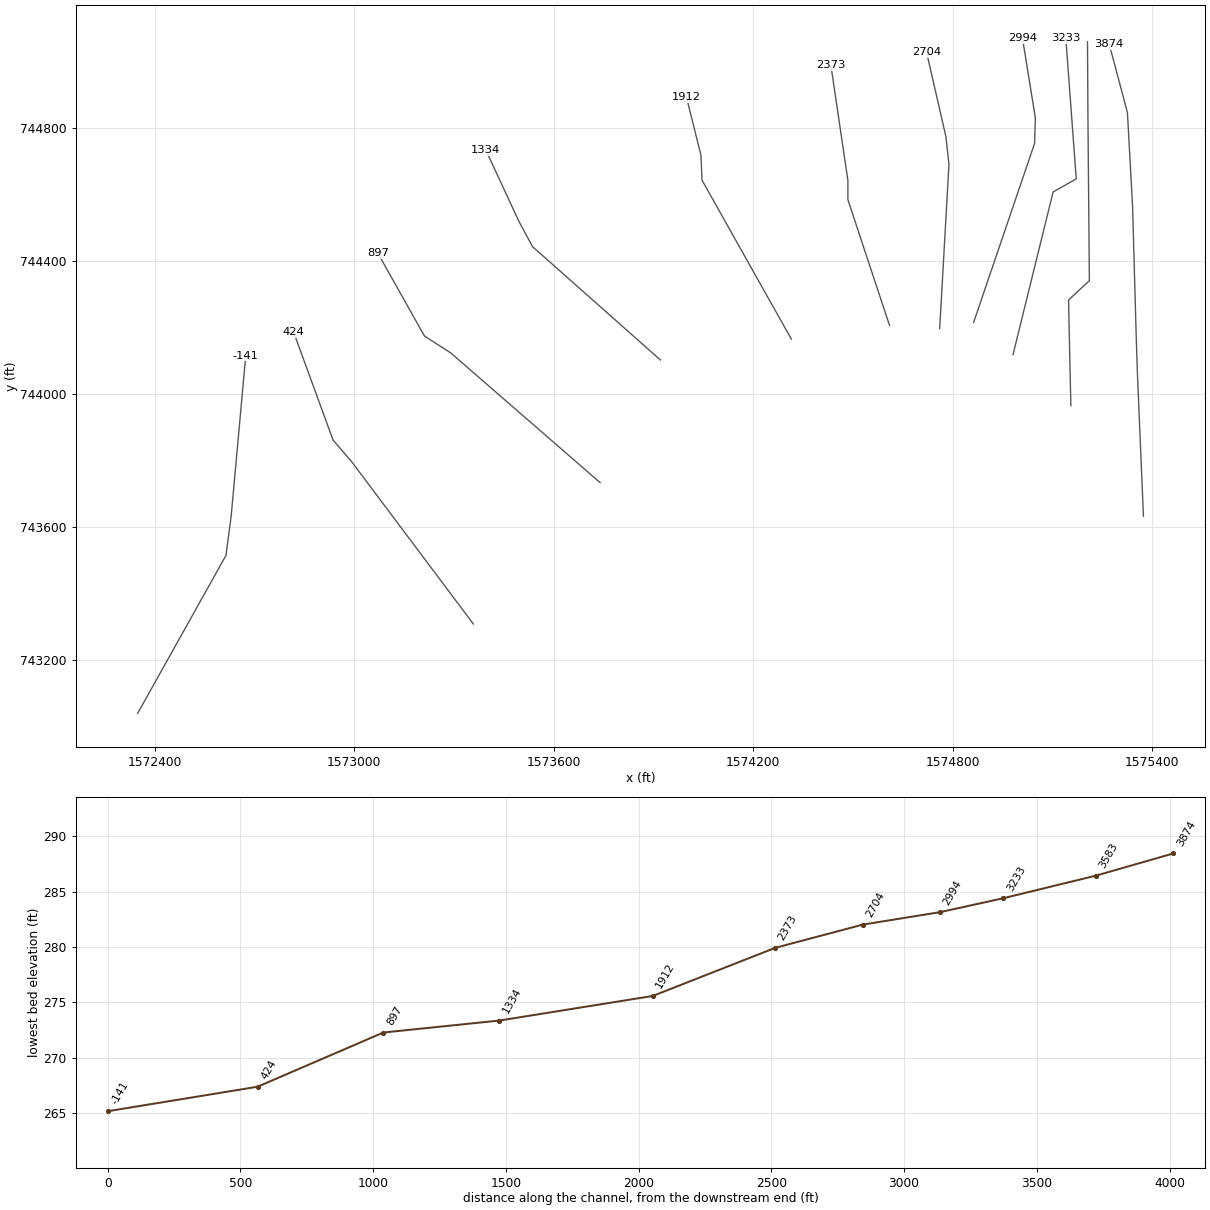
HEC-RAS study StoneRunTrib1.prj: StoneRunTrib1

--- StoneRunTrib1.g01 (geometry) --- (continued)

Type RM Length L Ch R = 2 ,3934    ,,,
BEGIN DESCRIPTION:
Mount St.  MDE Bridge #:042407FS-8.
Road Profile taken from DEM
END DESCRIPTION:
Bridge Culvert--1,0,-1,-1, 0
Deck Dist Width WeirC Skew NumUp NumDn MinLoCord MaxHiCord MaxSubmerge Is_Ogee
33,38,2.6,0, 156, 157, , , 0.98, 0, 0.5,0.5,,
       0    7.01   14.01   21.02   28.02   35.03   42.04   49.04   56.05   63.06
   70.06   77.07   84.07   91.08   98.09  105.09   112.1  119.11  126.11  133.12
  140.12  147.13  154.14  161.14  168.15  175.16  182.16  189.17  196.17  203.18
  210.19  217.19   224.2  231.21  238.21  245.22  252.22  259.23  266.24  273.24
  280.25  287.26  294.26  301.27  308.27  315.28  322.29  329.29   336.3  343.31
  350.31  357.32  364.32  371.33  378.34  385.34  392.35  399.35  406.36  413.37
  420.37  430.61  437.61  444.62  451.62  458.62  465.63  472.63  479.64  486.64
  493.64  500.65  507.65  514.65  521.66  528.66  535.67  543.22  550.22  557.22
  564.23  571.23  578.23  585.23  592.24  599.24  606.24  613.25  620.25  627.25
  634.25  641.26  648.26  655.26  662.26  669.27  676.27  683.27  690.28  697.28
  704.28  711.28  718.29  725.29  732.29  739.29   746.3   753.3   760.3  767.31
  774.31  781.31  788.31  795.32  802.32  809.32  816.33  823.33  830.33  837.33
  844.34  851.34  858.34  865.34  872.35  879.35  886.35  893.36  900.36  907.36
  914.36  921.37  928.37  933.66  940.69  947.71  954.73  961.75  968.78   975.8
  982.82  989.85  996.87 1003.89 1010.92 1017.94 1024.96 1031.99 1039.01 1046.03
 1053.06 1060.08  1067.1 1074.13 1081.15  1090.3
  318.91  318.46  317.91  317.76  317.62  317.55  317.42  317.03  316.49  316.09
  315.85   315.6  315.35  315.05  314.73  314.42  314.02  313.88  313.77  313.66
  313.44  313.14  312.85  312.56  312.22  311.93   311.7   311.4  311.08  310.86
  310.67  310.43  310.24  309.96  309.72  309.47  309.19  308.93  308.74  308.55
  308.35  308.11  307.93  307.78  307.59   307.4  307.23  307.02  306.89  306.74
  306.52  306.31  306.16  306.12     306  305.72  305.55  305.42  305.23   305.2
  305.14  304.69  304.56  304.48  304.42  304.31  304.18  304.07  303.91  303.95
  303.99  303.81  303.65  303.57   303.5  303.47  303.41  303.48  303.46  303.38
  303.29  303.24  303.15  303.08     303  303.08  303.12  303.04  302.94  303.01
  303.14  303.16  303.07  302.86  302.85  302.92  302.93   302.9  302.93  302.91
  302.88  302.93  302.87  302.77  302.83   302.8  302.78  302.85  302.78  302.87
   302.9  302.85  302.95  302.97     303  303.04     303  303.06  303.15  303.28
  303.35   303.4  303.39  303.34  303.37  303.55  303.63  303.68  303.78  303.94
  304.05  304.13  304.22  304.27  304.43  304.72  304.92  305.03  305.32  305.53
  305.74  306.12  306.36  306.41  306.54  307.03   307.3  307.49  307.73  307.95
   308.3   308.6  308.66  308.89  309.28  309.51
                                                                                
                                                                                
                                                                                
                                                                                
                                                                                
                                                                                
                                                                                
                                                                                
                                                                                
                                                                                
                                                                                
                                                                                
                                                                                
                                                                                
                                                                                
                                                
       0    7.01   14.01   21.02   28.02   35.03   42.04   49.04   56.05   63.06
   70.06   77.07   84.07   91.08   98.09  105.09   112.1  119.11  126.11  133.12
  140.12  147.13  154.14  161.14  168.15  175.16  182.16  189.17  196.17  203.18
  210.19  217.19   224.2  231.21  238.21  245.22  252.22  259.23  266.24  273.24
  280.25  287.26  294.26  301.27  308.27  315.28  322.29  329.29   336.3  343.31
  350.31  357.32  364.32  371.33  378.34  385.34  392.35  399.35  406.36  413.37
  420.37  430.61  437.61  444.62  451.62  458.62  465.63  472.63  479.64  486.64
  493.64  500.65  507.65  514.65  521.66  528.66  535.67  543.22  550.22  557.22
  564.23  571.23  578.23  585.23  592.24  599.24  606.24  613.25  620.25  627.25
  634.25  641.26  648.26  655.26  662.26  669.27  676.27  683.27  690.28  697.28
  704.28  711.28  718.29  725.29  732.29  739.29   746.3   753.3   760.3  767.31
  774.31  781.31  788.31  795.32  802.32  809.32  816.33  823.33  830.33  837.33
  844.34  851.34  858.34  865.34  872.35  879.35  886.35  893.36  900.36  907.36
  914.36  921.37  928.37  933.66  940.69  947.71  954.73  961.75  968.78   975.8
  982.82  989.85  996.87 1003.89 1010.92 1017.94 1024.96 1031.99 1039.01 1046.03
 1053.06 1060.08  1067.1 1074.13 1081.15  1090.3 1236.97
  318.91  318.46  317.91  317.76  317.62  317.55  317.42  317.03  316.49  316.09
  315.85   315.6  315.35  315.05  314.73  314.42  314.02  313.88  313.77  313.66
  313.44  313.14  312.85  312.56  312.22  311.93   311.7   311.4  311.08  310.86
  310.67  310.43  310.24  309.96  309.72  309.47  309.19  308.93  308.74  308.55
  308.35  308.11  307.93  307.78  307.59   307.4  307.23  307.02  306.89  306.74
  306.52  306.31  306.16  306.12     306  305.72  305.55  305.42  305.23   305.2
  305.14  304.69  304.56  304.48  304.42  304.31  304.18  304.07  303.91  303.95
  303.99  303.81  303.65  303.57   303.5  303.47  303.41  303.48  303.46  303.38
  303.29  303.24  303.15  303.08     303  303.08  303.12  303.04  302.94  303.01
  303.14  303.16  303.07  302.86  302.85  302.92  302.93   302.9  302.93  302.91
  302.88  302.93  302.87  302.77  302.83   302.8  302.78  302.85  302.78  302.87
   302.9  302.85  302.95  302.97     303  303.04     303  303.06  303.15  303.28
  303.35   303.4  303.39  303.34  303.37  303.55  303.63  303.68  303.78  303.94
  304.05  304.13  304.22  304.27  304.43  304.72  304.92  305.03  305.32  305.53
  305.74  306.12  306.36  306.41  306.54  307.03   307.3  307.49  307.73  307.95
   308.3   308.6  308.66  308.89  309.28  309.51  313.67
                                                                                
                                                                                
                                                                                
                                                                                
                                                                                
                                                                                
                                                                                
                                                                                
                                                                                
                                                                                
                                                                                
                                                                                
                                                                                
                                                                                
                                                                                
                                                        
BR Coef=-1 , 0 , 0 ,, 0 ,,,0.8,0,,0,
WSPro=,,,, 1 ,,,, 0 ,,,, 0 ,,,,-1 ,-1 ,-1 , 0 , 0 , 0 , 0 , 0
Multiple Barrel Culv=2,9,13,40.5,0.014,0.4,1,8,1,288.95,288.45, 2,Culvert #1  , 0 ,30
     485     485     500     500
Culvert Bottom n=0.014
BC Design=,, 0 ,, 0 ,,,,,,
BC Use User HTab Curves=0
BC User HTab FreeFlow(D)= 0

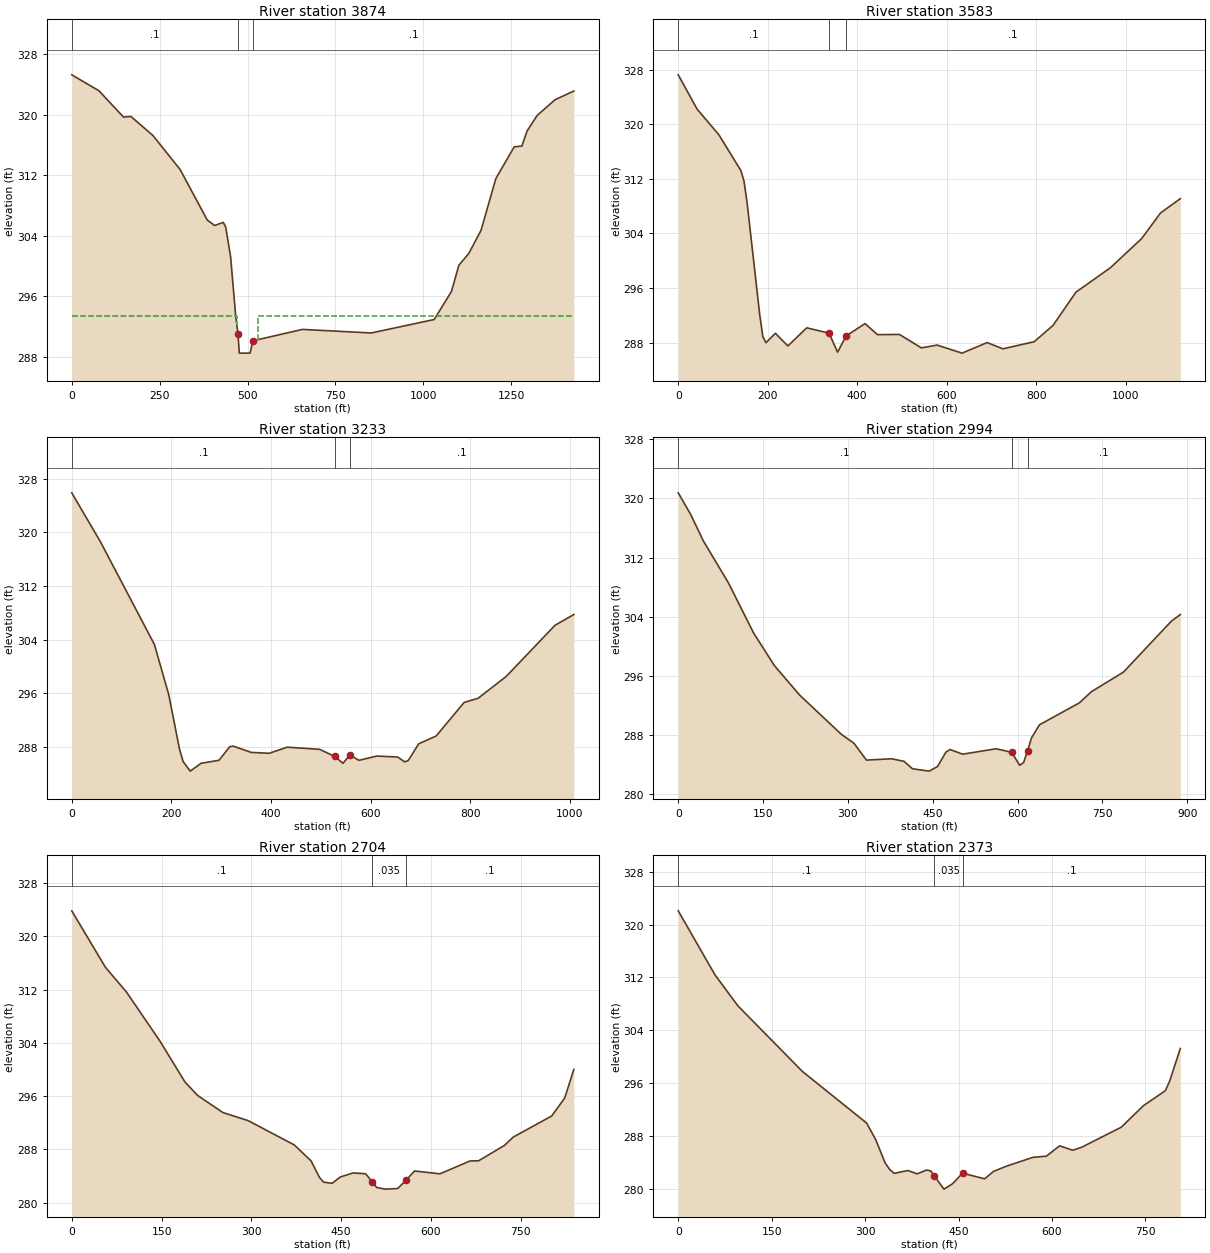
Type RM Length L Ch R = 1 ,3874    ,265.37,290.95,241.7
XS GIS Cut Line= 6
 1575373.1531719743631.8938859111575354.98755181744062.419082731
1575351.34313561744175.3959860351575340.49228498744564.218132272
1575324.98372699744846.1093088391575270.09734149745051.933254525
#Sta/Elev= 30
       0   325.3   77.07   323.2  147.13  319.71  168.15  319.79  231.21  317.25
  308.27  312.76  385.34  306.08  406.36  305.35  430.91  305.76  437.91  305.15
  451.92  301.18  465.93  293.56  472.93  290.94  476.61  288.45  507.32  288.45
  514.95  290.08  655.99  291.59  852.06  291.12 1031.07   292.9 1080.14  296.62
 1101.17  300.09 1129.22  301.63 1164.27  304.71 1206.33  311.56  1258.7  315.77
 1280.44  315.86 1294.93  317.84 1323.91  319.92 1374.62     322 1428.25  323.15
#Mann= 3 , 0 , 0
       0      .1       0  472.93    .035       0  514.95      .1       0
#XS Ineff= 2 , 0
       0  469.61   293.4   529.5       0   293.4
Permanent Ineff=
       F       F
Bank Sta=472.93,514.95
XS Rating Curve= 0 ,0
Exp/Cntr=0.5,0.3

Type RM Length L Ch R = 1 ,3583    ,172.05,349.36,95.5
XS GIS Cut Line= 5
1575154.85228713743964.3080478461575147.89158258744282.180220693
1575210.53792325744340.1860916471575206.29903354744825.538960338
1575204.91975872 745058.79405269
#Sta/Elev= 30
       0  327.26   42.01  322.25   91.02  318.45  140.03  313.22  147.04  311.65
  154.04  308.42  182.04  292.11  189.05  288.88  196.05  287.98  217.05  289.36
  245.06   287.5  287.07  290.16  337.03  289.38  356.11  286.59  375.19  288.97
  417.33  290.78  445.33  289.16  494.33  289.19  543.33  287.22  578.33  287.63
  634.33  286.45  690.34     288  725.34  287.08  795.34  288.12  837.34   290.5
   888.7  295.39   965.7  298.97  1035.7  303.26  1077.7     307 1121.95   309.1
#Mann= 3 , 0 , 0
       0      .1       0  337.03    .035       0  375.19      .1       0
Bank Sta=337.03,375.19
XS Rating Curve= 0 ,0
Exp/Cntr=0.3,0.1

Type RM Length L Ch R = 1 ,3233    ,158.29,238.87,148.69
XS GIS Cut Line= 4
1574980.83467428744117.4435471741575101.48688583744607.013098046
1575171.09393099744646.4570902741575139.74217589 745069.08524999
#Sta/Elev= 30
       0  325.89   57.68  318.58  165.82   303.3  194.65  295.83  216.28  287.71
  223.49  285.84  237.91  284.41  259.54  285.58  295.59  286.03  317.22  288.05
  324.42  288.13  360.47   287.2  396.52  287.07  432.57  287.98  497.45  287.66
     528   286.6  544.45  285.58  558.54  286.81  576.63  286.02   612.3  286.66
  654.42  286.51  668.45  285.79  675.47  285.98  696.53  288.48  731.63  289.65
  787.78  294.65  815.86  295.27  872.01  298.51  970.28  306.15 1008.01  307.75
#Mann= 3 , 0 , 0
       0      .1       0     528    .035       0  558.54      .1       0
Bank Sta=528,558.54
XS Rating Curve= 0 ,0
Exp/Cntr=0.3,0.1

Type RM Length L Ch R = 1 ,2994    ,213.07,290.21,280.13
XS GIS Cut Line= 4
1574862.50269751 744214.893410371575045.80124971744753.187892854
1575048.12148458744829.7556425041575009.38701035 745069.08524999
#Sta/Elev= 30
       0  320.74   22.18   317.8   44.37  314.25   88.74  308.58   133.1  301.83
  170.08   297.4  214.45  293.44  288.39  288.12  310.58  286.93  332.76  284.64
  377.13  284.82  399.31  284.47   414.1  283.47  443.68  283.15  458.47  283.77
  473.26  285.72  480.66  286.07  502.84  285.44     562  286.17  589.66  285.69
  603.66  283.94  610.67  284.31  617.67  285.91  624.67  287.65  638.68  289.41
  709.07  292.36  730.34  293.87  787.07  296.52  872.16  303.43  887.69  304.29
#Mann= 3 , 0 , 0
       0      .1       0  589.66    .035       0  617.67      .1       0
Bank Sta=589.66,617.67
XS Rating Curve= 0 ,0
Exp/Cntr=0.3,0.1

Type RM Length L Ch R = 1 ,2704    ,305.67,330.81,307.51
XS GIS Cut Line= 4
1574760.41236465744196.3315316741574788.25518267744690.541552216
1574778.97424336744774.0700063851574720.96837237745026.975603774
#Sta/Elev= 30
       0  323.82   56.09  315.36   91.14  311.65  147.23  304.27   189.3  298.08
  210.33  296.09   252.4  293.53  294.47  292.32  371.59  288.67  399.63  286.27
  413.65  283.79  420.67  283.08  434.69   282.9  448.71  283.86  469.74  284.46
  490.78  284.34  502.04   283.1  509.08  282.29  523.17  282.03   544.3  282.12
  558.38  283.39  572.47  284.75  614.95  284.33  665.22  286.26  679.58  286.29
  722.67   288.6  737.04  289.83  801.67  293.02  823.22  295.71  838.51  300.01
#Mann= 3 , 0 , 0
       0      .1       0  502.04    .035       0  558.38      .1       0
Bank Sta=502.04,558.38
XS Rating Curve= 0 ,0
Exp/Cntr=0.3,0.1

Type RM Length L Ch R = 1 ,2373    ,411.7,461.09,426.55
XS GIS Cut Line= 4
1574609.59710015744205.6124710141574484.30441888744583.810749665
1574484.30441888744641.8166206031574433.25925244744987.531611517
#Sta/Elev= 30
       0  322.08   58.99  312.38   95.86  307.68   199.1  297.77  302.34  289.94
  317.09  287.41  331.84  283.95  339.21  282.92  346.58  282.32  368.71  282.75
  383.46  282.24  398.41  282.82  405.41  282.69  411.16  281.93  426.41  279.93
  440.41  280.75  456.42  282.35   491.8  281.49  505.95  282.61  527.18  283.42
  569.63  284.75  590.86  284.92  612.09  286.49  633.32  285.82  647.47  286.27
  711.15  289.31  746.53  292.56  781.91  294.84  788.98  296.34  805.88  301.23
#Mann= 3 , 0 , 0
       0      .1       0  411.16    .035       0  456.42      .1       0
Bank Sta=411.16,456.42
XS Rating Curve= 0 ,0
Exp/Cntr=0.3,0.1

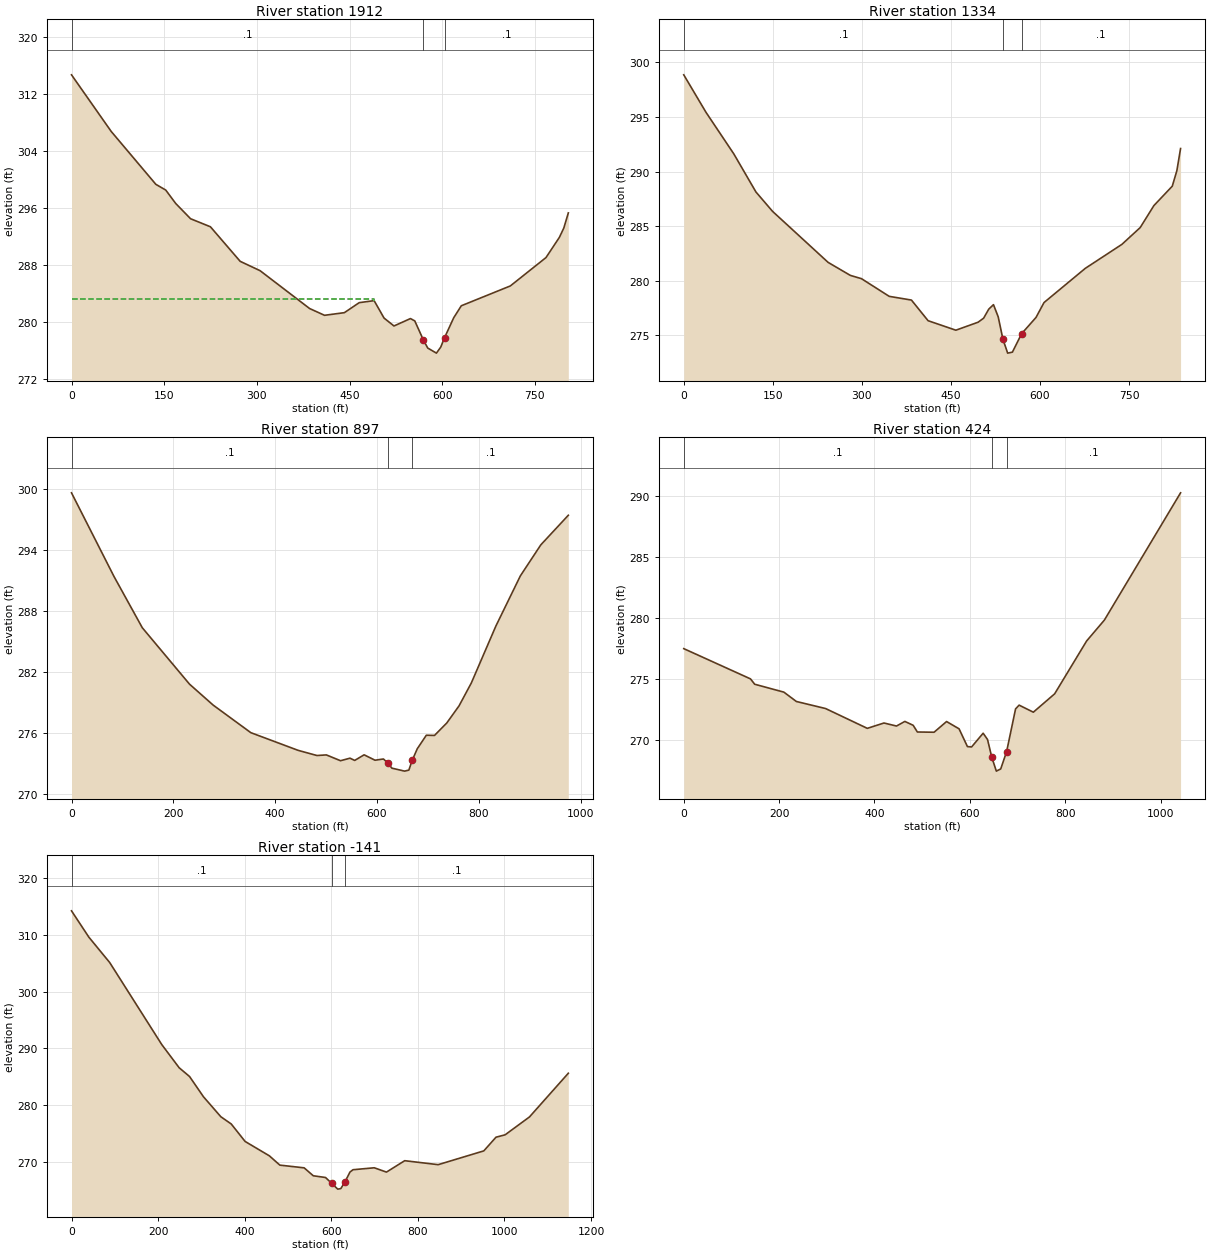
Type RM Length L Ch R = 1 ,1912    ,522.32,578.14,600.09
XS GIS Cut Line= 4
1574314.40820119744164.2283313131574045.58999076744642.474682316
1574042.46419765744717.4937177751573998.70309363744892.538133845
#Sta/Elev= 30
       0  314.73   64.24  306.77  136.51  299.33  152.57  298.52  168.63  296.64
  192.72  294.49  224.84  293.36  273.02   288.5  305.14  287.19  385.44  281.86
  409.53  280.91  441.65  281.28  465.74  282.69  489.83  282.97  505.89  280.52
  521.95  279.41  548.62  280.45  555.63  280.12  569.64  277.42  576.64   276.3
  590.66  275.59  597.66  276.44  603.83  277.77  618.68  280.57  630.92  282.25
  710.29  285.04  768.01  289.03  789.66  291.87  796.87  293.19  804.14  295.31
#Mann= 3 , 0 , 0
       0      .1       0  569.64    .035       0  603.83      .1       0
#XS Ineff= 2 , 0
          489.27  283.19
Permanent Ineff=
       F       F
Bank Sta=569.64,603.83
XS Rating Curve= 0 ,0
Exp/Cntr=0.3,0.1

Type RM Length L Ch R = 1 ,1334    ,401.76,436.85,451.01
XS GIS Cut Line= 4
1573920.55826503744101.7124684451573536.08570834744442.423921108
1573495.45039748744517.4429565671573395.42501685 744733.12268351
#Sta/Elev= 30
       0  298.86   37.41  295.43   84.18  291.63  121.59  288.13  149.65  286.35
  243.18  281.68  280.59  280.49   299.3  280.19  346.06  278.57  383.48  278.23
  411.54  276.34   458.3  275.47  495.71   276.2  505.07  276.57  513.72   277.4
  521.68  277.81  529.64  276.69   537.6  274.64  545.56  273.37  553.52  273.46
  569.09  275.15  593.32  276.64  606.75     278  676.19  281.13  737.92  283.33
  768.79  284.87  791.94  286.89   822.8  288.66  830.52  290.08  836.78  292.11
#Mann= 3 , 0 , 0
       0      .1       0   537.6    .035       0  569.09      .1       0
Bank Sta=537.6,569.09
XS Rating Curve= 0 ,0
Exp/Cntr=0.3,0.1

Type RM Length L Ch R = 1 ,897     ,482.13,473.6,400.94
XS GIS Cut Line= 4
1573739.26226264743732.8688774561573289.14804995744123.593020454
1573211.00322135744173.6057107451573070.34252986744423.669162244
#Sta/Elev= 30
       0  299.58   83.42  291.38  139.04  286.35  231.74  280.82  278.08  278.77
  352.24  276.06  444.93  274.33  482.01  273.82  500.55  273.88  528.36  273.31
   546.9  273.56  556.17  273.34  574.71  273.89  596.04  273.36  612.67  273.48
  620.98  273.09  629.29  272.58  654.22  272.29  662.53  272.39  669.16  273.35
  679.15  274.49  696.85  275.81  712.92  275.79  737.01  277.01  761.11  278.69
   785.2  280.93  833.39  286.51  881.58  291.44  921.73  294.48  975.73  297.38
#Mann= 3 , 0 , 0
       0      .1       0  620.98    .035       0  669.16      .1       0
Bank Sta=620.98,669.16
XS Rating Curve= 0 ,0
Exp/Cntr=0.3,0.1

Type RM Length L Ch R = 1 ,424     ,536.6,564.79,302.96
XS GIS Cut Line= 4
1573357.91549911743307.7610098871572992.19770128743795.384740338
1572935.93342471743861.0263963641572817.15328527744186.108883321
#Sta/Elev= 30
       0  277.48     140  274.99  148.75  274.55     210   273.9  236.25  273.13
   297.5  272.55     385  270.92     420  271.36  446.25  271.11  463.75  271.49
  481.25  271.17     490  270.62     525   270.6  551.25  271.48   577.5  270.88
     595  269.42  603.75  269.39  627.97  270.52  637.19     270  645.99  268.56
  655.63   267.4  664.85  267.58  677.25  269.01  695.98  272.52  703.44  272.83
  733.25  272.25  777.96  273.76  845.04  278.11   882.3  279.83 1042.09   290.3
#Mann= 3 , 0 , 0
       0      .1       0  645.99    .035       0  677.25      .1       0
Bank Sta=645.99,677.25
XS Rating Curve= 0 ,0
Exp/Cntr=0.3,0.1

Type RM Length L Ch R = 1 ,-141    ,268.51,271.83,165.39
XS GIS Cut Line= 4
1572348.28431363743038.9427994941572613.97673088743514.063357368
1572629.60569659743632.8434968441572673.36680061744114.215641022
#Sta/Elev= 30
       0  314.23    40.1  309.59   88.22  305.12  208.52  290.66  248.63  286.58
  272.69  285.03  304.77  281.47  344.87  277.95  368.93  276.67  401.01  273.59
  457.15  271.05  481.21  269.42  537.35  268.94  558.48  267.54  586.73  267.24
  601.07   266.2  614.97  265.19  622.03  265.28  631.14   266.4  643.21   268.2
  650.27  268.61  699.31  268.95  727.43  268.19   769.6   270.2  846.92   269.5
  952.35  271.93  980.47  274.34 1001.55  274.76 1057.78  277.91 1147.52  285.61
#Mann= 3 , 0 , 0
       0      .1       0  601.07    .035       0  631.14      .1       0
Bank Sta=601.07,631.14
XS Rating Curve= 0 ,0
Exp/Cntr=0.3,0.1
Stream Node=StoneRunTrib1   ,Reach1          , 0 , 0 ,Upstream end
Stream Node=StoneRunTrib1   ,Reach1          , 0 , 1 ,Downstream end

Chan Stop Cuts=-1
Use User Specified Reach Order=0