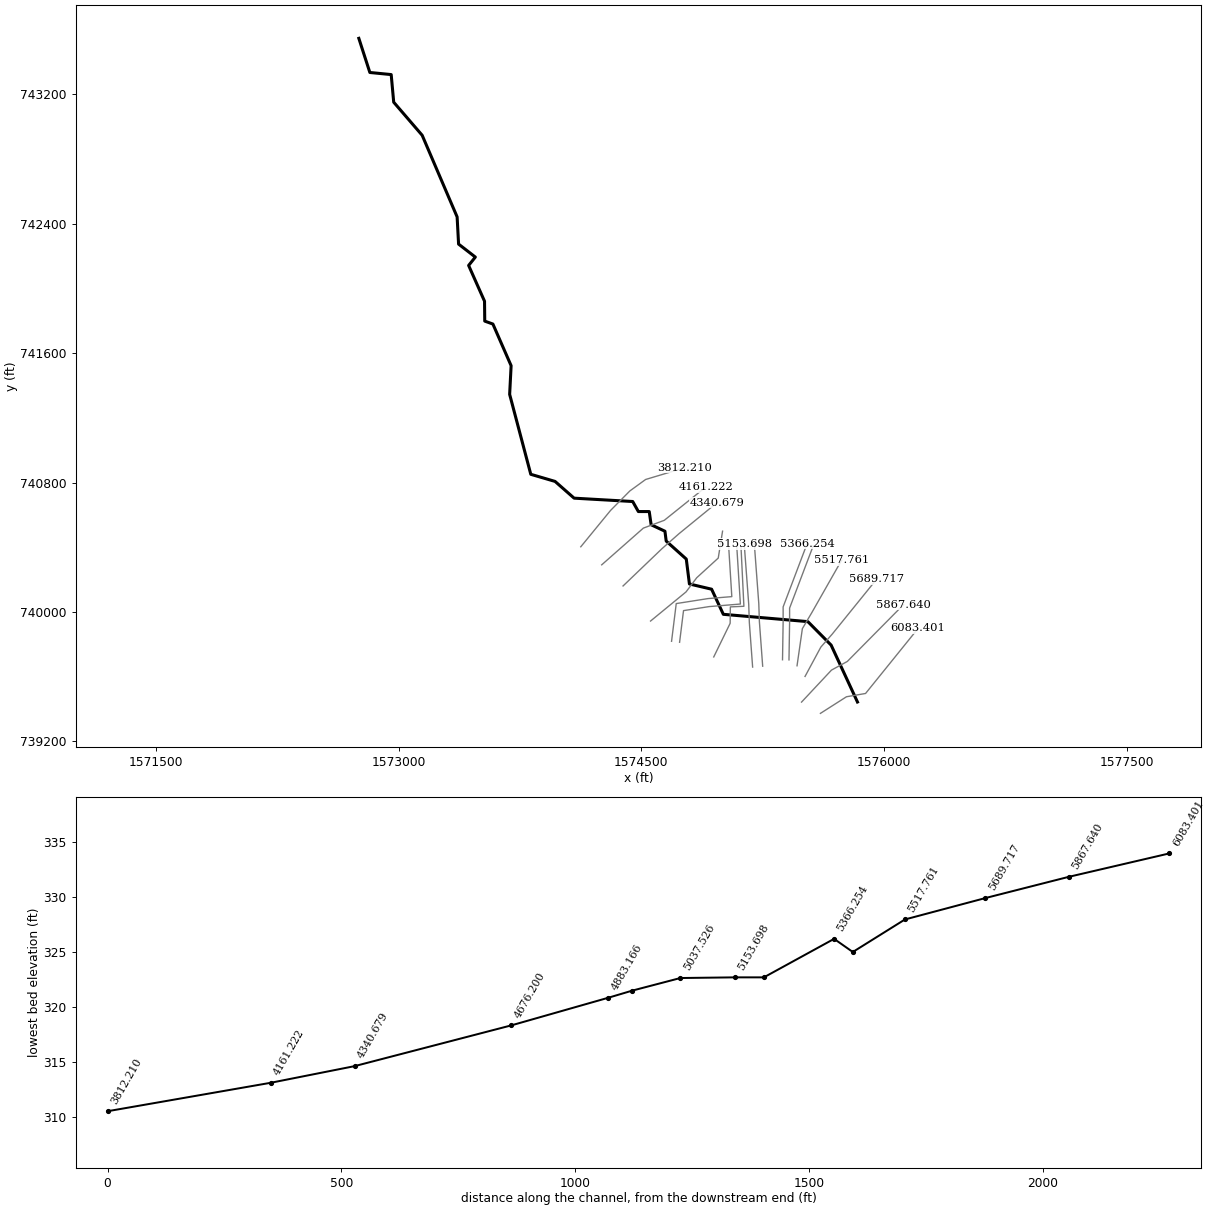
--- StoneRunTrib2.prj (project) ---

Proj Title=Stone Run Trib 2
Current Plan=p01
Default Exp/Contr=0.3,0.1
English Units
Geom File=g01
Flow File=f01
Flow File=f02
Plan File=p01
Plan File=p02
Y Axis Title=Elevation
X Axis Title(PF)=Main Channel Distance
X Axis Title(XS)=Station
BEGIN DESCRIPTION:
Stone Run Trib2 - Georeferenced HEC-RAS model.  MD Stateplane.  Horizontal Datum: NAD83.  Vertical Datum: NAVD88.  Units: Feet.  Created by: Jodell Kormanik-Sonterre, USACE - St. Paul District as part of FEMA Map Modernization study for Cecil County, MD.
END DESCRIPTION:
DSS Export Rating Curves= 0
DSS Export Rating Curve Sorted= 0
DSS Export Volume Flow Curves= 0
DXF OffsetX= 0
DXF OffsetY= 0
DXF ScaleX= 1
DXF ScaleY= 10

--- StoneRunTrib2.p01 (plan) ---

Plan Title=Stone Run Trib 2 Frequency Profiles
Program Version=4.00
Short Identifier=freq
Geom File=g01
Flow File=f01
Subcritical Flow
K Sum by GR= 0
Std Step Tol= 0.01
Critical Tol= 0.01
Num of Std Step Trials= 20
Max Error Tol= 0.3
Flow Tol Ratio= 0.001
Split Flow NTrial= 30
Split Flow Tol= 0.02
Split Flow Ratio= 0.02
Log Output Level= 0
Friction Slope Method= 1
Unsteady Friction Slope Method= 2
Unsteady Bridges Friction Slope Method= 1
Parabolic Critical Depth
Global Vel Dist= 0 , 0 , 0
Global Log Level= 0
CheckData=True
Encroach Param=-1 ,0,0, 0
Computation Interval=1HOUR
Output Interval=1HOUR
Run HTab= 0
Run UNet= 0
Run PostProcess= 0
Run WQNet= 0
UNET Theta= 1
UNET Theta Warmup= 1
UNET ZTol= 0.02
UNET ZSATol= 0.05
UNET MxIter= 20
UNET MaxInSteps= 0
UNET DtIC= 0
UNET DtMin= 0
UNET MaxCRTS= 20
UNET WFStab= 2
UNET SFStab= 1
UNET WFX= 1
UNET SFX= 1
UNET DSS MLevel= 4
UNET DZMax Abort= 100
UNET Convert EG Bridges= 0
UNET Use Existing IB Tables=-1
UNET Froude Reduction=False
UNET Froude Limit= 1
UNET Froude Power= 10
UNET Time Slicing=0,0, 5
Instantaneous Interval=1HOUR
Write IC File= 0
Echo Input=False
Echo Output=False
Write Detailed= 0
Detailed Automatic Start=False, 10
WQ ULTIMATE=-1
WQ Max Comp Step=1HOUR
WQ Output Interval=15MIN
WQ Output Selected Increments= 0
WQ Output face flow=0
WQ Output face velocity=0
WQ Output face area=0
WQ Output face dispersion=0
WQ Output cell volume=0
WQ Output cell surface area=0
WQ Output cell continuity=0
WQ Output face conc=0
WQ Output face dconc_dx=0
WQ Output face courant=0
WQ Output face peclet=0
WQ Output face adv mass=0
WQ Output face disp mass=0
WQ Output cell mass=0
WQ Output cell source sink temp=0
WQ Output cell source sink nsm=0
WQ Output MaxMinRange=-1
WQ Daily Max Min Mean=-1
WQ Daily Range=0
WQ Daily Time=0
WQ Create Restart=0
WQ Fixed Restart=0
WQ System Summary=False
Sorting and Armoring Iterations= 10
XS Update Threshold= 0.02
Hydraulics Update Threshold= 0.02
Energy Slope Method= 1
Volume Change Method= 0
XS Weighting Method= 0
Number of US Weighted Cross Sections= 1
Number of DS Weighted Cross Sections= 1
Upstream XS Weight=0.25
Main XS Weight=0.5
Downstream XS Weight=0.25
Number of DS XS's Weighted with US Boundary= 1
Upstream Boundary Weight= 1
Weight of XSs Associated with US Boundary= 0
Number of US XS's Weighted with DS Boundary= 1
Downstream Boundary Weight= 0.5
Weight of XSs Associated with DS Boundary= 0.5
Sediment Output Level= 4
Mass or Volume Output= 0
Output Increment Type= 1
Profile and TS Output Increment= 10
XS Output Flag= 0
XS Output Increment= 10
Disregard all LS=0
Disregard all Conn=0
Disregard all Breaches=0
Disregard all Pumps=0

--- StoneRunTrib2.p02 (plan) ---

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Plan Title=Stone Run Trib 2 Floodway Profiles
Short Identifier=floodway
Geom File=g01
Flow File=f02
Encroach Param=-1 ,0,0, 2
Encroach River=StoneRunTrib2
Encroach Reach=Reach1
Encroach Node=3392.588
       1     255     348
Encroach Node=3329.114
       1     300     350
Encroach Node=3260.340
       1  386.74     421
Encroach Node=3208.273
       1     405   444.5
Encroach Node=3135.500
       1     370     435
Encroach Node=3031.687
       1     390     465
Encroach Node=2832.038
       1     330     395
Encroach Node=2636.736
       1     280     370
Encroach Node=2351.638
       1     430     510
Encroach Node=2002.508
       1     400     480
Encroach Node=1770.888
       1     415     480
Encroach Node=1541.413
       1     410     500
Encroach Node=1235.391
       1  394.97     440
Encroach Node=1090.020
       1  504.66     550
Encroach Node=943.5313
       1     433     520
Encroach Node=838.3634
       1     380     450
Encroach Node=632.4494
       1     410     510
Encroach Node=410.8312
       1     440   573.6
Encroach Node=196.5021
       1     410     541
Encroach Node=21.46186
       1  576.02  683.76

--- StoneRunTrib2.f01 (steady flow) ---

Flow Title=Stone Run Trib 2 Frequency Flows
Program Version=4.00
Number of Profiles= 5
Profile Names=10yr,50yr,100yr,500yr,100ult
River Rch & RM=StoneRunTrib2,Reach1          ,6083.401
     461     992    1340    2540    1340
River Rch & RM=StoneRunTrib2,Reach1          ,5037.526
     461     998    1370    2710    1440
River Rch & RM=StoneRunTrib2,Reach1          ,4676.200
     621    1320    1760    3290    2030
River Rch & RM=StoneRunTrib2,Reach1          ,3031.687
     625    1440    1990    3970    2280
River Rch & RM=StoneRunTrib2,Reach1          ,21.46186
     721    1640    2240    4410    2530
Boundary for River Rch & Prof#=StoneRunTrib2,Reach1          , 1
Up Type= 0
Dn Type= 3
Dn Slope=0.015
Boundary for River Rch & Prof#=StoneRunTrib2,Reach1          , 2
Up Type= 0
Dn Type= 3
Dn Slope=0.015
Boundary for River Rch & Prof#=StoneRunTrib2,Reach1          , 3
Up Type= 0
Dn Type= 3
Dn Slope=0.015
Boundary for River Rch & Prof#=StoneRunTrib2,Reach1          , 4
Up Type= 0
Dn Type= 3
Dn Slope=0.015
Boundary for River Rch & Prof#=StoneRunTrib2,Reach1          , 5
Up Type= 0
Dn Type= 3
Dn Slope=0.015
DSS Import GetInterval= 0
DSS Import GetPeak= 0
DSS Import FillOption= 0

--- StoneRunTrib2.f02 (steady flow) ---

Flow Title=Stone Run Trib 2 Floodway Flows
Program Version=4.00
Number of Profiles= 2
Profile Names=100yr,100fldwy
River Rch & RM=StoneRunTrib2,Reach1          ,6083.401
    1340    1340
River Rch & RM=StoneRunTrib2,Reach1          ,5037.526
    1370    1370
River Rch & RM=StoneRunTrib2,Reach1          ,4676.200
    1760    1760
River Rch & RM=StoneRunTrib2,Reach1          ,3031.687
    1990    1990
River Rch & RM=StoneRunTrib2,Reach1          ,21.46186
    2240    2240
Boundary for River Rch & Prof#=StoneRunTrib2,Reach1          , 1
Up Type= 0
Dn Type= 1
Dn Known WS=270.94
Boundary for River Rch & Prof#=StoneRunTrib2,Reach1          , 2
Up Type= 0
Dn Type= 1
Dn Known WS=271.94
DSS Import GetInterval= 0
DSS Import GetPeak= 0
DSS Import FillOption= 0

--- StoneRunTrib2.g01 (geometry) ---

Geom Title=Stone Run Trib 2 Geometry
Program Version=4.00

River Reach=StoneRunTrib2   ,Reach1
Reach XY= 30
1575835.85650836739443.593133256 1575672.8389239739795.504109249
1575529.22819471739940.4086287771575006.53689216739985.691291124
1574934.08463238740140.9461334941574796.94285499740173.290892303
1574777.53599966740327.251944304 1574653.3321258740438.517914668
 1574645.5693837740499.3260612491574560.17922038740539.433562189
1574548.53510721740620.9423544261574481.25800887740620.942354426
1574446.32566932740683.0442913471574084.06437053740703.744937018
1573966.32944836740807.2481652351573816.24976744740851.237037241
1573685.57694179741345.4649520671573694.63347426741522.714230403
1573582.07371357741780.178510651 1573531.6158898741798.291575581
1573530.32209943741921.2016591281573431.99403264742142.439809456
1573473.39532393742194.1914235951573369.89209571742274.406425461
1573360.83556323 742442.599171341573144.77257426742947.177408993
1572968.81708628743151.5962847621572953.29160206743322.376611337
1572821.32498603 743335.314514891572753.19916199743546.434209779

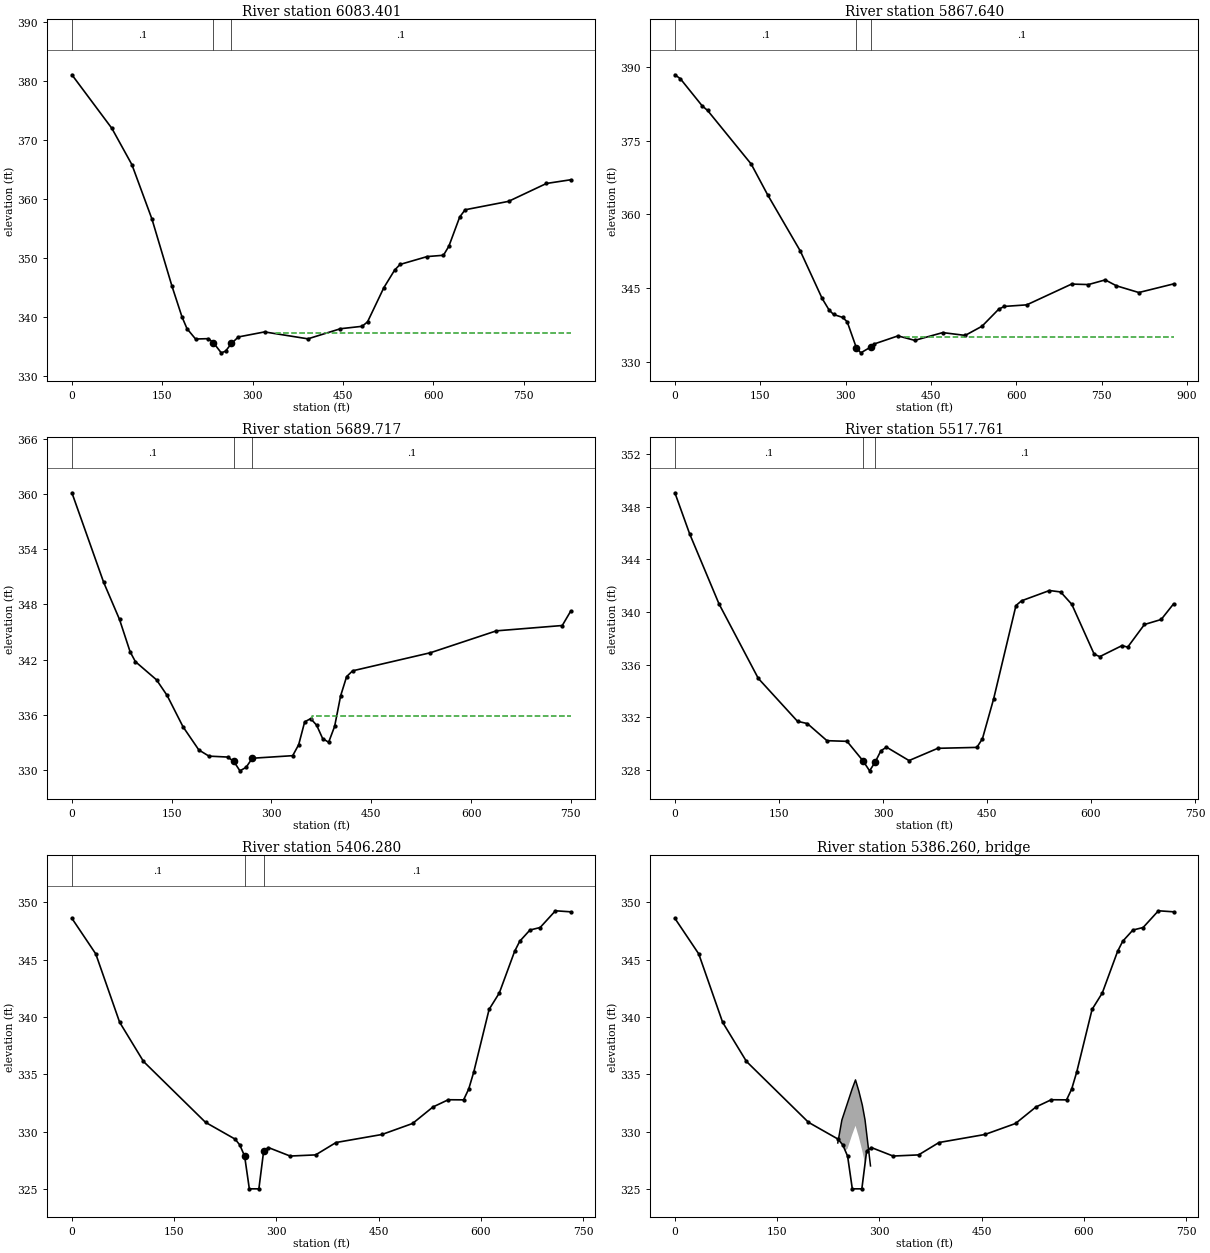
Type RM Length L Ch R = 1 ,6083.401,200.07,215.76,212.29
XS GIS Cut Line= 4
1575606.82360636739373.2707124351575767.90830874739476.009774596
1575885.86797266 739496.303910331576210.57414441 739898.38147451
#Sta/Elev= 30
       0  380.99   66.42  371.91   99.63  365.77  132.84  356.58  166.05  345.23
  182.66  340.04  191.06  338.02  205.26  336.28  226.57  336.34  234.78  335.66
  247.88  333.94  254.98  334.22  264.82  335.53  276.29  336.63  319.75  337.48
  391.73  336.31  445.72  338.02  481.71  338.43   490.7  339.19   517.7  344.96
  535.69  347.95  544.69   348.9  589.68  350.23  616.67  350.45  625.67  351.99
  643.66  356.93  652.66  358.15  724.64  359.57  787.62   362.6  827.57  363.22
#Mann= 3 , 0 , 0
       0      .1       0  234.78    .035       0  264.82      .1       0
#XS Ineff= 2 , 0
                          338.31          337.27
Permanent Ineff=
       F       F
Bank Sta=234.78,264.82
XS Rating Curve= 0 ,0
Exp/Cntr=0.3,0.1

Type RM Length L Ch R = 1 ,5867.640,165.17,177.92,186.71
XS GIS Cut Line= 4
1575490.13232589 739443.031804041575675.31631443739640.899627417
1575772.98184265739694.1717337221576120.51891708740045.513958558
#Sta/Elev= 30
       0  388.42    9.59  387.62   47.94   382.1   57.52  381.15  134.22  370.23
  162.99  363.99  220.51  352.53  258.86  342.88  271.01  340.54  278.98  339.62
  294.93  339.02   302.9  338.13  318.85  332.89  326.82  331.81  344.27  332.99
  350.74  333.63   392.1  335.26  421.64  334.35  470.87  335.93  510.25  335.36
  539.79  337.22  569.33  340.71  579.18  341.26  618.56  341.58  697.33  345.81
  726.87  345.71  756.41  346.66   776.1  345.46  815.48  344.09  876.45  345.84
#Mann= 3 , 0 , 0
       0      .1       0  318.85    .035       0  344.27      .1       0
#XS Ineff= 2 , 0
                          402.71          335.04
Permanent Ineff=
       F       F
Bank Sta=318.85,344.27
XS Rating Curve= 0 ,0
Exp/Cntr=0.3,0.1

Type RM Length L Ch R = 1 ,5689.717,161.51,171.96,194.47
XS GIS Cut Line= 4
1575511.69484513739601.579739422 1575609.3603733739782.958577529
1575680.38984838739864.1351204511575954.36068073740202.793510497
#Sta/Elev= 30
       0  360.14    47.7   350.4   71.55  346.36   87.45  342.85    95.4  341.77
   127.2  339.79  143.11  338.09  166.96  334.69  190.81  332.16     206  331.49
  233.91  331.39  243.21  330.93  252.51  329.89  261.81  330.27  271.11  331.26
  331.87  331.54  340.88  332.74  349.88  335.22  358.89  335.57  367.89  334.85
  376.89   333.4   385.9     333   394.9  334.73  403.91  338.05  412.91  340.14
  421.91  340.77  538.96  342.74     638  345.12  737.05   345.7  749.47  347.23
#Mann= 3 , 0 , 0
       0      .1       0  243.21    .035       0  271.11      .1       0
#XS Ineff= 2 , 0
                          360.61          335.83
Permanent Ineff=
       F       F
Bank Sta=243.21,271.11
XS Rating Curve= 0 ,0
Exp/Cntr=0.3,0.1

Type RM Length L Ch R = 1 ,5517.761,88.83,111.48,145.89
XS GIS Cut Line= 4
1575462.22788928739667.5356805471575495.20585985739897.113091037
1575553.55150005739996.0470027181575737.46710514740319.484790936
#Sta/Elev= 30
       0  349.06   21.22  345.95   63.65  340.62  120.22  334.97   176.8  331.71
  190.94  331.54  219.23  330.24  248.19  330.19  271.37   328.7  280.69  327.95
  288.82  328.62  296.95  329.47  305.07  329.75  337.58  328.73     379  329.66
  435.37  329.73  443.42  330.39  459.53  333.41  491.74   340.5  499.79  340.86
  540.05  341.64  556.16  341.53  572.26  340.59  604.47  336.81  612.53  336.62
  644.74  337.46  652.79  337.34  676.95  339.06   701.1  339.44  718.86  340.62
#Mann= 3 , 0 , 0
       0      .1       0  271.37    .035       0  288.82      .1       0
Bank Sta=271.37,288.82
XS Rating Curve= 0 ,0
Exp/Cntr=0.5,0.3

Type RM Length L Ch R = 1 ,5406.280,40.26,40.03,40.57
BEGIN DESCRIPTION:
Ground elevation lowered to accomodate foot bridge clearance.
END DESCRIPTION:
XS GIS Cut Line= 4
1575412.46411079739703.9909767811575416.27194811739936.269055605
1575416.27194811 740024.092944891575562.10578004740408.792535856
#Sta/Elev= 30
       0  348.59      35  345.49   70.01  339.53  105.01  336.11  196.03   330.8
  239.31  329.34  246.31  328.83  253.41  327.85  260.31     325  274.31     325
  281.31  328.29  288.31   328.6  320.13  327.86  357.56  327.96  387.51  329.04
  454.88  329.74   499.8   330.7  529.74  332.14   552.2  332.77  574.66  332.76
  582.15   333.7  589.63   335.2  612.09  340.65  627.06  342.08  649.52  345.71
  657.01  346.59  671.98  347.57  686.95  347.79  709.41  349.25  731.55  349.16
#Mann= 3 , 0 , 0
       0      .1       0  253.41    .035       0  281.31      .1       0
Bank Sta=253.41,281.31
XS Rating Curve= 0 ,0
Exp/Cntr=0.5,0.3

Type RM Length L Ch R = 3 ,5386.260,,,
BEGIN DESCRIPTION:
Foot Bridge. MDE Bridge #: CE042407FS-2
Bridge Data obtained from bridge surveys
END DESCRIPTION:
Bridge Culvert--1,0,-1,-1, 0
Deck Dist Width WeirC Skew NumUp NumDn MinLoCord MaxHiCord MaxSubmerge Is_Ogee
20,6,2.6,0, 10, 10, , , 0.98, 0, 0,0,,
     239     245     250     255     260     265     270     275     279     287
     329     331   331.9   332.8   333.7   334.5   333.5   332.3     331     327
             327   327.9   328.8   329.7   330.5   329.5   328.3     327
     239     245     250     255     260     265     270     275     279     287
     329     331   331.9   332.8   333.7   334.5   333.5   332.3     331     327
             327   327.9   328.8   329.7   330.5   329.5   328.3     327
BR Coef=-1 , 0 , 0 ,, 0 ,,,0.8,0,,0,
WSPro=,,,, 1 ,,,, 0 ,,,, 0 ,,,,-1 ,-1 ,-1 , 0 , 0 , 0 , 0 , 0
BC Design=,, 0 ,, 0 ,,,,,,
BC Use User HTab Curves=0
BC User HTab FreeFlow(D)= 0

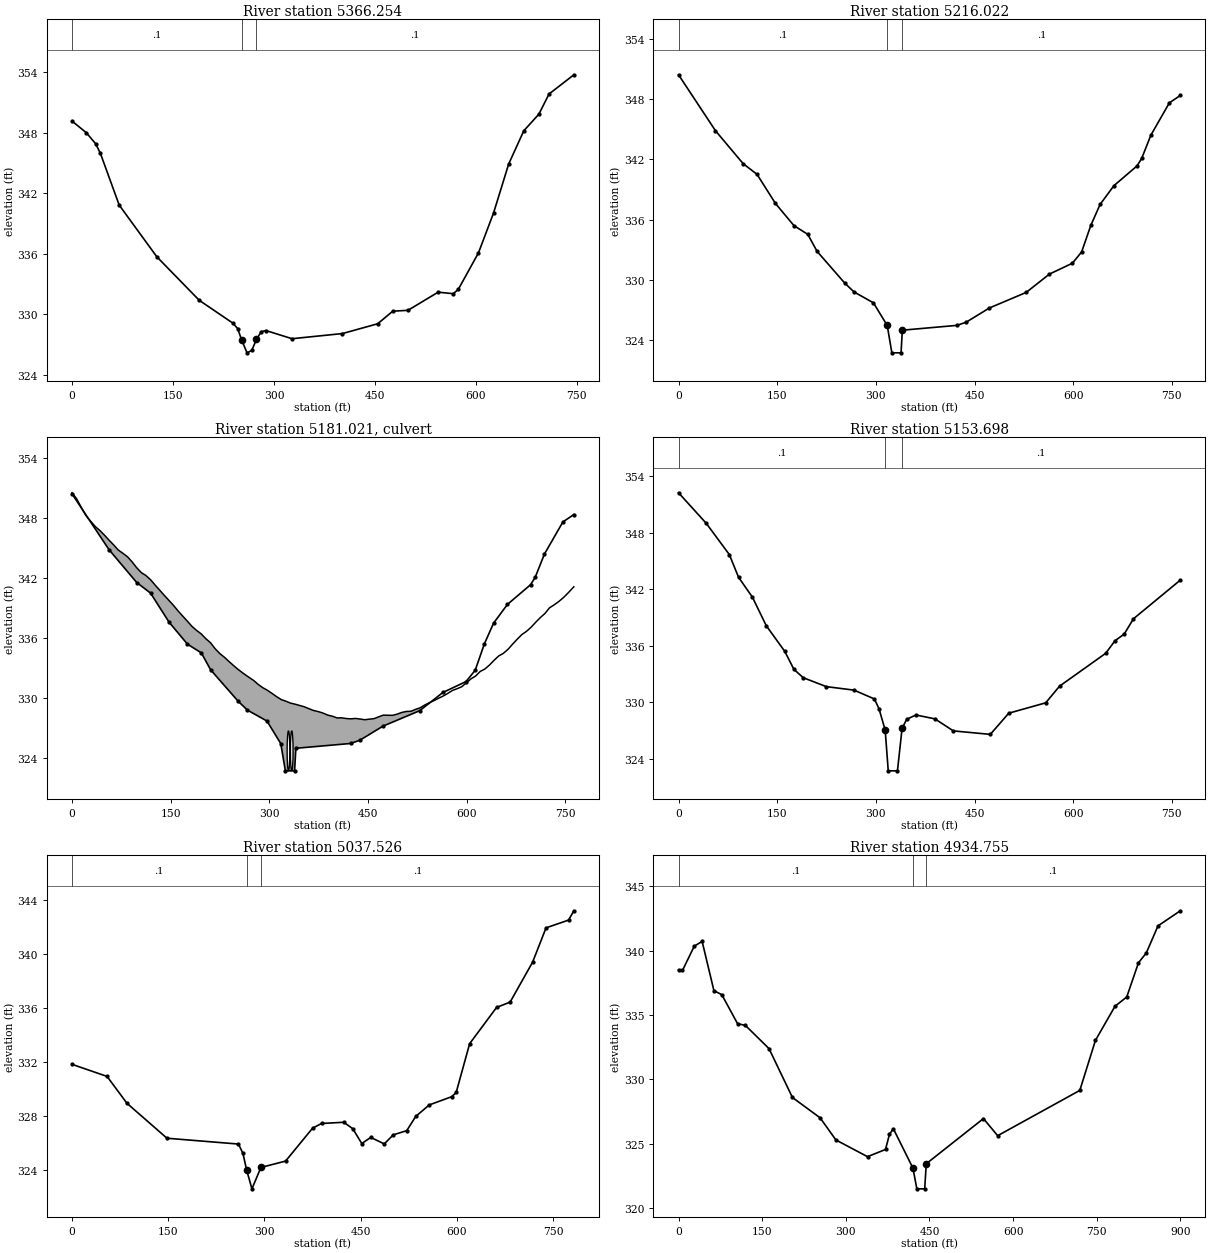
Type RM Length L Ch R = 1 ,5366.254,149.38,150.23,177.6
XS GIS Cut Line= 4
1575372.46948463739704.6466263681575376.27194811739936.596902415
1575376.27194811 740031.420234741575524.70308439 740422.97133553
#Sta/Elev= 30
       0  349.15      21  348.01      35  346.91   42.01  345.97   70.01  340.83
  126.02   335.7  189.03  331.39  238.98  329.13  245.98   328.6  252.14  327.43
  259.98  326.19  266.98  326.43  273.98  327.52  280.98  328.28  287.98   328.4
   326.8  327.59  401.67   328.1  454.07  329.07  476.53  330.32  498.98   330.4
   543.9   332.2  566.36  332.05  573.85  332.48  603.79  336.09  626.25  340.05
  648.71   344.9  671.16  348.19  693.62  349.84   708.6  351.83  745.55  353.74
#Mann= 3 , 0 , 0
       0      .1       0  252.14    .035       0  273.98      .1       0
Bank Sta=252.14,273.98
XS Rating Curve= 0 ,0
Exp/Cntr=0.5,0.3

Type RM Length L Ch R = 1 ,5216.022,64.55,62.33,62.37
BEGIN DESCRIPTION:
Ground elevation lowered to accomodate culvert opening.
END DESCRIPTION:
XS GIS Cut Line= 4
1575249.79835723739665.0358054191575229.55557851739939.578491852
1575225.74978448740052.4837146851575197.79180534740426.103982136
#Sta/Elev= 30
       0  350.44   56.15  344.86   98.27  341.57  119.32  340.51   147.4   337.6
  175.48  335.39  196.53  334.52  210.57  332.83  252.68  329.66  266.72  328.78
   296.3  327.69  317.31  325.43  324.32   322.7  338.32   322.7  340.26  324.96
  423.35  325.44  437.39  325.76  472.49  327.17  528.65  328.73  563.75  330.55
  598.84  331.64  612.88  332.77  626.92  335.43  640.96  337.51  662.02  339.38
  697.12  341.35  704.14  342.09  718.18  344.42  746.26  347.64  762.92  348.38
#Mann= 3 , 0 , 0
       0      .1       0  317.31    .035       0  340.26      .1       0
Bank Sta=317.31,340.26
XS Rating Curve= 0 ,0
Exp/Cntr=0.5,0.3

Type RM Length L Ch R = 2 ,5181.021,,,
BEGIN DESCRIPTION:
Hopewell Rd.  MDE Bridge#: CE042407FS-1
Road Profile taken from DEM.
Structure detail obtained from bridge surveys.
END DESCRIPTION:
Bridge Culvert--1,0,-1,-1, 0
Deck Dist Width WeirC Skew NumUp NumDn MinLoCord MaxHiCord MaxSubmerge Is_Ogee
20,24,2.6,0, 109, 109, , , 0.98, 0, 0.5,0.5,,
       0    7.02   14.04   21.06   28.08    35.1   42.11   49.13   56.15   63.17
   70.19   77.21   84.23   91.25   98.27  105.29   112.3  119.32  126.34  133.36
  140.38   147.4  154.42  161.44  168.46  175.48  182.49  189.51  196.53  203.55
  210.57  217.59  224.61  231.63  238.65  245.67  252.68   259.7  266.72  275.99
  282.99  289.99     297     304  311.01  318.01  325.01  332.02  339.02  346.03
  353.03  360.03  367.04  374.04  381.05  388.94  395.96  402.98     410  417.01
  424.03  431.05  438.07  445.09  452.11  459.13  466.15  473.17  480.19  487.21
  494.23  501.25  508.27  515.29  522.31  529.33  536.35  543.37  550.39  557.41
  564.43  571.45  578.46  585.48   592.5  599.52  606.54  613.56  620.58   627.6
  634.62  641.64  648.66  655.68   662.7  669.72  676.74  683.76  690.78   697.8
  704.82  711.84  718.86  725.88   732.9  739.92  746.94  753.95  762.88
  350.56  349.95  349.09  348.28  347.72  347.19  346.79  346.32  345.82  345.34
  344.83   344.5  344.15  343.64  343.05  342.56  342.27  341.85  341.31  340.79
  340.27  339.77  339.26   338.7  338.19  337.68  337.16  336.76  336.41  335.93
  335.53  334.93  334.45  334.08  333.65  333.24  332.85   332.5  332.17  331.76
  331.36  331.03  330.77  330.46  330.13  329.84  329.68  329.49  329.38  329.25
  329.12  328.93  328.75  328.64   328.5  328.28  328.17     328  328.01  327.94
  327.91  327.95  327.89  327.82  327.88  327.93  328.11  328.28  328.27  328.26
  328.38  328.55  328.65  328.67  328.86  329.02   329.3  329.53  329.74  329.98
   330.2  330.47  330.76  330.93  331.13  331.52  331.92   332.2  332.66   332.9
   333.3  333.78  334.21  334.47  334.87  335.39  335.88  336.35  336.67  337.08
  337.58  338.05  338.46  339.03  339.33  339.66  340.05  340.51  341.14
                                                                                
                                                                                
                                                                                
                                                                                
                                                                                
                                                                                
                                                                                
                                                                                
                                                                                
                                                                                
                                                                        
       0    7.02   14.04   21.06   28.08    35.1   42.11   49.13   56.15   63.17
   70.19   77.21   84.23   91.25   98.27  105.29   112.3  119.32  126.34  133.36
  140.38   147.4  154.42  161.44  168.46  175.48  182.49  189.51  196.53  203.55
  210.57  217.59  224.61  231.63  238.65  245.67  252.68   259.7  266.72  275.99
  282.99  289.99     297     304  311.01  318.01  325.01  332.02  339.02  346.03
  353.03  360.03  367.04  374.04  381.05  388.94  395.96  402.98     410  417.01
  424.03  431.05  438.07  445.09  452.11  459.13  466.15  473.17  480.19  487.21
  494.23  501.25  508.27  515.29  522.31  529.33  536.35  543.37  550.39  557.41
  564.43  571.45  578.46  585.48   592.5  599.52  606.54  613.56  620.58   627.6
  634.62  641.64  648.66  655.68   662.7  669.72  676.74  683.76  690.78   697.8
  704.82  711.84  718.86  725.88   732.9  739.92  746.94  753.95  762.88
  350.56  349.95  349.09  348.28  347.72  347.19  346.79  346.32  345.82  345.34
  344.83   344.5  344.15  343.64  343.05  342.56  342.27  341.85  341.31  340.79
  340.27  339.77  339.26   338.7  338.19  337.68  337.16  336.76  336.41  335.93
  335.53  334.93  334.45  334.08  333.65  333.24  332.85   332.5  332.17  331.76
  331.36  331.03  330.77  330.46  330.13  329.84  329.68  329.49  329.38  329.25
  329.12  328.93  328.75  328.64   328.5  328.28  328.17     328  328.01  327.94
  327.91  327.95  327.89  327.82  327.88  327.93  328.11  328.28  328.27  328.26
  328.38  328.55  328.65  328.67  328.86  329.02   329.3  329.53  329.74  329.98
   330.2  330.47  330.76  330.93  331.13  331.52  331.92   332.2  332.66   332.9
   333.3  333.78  334.21  334.47  334.87  335.39  335.88  336.35  336.67  337.08
  337.58  338.05  338.46  339.03  339.33  339.66  340.05  340.51  341.14
                                                                                
                                                                                
                                                                                
                                                                                
                                                                                
                                                                                
                                                                                
                                                                                
                                                                                
                                                                                
                                                                        
BR Coef=-1 , 0 , 0 ,, 0 ,,,0.8,0,,0,
WSPro=,,,, 1 ,,,, 0 ,,,, 0 ,,,,-1 ,-1 ,-1 , 0 , 0 , 0 , 0 , 0
Multiple Barrel Culv=1,4,,36,0.025,0.9,1,2,3,322.7,322.7, 2,Culvert #1  , 0 ,20
     329     323     334     328
Culvert Bottom n=0.025
BC Design=,, 0 ,, 0 ,,,,,,
BC Use User HTab Curves=0
BC User HTab FreeFlow(D)= 0

Type RM Length L Ch R = 1 ,5153.698,122.51,116.17,29.48
BEGIN DESCRIPTION:
Ground elevation lowered to accomodate culvert opening.
END DESCRIPTION:
XS GIS Cut Line= 4
1575187.68523379739659.5208223311575167.33240443739935.556071803
1575163.52798945740048.420381442 1575135.6847444740420.507384509
#Sta/Elev= 30
       0  352.22   42.11  348.98   77.21  345.66   91.25  343.25   112.3  341.14
  133.36  338.11  161.44  335.39  175.48  333.47  189.51  332.59  224.61  331.64
  266.72  331.27   297.8  330.33   304.8  329.28  314.14  327.03  318.81   322.7
  332.82   322.7  339.82   327.2  346.82  328.17  360.83  328.63  389.71  328.22
  417.79  326.94  473.95  326.57  502.03  328.82  558.18  329.92  579.24  331.69
  649.44  335.18  663.48  336.51  677.52  337.22  691.55  338.84  762.84  342.95
#Mann= 3 , 0 , 0
       0      .1       0  314.14    .035       0  339.82      .1       0
Bank Sta=314.14,339.82
XS Rating Curve= 0 ,0
Exp/Cntr=0.5,0.3

Type RM Length L Ch R = 1 ,5037.526,179.05,102.77,21.58
XS GIS Cut Line= 5
1574947.26419505 739722.076170341575048.73487374739930.091061592
1575050.00325724740031.5617402641575133.71656708740035.366890714
1575115.95919836740400.661333874
#Sta/Elev= 30
       0  331.84   54.52  330.95   85.67  328.96  147.98  326.38  259.45  325.95
  266.45  325.26  272.06  324.06  280.45  322.64  294.45  324.22  332.92  324.69
  374.97  327.12  388.98  327.47  423.73  327.56  437.75  327.08  451.76  325.99
  465.78  326.44  486.81  325.96  500.82  326.63  521.85  326.94  535.86  327.99
  556.89  328.84  591.93  329.45  598.94  329.76  619.96  333.37  662.01  336.05
  683.04  336.44  718.08  339.39   739.1  341.93  774.14   342.5  782.45  343.19
#Mann= 3 , 0 , 0
       0      .1       0  272.06    .035       0  294.45      .1       0
Bank Sta=272.06,294.45
XS Rating Curve= 0 ,0
Exp/Cntr=0.5,0.3

Type RM Length L Ch R = 1 ,4934.755,50.99,51.59,69.75
BEGIN DESCRIPTION:
Ground elevation lowered to accomodate culvert opening.
END DESCRIPTION:
XS GIS Cut Line= 5
  1574736.154066739812.8537482771574760.46764804740008.520194352
1574918.52181649740033.3572779741575112.00463687740049.240196034
1575090.17479201740397.153348699
#Sta/Elev= 30
       0  338.51    7.05  338.47   28.22  340.36   42.32  340.73   63.48   336.9
   77.59  336.59  105.81  334.34  119.92   334.2  162.24   332.4  204.26   328.6
  253.86  327.02   282.2   325.3  338.89     324  371.21  324.56  378.24  325.74
  385.26  326.17  420.38  323.11   427.4   321.5  441.45   321.5  444.28  323.45
   546.8  326.96  572.34  325.63  719.63  329.15  747.69  333.04  782.75  335.69
   803.8  336.41  824.84  339.07  838.86  339.83  859.91  341.94   899.9  343.11
#Mann= 3 , 0 , 0
       0      .1       0  420.38    .035       0  444.28      .1       0
Bank Sta=420.38,444.28
XS Rating Curve= 0 ,0
Exp/Cntr=0.5,0.3

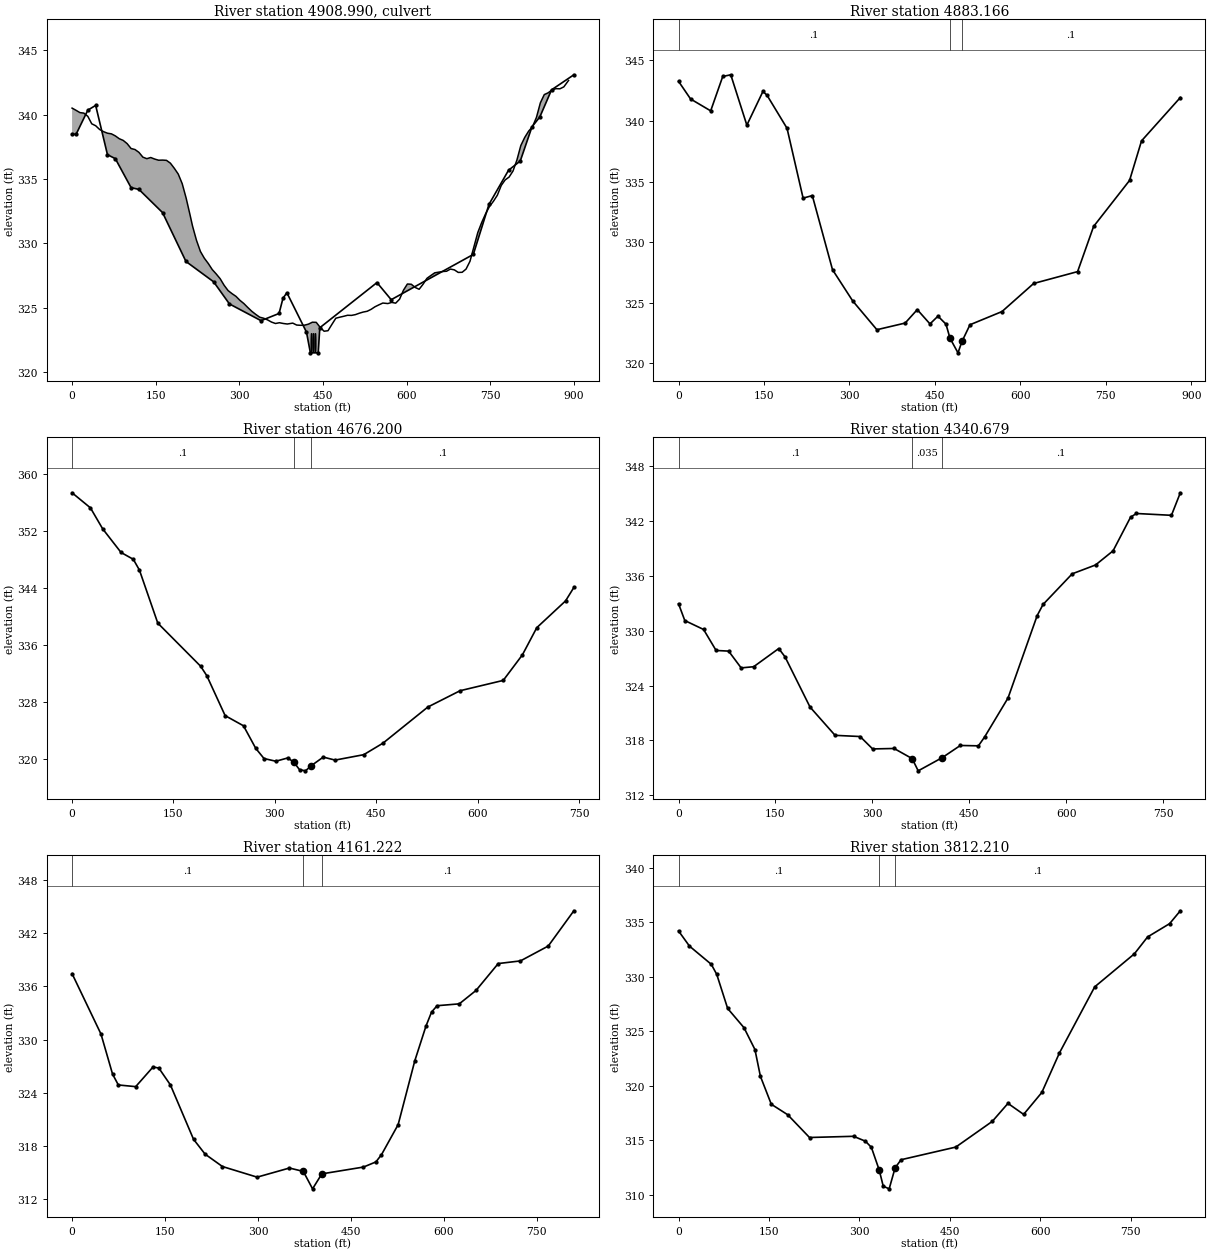
Type RM Length L Ch R = 2 ,4908.990,,,
BEGIN DESCRIPTION:
Cemetery Ln. MDE Bridge #: CE042407FS-3
Bridge Deck Profile taken from DEM.
Structure detail from bridge surveys.
END DESCRIPTION:
Bridge Culvert--1,0,-1,-1, 0
Deck Dist Width WeirC Skew NumUp NumDn MinLoCord MaxHiCord MaxSubmerge Is_Ogee
22,18,2.6,0, 127, 127, , , 0.98, 0, 0,0,,
       0    7.05   14.11   21.16   28.22   35.27   42.32   49.38   56.43   63.48
   70.54   77.59   84.65    91.7   98.75  105.81  112.86  119.92  126.97  134.02
  141.08  148.13  155.18  162.24  169.29  176.35   183.4  190.45  197.51  204.56
  211.62  216.01  223.09  230.18  237.26  244.35  251.43  258.52  265.61  272.69
  279.78  286.86  293.95  301.04  308.12  315.21  322.29  329.38  336.47  343.55
  350.64  357.72  364.81   371.9  378.98  386.07  395.76  402.78  409.81  416.83
  423.85  430.88   437.9  444.92  451.95  458.97  465.99  473.02  480.04  487.06
  494.09  501.11  508.14  515.16  522.18  529.21  536.23  543.25  550.28   557.3
  566.29  573.31  580.32  587.34  594.35  601.36  608.38  615.39   622.4  629.42
  636.43  643.45  650.46  657.47  664.49   671.5  678.51  685.53  692.54  699.56
  706.57  713.58   720.6  727.61  734.62  741.64  748.65  755.67  762.68  769.69
  776.71  783.72  790.74  797.75  804.76  811.78  818.79   825.8  832.82  839.83
  846.85  853.86  860.87  867.89   874.9  881.91  890.37
  340.52  340.35  340.17  340.13  339.88   339.3  339.15  338.86  338.69  338.57
  338.52  338.36  338.14  338.01  337.76  337.38   337.3  337.08  336.71  336.59
  336.68  336.56  336.47  336.48  336.46  336.24  335.84  335.39  334.65  333.53
  332.21  331.36  330.25  329.38  328.85  328.44  327.97  327.63  327.26  326.75
  326.34   326.1  325.89  325.58  325.33  325.02  324.73  324.49  324.27  324.19
  324.06  323.89  323.78  323.84  323.78  323.74  323.81  323.66  323.64  323.65
  323.73  323.88  323.87  323.48  323.18  323.22  323.71  324.19  324.27  324.34
  324.42  324.41  324.47  324.58  324.67  324.73  324.88  325.08  325.23  325.37
  325.33  325.42  325.36  325.67  326.37  326.85  326.83  326.58  326.44  326.83
  327.29  327.51  327.72  327.77  327.82  327.84  328.01  327.95  327.75  327.76
  328.01  328.61  329.73  330.85  331.63  332.31  332.88  333.28  333.75  334.51
  334.94  335.16  335.63  336.48  337.61  338.24  338.73  339.08   339.8  340.93
  341.57  341.71  341.94  342.03  342.02  342.17  342.67
                                                                                
                                                                                
                                                                                
                                                                                
                                                                                
                                                                                
                                                                                
                                                                                
                                                                                
                                                                                
                                                                                
                                                                                
                                                        
       0    7.05   14.11   21.16   28.22   35.27   42.32   49.38   56.43   63.48
   70.54   77.59   84.65    91.7   98.75  105.81  112.86  119.92  126.97  134.02
  141.08  148.13  155.18  162.24  169.29  176.35   183.4  190.45  197.51  204.56
  211.62  216.01  223.09  230.18  237.26  244.35  251.43  258.52  265.61  272.69
  279.78  286.86  293.95  301.04  308.12  315.21  322.29  329.38  336.47  343.55
  350.64  357.72  364.81   371.9  378.98  386.07  395.76  402.78  409.81  416.83
  423.85  430.88   437.9  444.92  451.95  458.97  465.99  473.02  480.04  487.06
  494.09  501.11  508.14  515.16  522.18  529.21  536.23  543.25  550.28   557.3
  566.29  573.31  580.32  587.34  594.35  601.36  608.38  615.39   622.4  629.42
  636.43  643.45  650.46  657.47  664.49   671.5  678.51  685.53  692.54  699.56
  706.57  713.58   720.6  727.61  734.62  741.64  748.65  755.67  762.68  769.69
  776.71  783.72  790.74  797.75  804.76  811.78  818.79   825.8  832.82  839.83
  846.85  853.86  860.87  867.89   874.9  881.91  890.37
  340.52  340.35  340.17  340.13  339.88   339.3  339.15  338.86  338.69  338.57
  338.52  338.36  338.14  338.01  337.76  337.38   337.3  337.08  336.71  336.59
  336.68  336.56  336.47  336.48  336.46  336.24  335.84  335.39  334.65  333.53
  332.21  331.36  330.25  329.38  328.85  328.44  327.97  327.63  327.26  326.75
  326.34   326.1  325.89  325.58  325.33  325.02  324.73  324.49  324.27  324.19
  324.06  323.89  323.78  323.84  323.78  323.74  323.81  323.66  323.64  323.65
  323.73  323.88  323.87  323.48  323.18  323.22  323.71  324.19  324.27  324.34
  324.42  324.41  324.47  324.58  324.67  324.73  324.88  325.08  325.23  325.37
  325.33  325.42  325.36  325.67  326.37  326.85  326.83  326.58  326.44  326.83
  327.29  327.51  327.72  327.77  327.82  327.84  328.01  327.95  327.75  327.76
  328.01  328.61  329.73  330.85  331.63  332.31  332.88  333.28  333.75  334.51
  334.94  335.16  335.63  336.48  337.61  338.24  338.73  339.08   339.8  340.93
  341.57  341.71  341.94  342.03  342.02  342.17  342.67
                                                                                
                                                                                
                                                                                
                                                                                
                                                                                
                                                                                
                                                                                
                                                                                
                                                                                
                                                                                
                                                                                
                                                                                
                                                        
BR Coef=-1 , 0 , 0 ,, 0 ,,,0.8,0,,0,
WSPro=,,,, 1 ,,,, 0 ,,,, 0 ,,,,-1 ,-1 ,-1 , 0 , 0 , 0 , 0 , 0
Multiple Barrel Culv=1,1.5,,18,0.025,0.9,1,2,3,321.5,321.5, 3,Culvert #1  , 0 ,22
   429.5   486.5     433     490   436.5   493.5
Culvert Bottom n=0.025
BC Design=,, 0 ,, 0 ,,,,,,
BC Use User HTab Curves=0
BC User HTab FreeFlow(D)= 0

Type RM Length L Ch R = 1 ,4883.166,118.88,206.97,231.82
XS GIS Cut Line= 5
1574686.53566839739819.019347981 1574715.4941926740052.066519186
1574912.58739954740083.0383088441575059.03135264740095.059827387
1575040.27292603740394.022251219
#Sta/Elev= 30
       0  343.28   21.16  341.82   56.43  340.84   77.59  343.68    91.7  343.82
  119.92  339.66  148.13  342.44  155.18  342.14  190.45   339.4  218.67  333.63
  234.84  333.84  270.27  327.72   305.7  325.14  348.21  322.76  397.82  323.31
  419.07  324.42  441.38  323.24  455.42  323.88  469.47  323.22  476.49  322.06
  490.54  320.85  497.56  321.79  511.61  323.17   567.8  324.26  623.37  326.58
  700.52  327.56  728.58  331.29   791.7  335.09  812.74  338.36  880.84  341.94
#Mann= 3 , 0 , 0
       0      .1       0  476.49    .035       0  497.56      .1       0
Bank Sta=476.49,497.56
XS Rating Curve= 0 ,0
Exp/Cntr=0.5,0.3

Type RM Length L Ch R = 1 ,4676.200,291.43,335.52,284.12
XS GIS Cut Line= 5
1574556.60208224739944.0432799011574776.03242484 740124.15373452
1574841.98836596740211.672194883 1574975.1686317 740333.43700926
1575001.80468485740499.595245555
#Sta/Elev= 30
       0  357.43   27.17  355.31   45.28  352.36   72.45  349.04   90.56  348.08
   99.62  346.57  126.79  339.11  190.18  333.05  199.23  331.73   226.4  326.11
  253.57  324.68  271.68  321.51  283.88  320.08  301.41   319.7  318.94  320.16
  327.71   319.6  336.47  318.51  345.24  318.35     354  319.09  371.54  320.28
  389.07  319.86  431.41  320.62  459.86  322.24  526.26  327.32  573.93  329.61
  637.73  331.06  666.09  334.65  687.36  338.47  729.89  342.23   742.2  344.12
#Mann= 3 , 0 , 0
       0      .1       0  327.71    .035       0     354      .1       0
Bank Sta=327.71,354
XS Rating Curve= 0 ,0
Exp/Cntr=0.3,0.1

Type RM Length L Ch R = 1 ,4340.679,173.8,179.46,123.4
XS GIS Cut Line= 4
1574386.63869548 740160.936855541574627.63155727740391.782649487
1574732.90738641740484.3746437581574967.55833079740675.900549725
#Sta/Elev= 30
       0  332.96    9.69  331.12   38.77  330.14   58.16  327.84   77.55  327.77
   96.93  325.93  116.32  326.06  155.09  328.05  164.79  327.15  203.56  321.64
  242.33  318.54  281.11  318.41  300.49  317.05  333.72   317.1  361.68  315.99
  371.01  314.65   408.3   316.1  436.26  317.43  464.23  317.39  473.92  318.37
  510.06  322.63  555.24  331.67  564.28  332.88  609.45  336.24   645.6  337.21
   672.7  338.76  699.81  342.45  708.85  342.85  763.06  342.65  776.81  345.12
#Mann= 3 , 0 , 0
       0      .1       0  361.68    .035       0   408.3      .1       0
Bank Sta=361.68,408.3
XS Rating Curve= 0 ,0
Exp/Cntr=0.3,0.1

Type RM Length L Ch R = 1 ,4161.222,220.96,349.01,292.47
XS GIS Cut Line= 4
1574254.72681318740291.580354303 1574512.2086603740518.620997816
1574641.58377559740566.8195701841574897.79723921 740772.29769446
#Sta/Elev= 30
       0  337.44   46.66  330.62   65.33   326.1   74.66  324.87  102.66  324.68
  130.66   326.9  139.99  326.78  158.66  324.88  195.99  318.74  214.65  317.06
  242.65  315.66  298.65  314.46  350.75  315.49  373.16  315.11   388.1  313.14
  403.04  314.83  470.27   315.6  490.32  316.18  499.29  316.99  526.21  320.39
  553.13  327.61  571.08  331.51  580.05  333.09  589.02  333.82  624.91  334.03
  651.83  335.54  687.73  338.58  723.62  338.88  768.48  340.56  809.78  344.54
#Mann= 3 , 0 , 0
       0      .1       0  373.16    .035       0  403.04      .1       0
Bank Sta=373.16,403.04
XS Rating Curve= 0 ,0
Exp/Cntr=0.3,0.1

Type RM Length L Ch R = 1 ,3812.210,211.92,255.93,271.22
XS GIS Cut Line= 5
1574125.35169791740403.1981008351574309.26730299740627.701977372
1574428.49535041740748.1984082911574526.16087863740819.227883339
1574767.15374048740891.525741905
#Sta/Elev= 30
       0  334.22    18.1  332.83   54.29  331.16   63.34  330.24   81.44  327.11
  108.59  325.34  126.69  323.34  135.73  320.89  153.83  318.32  180.98  317.36
  217.18  315.27  290.22  315.38  309.91  314.93  319.76  314.37  332.76  312.29
  339.46   310.8   349.3  310.56  359.15  312.49     369  313.23  459.73  314.39
  520.32  316.75  546.29   318.4  572.25  317.39  602.42   319.4  631.65  323.03
  690.12  329.09  755.89  332.12  777.82  333.67  814.36  334.89   832.1  336.07
#Mann= 3 , 0 , 0
       0      .1       0  332.76    .035       0  359.15      .1       0
Bank Sta=332.76,359.15
XS Rating Curve= 0 ,0
Exp/Cntr=0.3,0.1