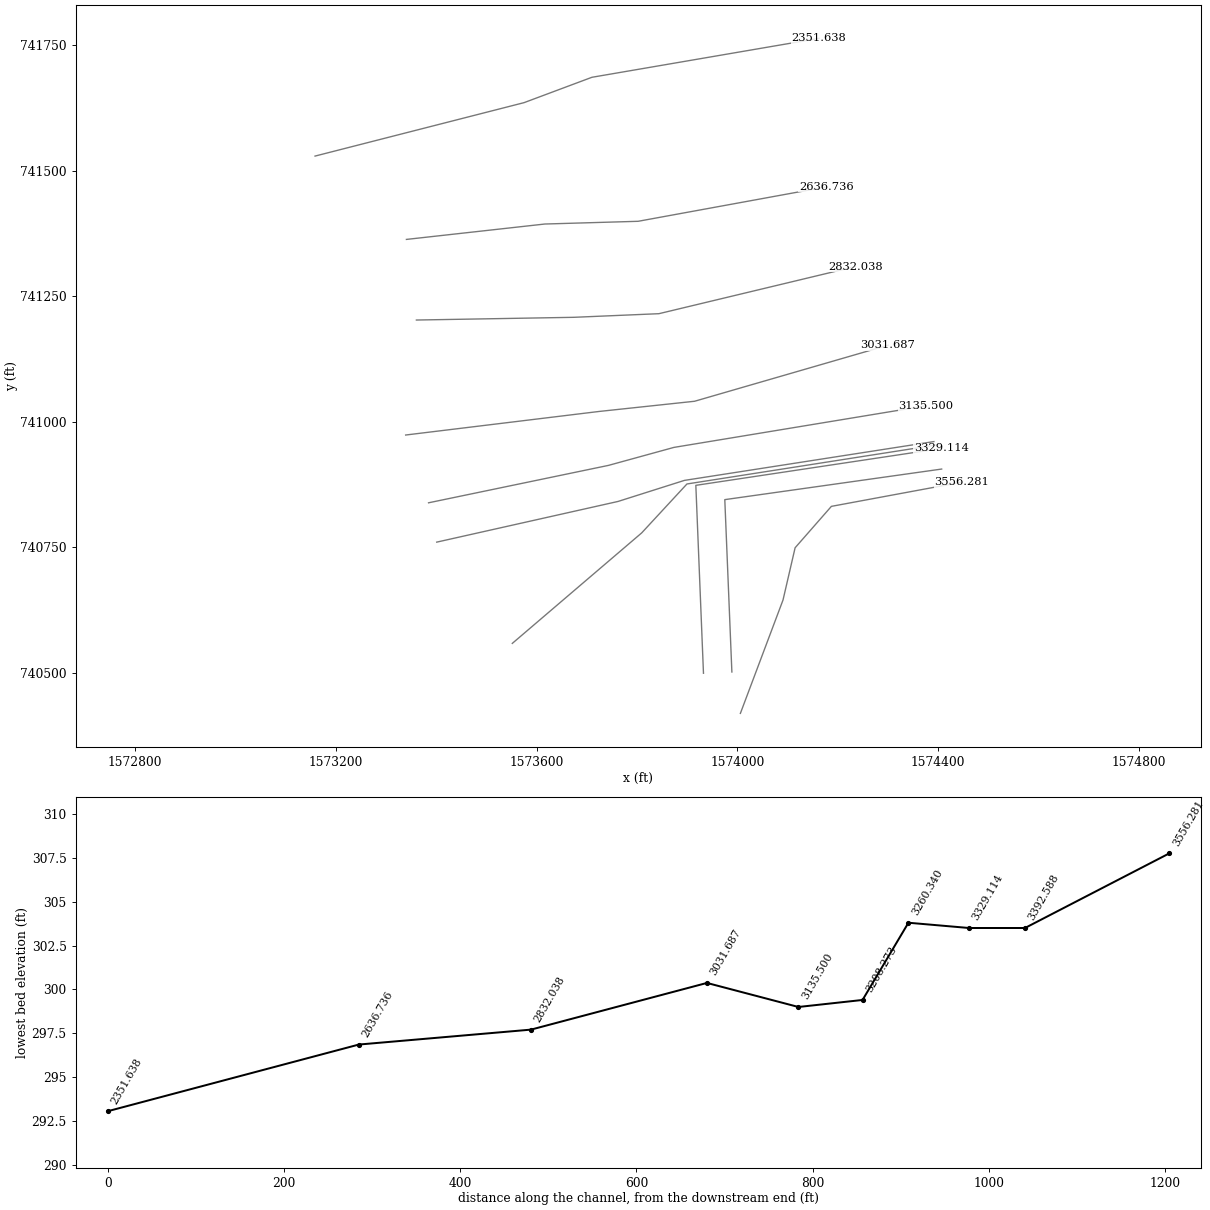
HEC-RAS study StoneRunTrib2.prj: Stone Run Trib 2

--- StoneRunTrib2.g01 (geometry) --- (continued)

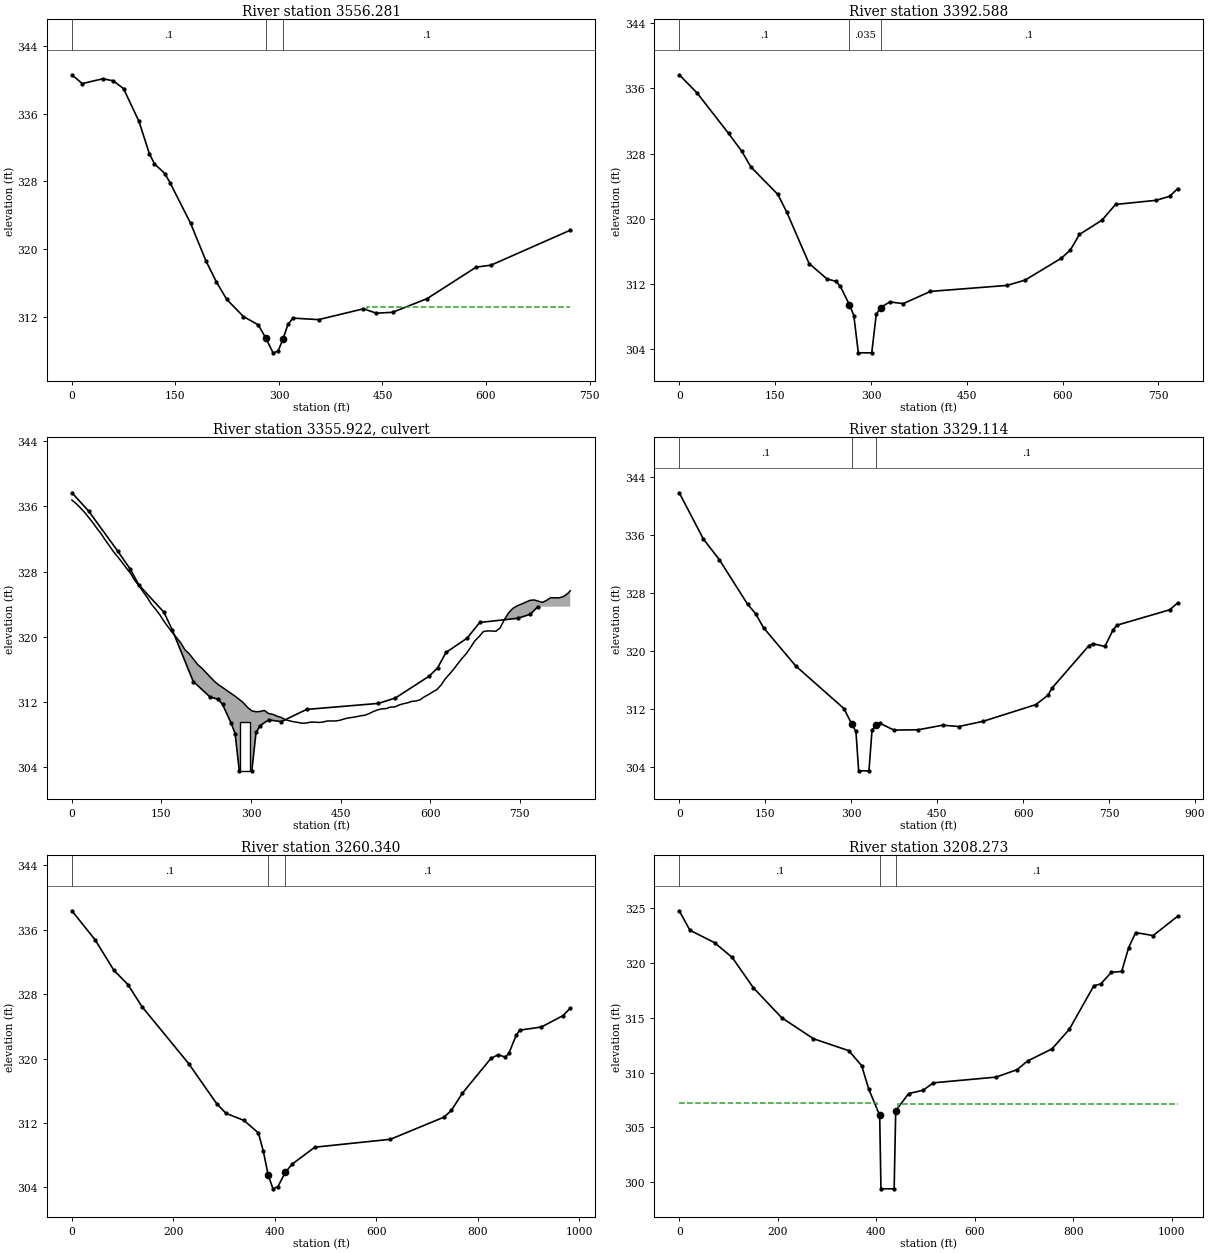
Type RM Length L Ch R = 1 ,3556.281,149.88,163.69,158.41
XS GIS Cut Line= 5
1574006.12365049 740419.687086121574091.10534389 740645.45934613
1574115.20463009740749.4667917641574187.50248861 740831.91171819
 1574447.5211027740880.110290527
#Sta/Elev= 30
       0  340.58   14.96  339.54   44.88  340.11   59.84  339.87   74.79  338.95
   97.23  335.07  112.19  331.28  119.67  330.06  134.63  328.92  142.11  327.85
  172.03  323.04  194.47  318.56  209.42  316.12  224.38  314.06  248.42  312.04
  269.98  311.06  280.83  309.51  291.53  307.75  298.72  307.95  305.91  309.39
  313.09  311.11  320.28  311.85  357.31  311.67  422.48  312.95   441.1  312.43
  464.77  312.54  514.61  314.15   585.8  317.87  607.16   318.1   722.1  322.23
#Mann= 3 , 0 , 0
       0      .1       0  280.83    .035       0  305.91      .1       0
#XS Ineff= 2 , 0
                          428.02          313.16
Permanent Ineff=
       F       F
Bank Sta=280.83,305.91
XS Rating Curve= 0 ,0
Exp/Cntr=0.5,0.3

Type RM Length L Ch R = 1 ,3392.588,70.31,63.47,59.1
BEGIN DESCRIPTION:
Ground elevation lowered to accomodate culvert opening.
END DESCRIPTION:
XS GIS Cut Line= 3
1573989.16816057740502.0954659881573975.06322855740845.315479398
1574407.31286977740906.212528318
#Sta/Elev= 30
       0  337.68   28.02  335.43   77.06  330.48   98.08  328.25  112.09  326.35
  154.13  322.99  168.14  320.81  203.17  314.48  231.19  312.59  245.21  312.29
  252.21  311.66  266.22  309.42  273.23  308.08  280.24   303.5  301.25   303.5
  308.26  308.22  315.27  309.06  329.28  309.76  350.58  309.55  392.99  311.05
  513.17  311.79  541.45  312.45     598  315.13  612.14  316.14  626.28  318.05
  661.62  319.81  682.83  321.74  746.45  322.25  767.66  322.75  780.03  323.68
#Mann= 3 , 0 , 0
       0      .1       0  266.22    .035       0  315.27      .1       0
Bank Sta=266.22,315.27
XS Rating Curve= 0 ,0
Exp/Cntr=0.5,0.3

Type RM Length L Ch R = 2 ,3355.922,,,
BEGIN DESCRIPTION:
Harrington Drive. MDE Bridge #: CE042407FS-4.
END DESCRIPTION:
Bridge Culvert--1,0,-1,-1, 0
Deck Dist Width WeirC Skew NumUp NumDn MinLoCord MaxHiCord MaxSubmerge Is_Ogee
25,27,2.6,0, 120, 120, , , 0.98, 0, 1,1,,
       0    7.01   14.01   21.02   28.02   35.03   42.04   49.04   56.05   63.05
   70.06   77.06   84.07   91.08   98.08  105.09  112.09   119.1  126.11  133.11
  140.12  147.12  154.13  161.14  168.14  175.15  182.15  189.16  196.17  203.17
  210.18  217.18  224.19  231.19   238.2  245.21  252.21  259.22  266.22  273.23
  280.24  287.24  294.25  301.25  308.26  315.27  322.27  329.28  336.28  343.29
   350.3   357.3  364.31  370.68  377.75  384.82  391.89  398.96  406.03   413.1
  420.16  427.23   434.3  441.37  448.44  455.51  462.58  469.65  476.72  483.79
  490.86  497.92  504.99  512.06  519.13   526.2  533.27  540.34  547.41  554.48
  561.55  568.62  575.69  582.75  589.82  596.89  603.96  611.03   618.1  625.17
  632.24  639.31  646.38  653.45  660.52  667.58  674.65  681.72  688.79  695.86
  702.93     710  717.07  724.14  731.21  738.28  745.35  752.41  759.48  766.55
  773.62  780.69  787.76  794.83   801.9  808.97  816.04  823.11  830.18  834.37
  336.78  336.36  335.84  335.29  334.66     334  333.29  332.63  331.85  331.13
   330.4  329.77  329.13  328.43  327.79  326.93  326.26  325.53  324.82  323.99
  323.37  322.69  321.88  321.18  320.52  319.88  319.25  318.39  317.91  317.26
  316.59  316.15  315.61  315.06  314.53  314.09  313.75  313.39  313.03  312.68
  312.28  311.85  311.28  310.88  310.76   310.8  310.93  310.54  310.45  310.22
  310.07  309.78  309.65  309.54  309.46  309.35  309.37  309.48  309.49  309.45
  309.49  309.63  309.63  309.63  309.71  309.87     310  310.07  310.16  310.27
  310.34  310.55   310.8     311  311.12  311.15  311.34  311.35  311.58  311.74
  311.85  312.03  312.08  312.23  312.59  312.87   313.2  313.49  314.05  314.82
  315.39  316.01  316.69  317.35  317.93  318.69  319.48     320  320.62   320.7
  320.69  320.66  321.09  322.11  322.92  323.47  323.78  323.99  324.22  324.45
  324.51  324.36  324.21  324.46  324.79  324.77  324.77  324.93   325.3  325.64
                                                                                
                                                                                
                                                                                
                                                                                
                                                                                
                                                                                
                                                                                
                                                                                
                                                                                
                                                                                
                                                                                
                                                                                
       0    7.01   14.01   21.02   28.02   35.03   42.04   49.04   56.05   63.05
   70.06   77.06   84.07   91.08   98.08  105.09  112.09   119.1  126.11  133.11
  140.12  147.12  154.13  161.14  168.14  175.15  182.15  189.16  196.17  203.17
  210.18  217.18  224.19  231.19   238.2  245.21  252.21  259.22  266.22  273.23
  280.24  287.24  294.25  301.25  308.26  315.27  322.27  329.28  336.28  343.29
   350.3   357.3  364.31  370.68  377.75  384.82  391.89  398.96  406.03   413.1
  420.16  427.23   434.3  441.37  448.44  455.51  462.58  469.65  476.72  483.79
  490.86  497.92  504.99  512.06  519.13   526.2  533.27  540.34  547.41  554.48
  561.55  568.62  575.69  582.75  589.82  596.89  603.96  611.03   618.1  625.17
  632.24  639.31  646.38  653.45  660.52  667.58  674.65  681.72  688.79  695.86
  702.93     710  717.07  724.14  731.21  738.28  745.35  752.41  759.48  766.55
  773.62  780.69  787.76  794.83   801.9  808.97  816.04  823.11  830.18  834.37
  336.78  336.36  335.84  335.29  334.66     334  333.29  332.63  331.85  331.13
   330.4  329.77  329.13  328.43  327.79  326.93  326.26  325.53  324.82  323.99
  323.37  322.69  321.88  321.18  320.52  319.88  319.25  318.39  317.91  317.26
  316.59  316.15  315.61  315.06  314.53  314.09  313.75  313.39  313.03  312.68
  312.28  311.85  311.28  310.88  310.76   310.8  310.93  310.54  310.45  310.22
  310.07  309.78  309.65  309.54  309.46  309.35  309.37  309.48  309.49  309.45
  309.49  309.63  309.63  309.63  309.71  309.87     310  310.07  310.16  310.27
  310.34  310.55   310.8     311  311.12  311.15  311.34  311.35  311.58  311.74
  311.85  312.03  312.08  312.23  312.59  312.87   313.2  313.49  314.05  314.82
  315.39  316.01  316.69  317.35  317.93  318.69  319.48     320  320.62   320.7
  320.69  320.66  321.09  322.11  322.92  323.47  323.78  323.99  324.22  324.45
  324.51  324.36  324.21  324.46  324.79  324.77  324.77  324.93   325.3  325.64
                                                                                
                                                                                
                                                                                
                                                                                
                                                                                
                                                                                
                                                                                
                                                                                
                                                                                
                                                                                
                                                                                
                                                                                
BR Coef=-1 , 0 , 0 ,, 0 ,,,0.8,0,,0,
WSPro=,,,, 1 ,,,, 0 ,,,, 0 ,,,,-1 ,-1 ,-1 , 0 , 0 , 0 , 0 , 0
Culvert=2,6,18,45,0.014,0.4,1,8,1,303.5,290,303.5,322,Culvert #1  , 0 ,16
Culvert Bottom n=0.014
BC Design=,, 0 ,, 0 ,,,,,,
BC Use User HTab Curves=0
BC User HTab FreeFlow(D)= 0

Type RM Length L Ch R = 1 ,3329.114,84.59,68.77,9.11
BEGIN DESCRIPTION:
Ground elevation lowered to accomodate culvert opening.
END DESCRIPTION:
XS GIS Cut Line= 3
1573932.55740851740499.5952455551573917.33680667740873.768373117
1574406.93283121740947.334615156
#Sta/Elev= 30
       0  341.83   42.03  335.46   70.06  332.59   119.1  326.48  133.11  325.18
  147.12  323.22  203.17  317.96  287.24  312.09  301.25  309.91  308.25  308.93
     313   303.5  330.96   303.5  336.28  309.07  343.28  309.84  350.29  310.05
  374.48  309.12  416.95  309.16  459.43  309.79  487.74  309.61  530.21  310.33
  622.23  312.63  643.47  313.94  650.55  314.92  714.25  320.71  721.33  321.02
  742.57  320.65  756.73   322.9   763.8  323.58  855.82   325.7  869.57  326.65
#Mann= 3 , 0 , 0
       0      .1       0  301.25    .035       0  343.28      .1       0
Bank Sta=301.25,343.28
XS Rating Curve= 0 ,0
Exp/Cntr=0.5,0.3

Type RM Length L Ch R = 1 ,3260.340,64.44,52.07,12.67
XS GIS Cut Line= 4
1573551.50900157740559.046357632 1573809.4330374 740779.09343715
 1573899.6162667740876.4913248121574403.92680278740955.318285033
#Sta/Elev= 30
       0  338.37   46.01  334.74   82.81  330.96  110.42   329.2  138.02  326.46
  230.03  319.38  285.24   314.4  303.65  313.19  339.04  312.31  367.66  310.74
   377.2  308.49  386.74  305.56  396.28   303.8  405.82  304.06  420.78  305.87
  434.43  306.89  478.86  308.98  627.64  309.96  733.92  312.73  748.09  313.57
  769.34  315.67  826.02  320.03  840.19  320.47  854.36  320.17  861.45  320.67
  875.62  322.91  882.71  323.53  925.22  323.92  967.73  325.33  982.21  326.25
#Mann= 3 , 0 , 0
       0      .1       0  386.74    .035       0  420.78      .1       0
Bank Sta=386.74,420.78
XS Rating Curve= 0 ,0
Exp/Cntr=0.5,0.3

Type RM Length L Ch R = 1 ,3208.273,74.71,72.77,133.32
BEGIN DESCRIPTION:
Ground elevation lowered to accomodate culvert.
END DESCRIPTION:
XS GIS Cut Line= 4
 1573400.8649177740760.6822134851573762.30566475740841.707575545
 1573894.5410807 740883.613165111574391.82074358740960.905696988
#Sta/Elev= 30
       0  324.76   21.52  322.99   71.74  321.85  107.61   320.5  150.65  317.73
  208.04  315.01   272.6  313.09  344.34     312  370.41  310.64   385.1  308.47
  407.13  306.11  409.71   299.4   436.5   299.4  439.68  306.52  465.87  308.09
  495.24  308.39  516.21  309.07  643.72  309.59  686.23  310.27  707.48  311.06
  757.07  312.16  792.49  313.96  842.08  317.92  856.25  318.09   877.5  319.14
  898.75  319.23  912.92  321.41  927.09  322.77  962.51   322.5 1012.38  324.26
#Mann= 3 , 0 , 0
       0      .1       0  407.13    .035       0  439.68      .1       0
#XS Ineff= 2 , 0
          402.21  307.21  443.84          307.13
Permanent Ineff=
       F       F
Bank Sta=407.13,439.68
XS Rating Curve= 0 ,0
Exp/Cntr=0.5,0.3

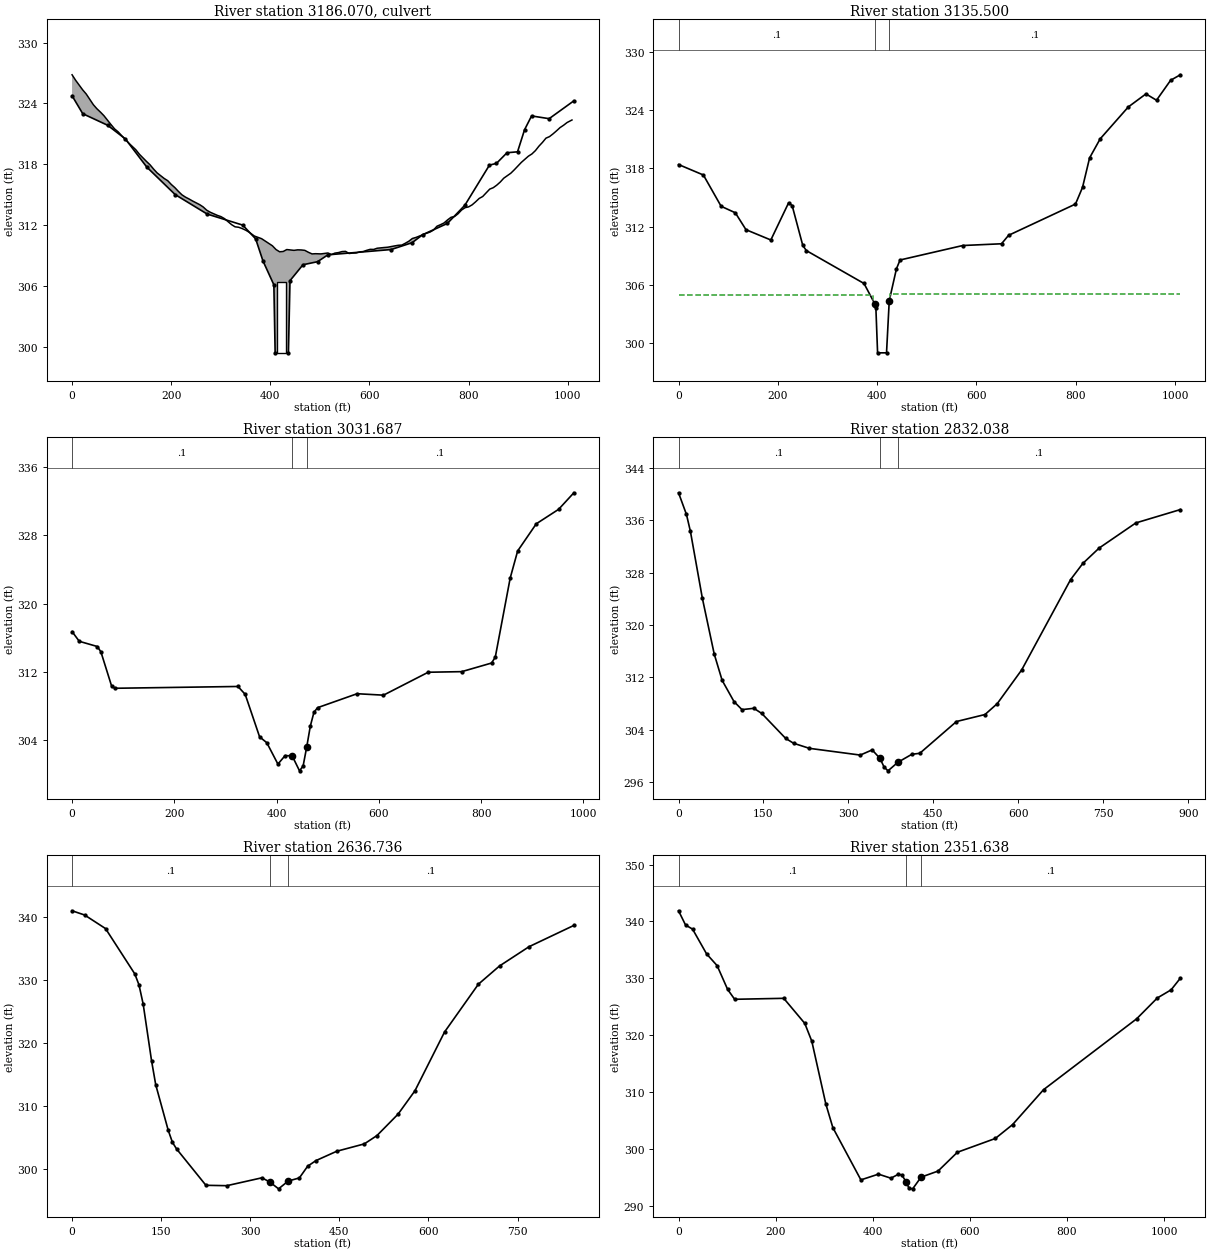
Type RM Length L Ch R = 2 ,3186.070,,,
BEGIN DESCRIPTION:
Rising Sun Rd (Main St).  MDE Bridge #:CE 042407FS-5.
Road Profile taken from DEM.
Structure detail from bridge surveys.
END DESCRIPTION:
Bridge Culvert--1,0,-1,-1, 0
Deck Dist Width WeirC Skew NumUp NumDn MinLoCord MaxHiCord MaxSubmerge Is_Ogee
11,36,2.6,0, 141, 141, , , 0.98, 0, 0,0,,
       0    7.15    14.3   21.45    28.6   35.75    42.9   50.05    57.2   64.35
   71.49   78.64   85.79   92.94  100.09  107.24  114.39  121.54  128.69  135.84
  142.99  150.14  157.29  164.44  171.59  178.74  185.89  193.04  200.18  207.33
  214.48  221.63  228.78  235.93  243.08  250.23  257.38  264.53  271.68  278.83
  285.98  293.13  300.28  307.43  314.58  321.73  328.87  336.02  343.17  350.32
  357.47  367.91  375.17  382.43  389.69  396.95  404.21  411.47  418.72  425.98
  433.24   440.5  447.76  455.02  462.28  469.54   476.8  484.05  491.31  502.07
  509.17  516.26  523.36  530.45  537.55  544.64  551.74  558.83  565.92  573.02
  580.11  587.21   594.3   601.4  608.49  615.59  622.68  629.78  636.87  643.96
  651.06  658.15  665.25  672.34  679.44  686.53  693.63  700.72  707.82  714.91
  722.01   729.1  736.19  743.29  750.38  757.48  764.57  771.67  778.76  785.86
  792.95  800.05  807.14  814.24  821.33  828.42  835.52  842.61  849.71   856.8
   863.9  870.99  878.09  885.18  892.28  899.37  906.47  913.56  920.65  927.75
  934.84  941.94  949.03  956.13  963.22  970.32  977.41  984.51   991.6   998.7
 1008.57
  326.83  326.29  325.81  325.34  324.93  324.41  323.88  323.48  323.15  322.79
  322.35  321.91  321.49   321.2  320.82  320.47  320.09  319.76  319.43  318.99
  318.63  318.28  317.95  317.53  317.15  316.87   316.6  316.38  316.01   315.7
  315.33  314.99  314.76  314.58  314.38   314.2  314.02  313.79  313.47  313.27
  313.12  312.96  312.84  312.64  312.35  312.05  311.83  311.79  311.66   311.5
  311.29  310.92  310.79  310.66  310.43  310.19  309.96  309.59  309.37   309.4
  309.59  309.55  309.51  309.56  309.55  309.51  309.32  309.16  309.18  309.16
   309.2  309.25   309.1  309.24  309.29  309.39  309.41   309.2  309.24  309.25
  309.36  309.39  309.51  309.61   309.6  309.72  309.76  309.79  309.82  309.89
  309.95  310.01  310.03  310.21  310.41  310.68  310.78  310.92  311.06  311.19
  311.31  311.51  311.89  312.04  312.21  312.51  312.77  312.85  313.12  313.49
  313.72   313.8     314   314.3  314.63  314.82  315.18  315.55  315.69  315.94
  316.25  316.63  316.88  317.12  317.46  317.83  318.19  318.49   318.8  319.02
  319.35  319.79  320.16  320.58  320.73     321   321.3  321.62  321.85  322.12
  322.37
                                                                                
                                                                                
                                                                                
                                                                                
                                                                                
                                                                                
                                                                                
                                                                                
                                                                                
                                                                                
                                                                                
                                                                                
                                                                                
                                                                                
        
       0    7.15    14.3   21.45    28.6   35.75    42.9   50.05    57.2   64.35
   71.49   78.64   85.79   92.94  100.09  107.24  114.39  121.54  128.69  135.84
  142.99  150.14  157.29  164.44  171.59  178.74  185.89  193.04  200.18  207.33
  214.48  221.63  228.78  235.93  243.08  250.23  257.38  264.53  271.68  278.83
  285.98  293.13  300.28  307.43  314.58  321.73  328.87  336.02  343.17  350.32
  357.47  367.91  375.17  382.43  389.69  396.95  404.21  411.47  418.72  425.98
  433.24   440.5  447.76  455.02  462.28  469.54   476.8  484.05  491.31  502.07
  509.17  516.26  523.36  530.45  537.55  544.64  551.74  558.83  565.92  573.02
  580.11  587.21   594.3   601.4  608.49  615.59  622.68  629.78  636.87  643.96
  651.06  658.15  665.25  672.34  679.44  686.53  693.63  700.72  707.82  714.91
  722.01   729.1  736.19  743.29  750.38  757.48  764.57  771.67  778.76  785.86
  792.95  800.05  807.14  814.24  821.33  828.42  835.52  842.61  849.71   856.8
   863.9  870.99  878.09  885.18  892.28  899.37  906.47  913.56  920.65  927.75
  934.84  941.94  949.03  956.13  963.22  970.32  977.41  984.51   991.6   998.7
 1008.57
  326.83  326.29  325.81  325.34  324.93  324.41  323.88  323.48  323.15  322.79
  322.35  321.91  321.49   321.2  320.82  320.47  320.09  319.76  319.43  318.99
  318.63  318.28  317.95  317.53  317.15  316.87   316.6  316.38  316.01   315.7
  315.33  314.99  314.76  314.58  314.38   314.2  314.02  313.79  313.47  313.27
  313.12  312.96  312.84  312.64  312.35  312.05  311.83  311.79  311.66   311.5
  311.29  310.92  310.79  310.66  310.43  310.19  309.96  309.59  309.37   309.4
  309.59  309.55  309.51  309.56  309.55  309.51  309.32  309.16  309.18  309.16
   309.2  309.25   309.1  309.24  309.29  309.39  309.41   309.2  309.24  309.25
  309.36  309.39  309.51  309.61   309.6  309.72  309.76  309.79  309.82  309.89
  309.95  310.01  310.03  310.21  310.41  310.68  310.78  310.92  311.06  311.19
  311.31  311.51  311.89  312.04  312.21  312.51  312.77  312.85  313.12  313.49
  313.72   313.8     314   314.3  314.63  314.82  315.18  315.55  315.69  315.94
  316.25  316.63  316.88  317.12  317.46  317.83  318.19  318.49   318.8  319.02
  319.35  319.79  320.16  320.58  320.73     321   321.3  321.62  321.85  322.12
  322.37
                                                                                
                                                                                
                                                                                
                                                                                
                                                                                
                                                                                
                                                                                
                                                                                
                                                                                
                                                                                
                                                                                
                                                                                
                                                                                
                                                                                
        
BR Coef=-1 , 0 , 0 ,, 0 ,,,0.8,0,,0,
WSPro=,,,, 1 ,,,, 0 ,,,, 0 ,,,,-1 ,-1 ,-1 , 0 , 0 , 0 , 0 , 0
Culvert=2,7,18,36,0.014,0.4,1,8,1,299.4,421.8,299,409.9,Culvert #1  , 0 ,11
Culvert Bottom n=0.014
BC Design=,, 0 ,, 0 ,,,,,,
BC Use User HTab Curves=0
BC User HTab FreeFlow(D)= 0

Type RM Length L Ch R = 1 ,3135.500,107.11,103.81,100.5
BEGIN DESCRIPTION:
Ground elevation lowered to accomodate culvert.
END DESCRIPTION:
XS GIS Cut Line= 4
1573384.59263472740839.0098127721573743.26905924740913.523577005
1573873.64237255 740949.31232971 1574375.9632083741032.182518333
#Sta/Elev= 30
       0  318.39   50.05  317.31   85.79  314.09  114.39  313.42  135.84  311.68
  185.89  310.62  221.63  314.44  228.78  314.17  250.23  310.06  257.38  309.53
  373.59  306.14  395.37  304.04  397.48  303.61   400.9     299   418.9     299
  424.41  304.38  438.92  307.66  446.18  308.56  572.48  310.05  650.52  310.23
  664.71   311.1   799.5  314.32  813.69  316.04  827.88  319.07  849.17  321.03
  905.92  324.32   941.4  325.66  962.68  325.01  991.06  327.06 1010.64  327.63
#Mann= 3 , 0 , 0
       0      .1       0  395.37    .035       0  424.41      .1       0
#XS Ineff= 2 , 0
          392.04  304.96  425.32          305.08
Permanent Ineff=
       F       F
Bank Sta=395.37,424.41
XS Rating Curve= 0 ,0
Exp/Cntr=0.5,0.3

Type RM Length L Ch R = 1 ,3031.687,219.96,199.65,201.55
XS GIS Cut Line= 4
1573338.95393832740973.9706683011573724.54251723 741020.90085718
1573914.80003972  741041.19499291574300.38861862741152.812739447
#Sta/Elev= 30
       0  316.71    14.1  315.57   49.36  314.96   56.41  314.33   77.57  310.27
   84.62  310.06  324.38  310.27  338.48  309.35  366.69  304.36  380.79  303.67
  402.51  301.16  416.59  302.16  430.45  302.12  444.75  300.37  451.79  300.94
  458.83  303.17  465.87  305.62  472.91  307.23  479.95  307.78  557.39  309.42
  608.92  309.25  696.37  311.94  761.95  312.01  820.25  313.02  827.54  313.71
  856.69  322.99  871.27  326.17   907.7  329.36  951.43  331.06  981.19     333
#Mann= 3 , 0 , 0
       0      .1       0  430.45    .035       0  458.83      .1       0
Bank Sta=430.45,458.83
XS Rating Curve= 0 ,0
Exp/Cntr=0.3,0.1

Type RM Length L Ch R = 1 ,2832.038,188.16,195.3,194.22
XS GIS Cut Line= 4
1573360.32055542741202.9546149521573674.15819341741208.365608692
1573843.70266454741215.5802670271574235.09787977741309.370825514
#Sta/Elev= 30
       0  340.22      14   336.9      21  334.31   42.01  324.12   63.01  315.57
   77.01  311.54   98.01  308.29  112.02  307.07  133.02  307.27  147.02  306.48
  189.03  302.68  203.03  301.93  231.03  301.15  320.89  300.12  341.91  300.91
  355.75  299.61  362.93  298.29  369.93  297.71  387.03     299  411.97  300.24
  425.99  300.39  490.78  305.25  541.17  306.32  562.76  307.98  605.95  313.14
  692.33  326.95  713.92  329.42  742.72  331.77   807.5  335.61  886.06  337.65
#Mann= 3 , 0 , 0
       0      .1       0  355.75    .035       0  387.03      .1       0
Bank Sta=355.75,387.03
XS Rating Curve= 0 ,0
Exp/Cntr=0.3,0.1

Type RM Length L Ch R = 1 ,2636.736,246.44,285.1,282.27
XS GIS Cut Line= 4
1573340.48024493741363.4807631081573616.44092667741394.143061072
1573802.21837904741399.5540548411574177.38061297741468.093309119
#Sta/Elev= 30
       0  340.93   21.13  340.26   56.34  338.11  105.65  330.92  112.69  329.18
  119.73  326.14  133.82  317.17  140.86  313.36  161.99  306.11  169.03  304.22
  176.08  303.17  225.38  297.42  260.59  297.36  319.68  298.61  333.14  297.93
  347.69  296.86  363.81  298.09   382.7  298.59  396.71  300.45  410.72  301.34
  445.73  302.82  491.98  303.98  513.33   305.3  548.91   308.7  577.37  312.41
  627.18  321.72  684.11  329.29  719.69  332.18   769.5  335.24  844.89  338.61
#Mann= 3 , 0 , 0
       0      .1       0  333.14    .035       0  363.81      .1       0
Bank Sta=333.14,363.81
XS Rating Curve= 0 ,0
Exp/Cntr=0.3,0.1

Type RM Length L Ch R = 1 ,2351.638,317.05,349.13,293.5
XS GIS Cut Line= 4
1573158.31012174741529.4179050481573574.95664117741635.834115624
1573710.23148514741686.336724043 1574162.9512963741763.894301251
#Sta/Elev= 30
       0  341.88   14.45  339.38    28.9  338.66    57.8  334.31   79.47  332.25
  101.15  328.07   115.6  326.34  216.74  326.51  260.09  322.11  274.54  318.98
  303.44  307.96  317.89  303.81  375.68  294.63  411.81  295.64  437.49  294.93
  452.44   295.6  459.91  295.51  469.31  294.23  474.85  293.14  482.32  293.06
   499.6  295.11  534.63  296.18  574.42  299.48  652.54   301.9  688.05  304.33
  751.97  310.47  943.72  322.91  986.33  326.57 1014.74     328 1033.73  330.04
#Mann= 3 , 0 , 0
       0      .1       0  469.31    .035       0   499.6      .1       0
Bank Sta=469.31,499.6
XS Rating Curve= 0 ,0
Exp/Cntr=0.3,0.1