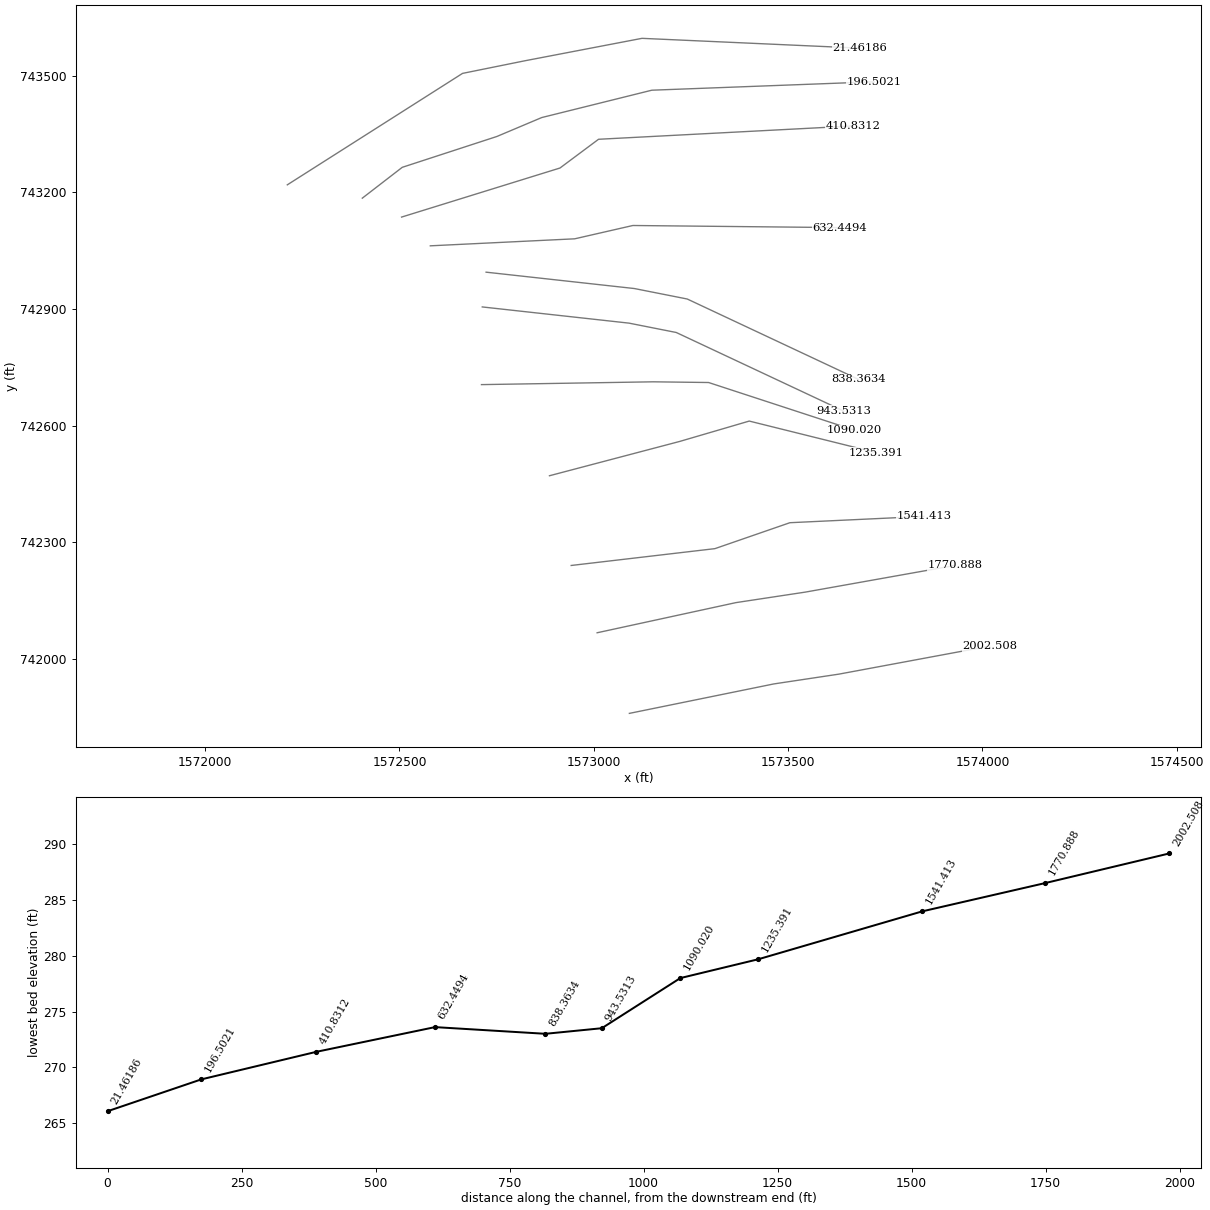
HEC-RAS study StoneRunTrib2.prj: Stone Run Trib 2

--- StoneRunTrib2.g01 (geometry) --- (continued)

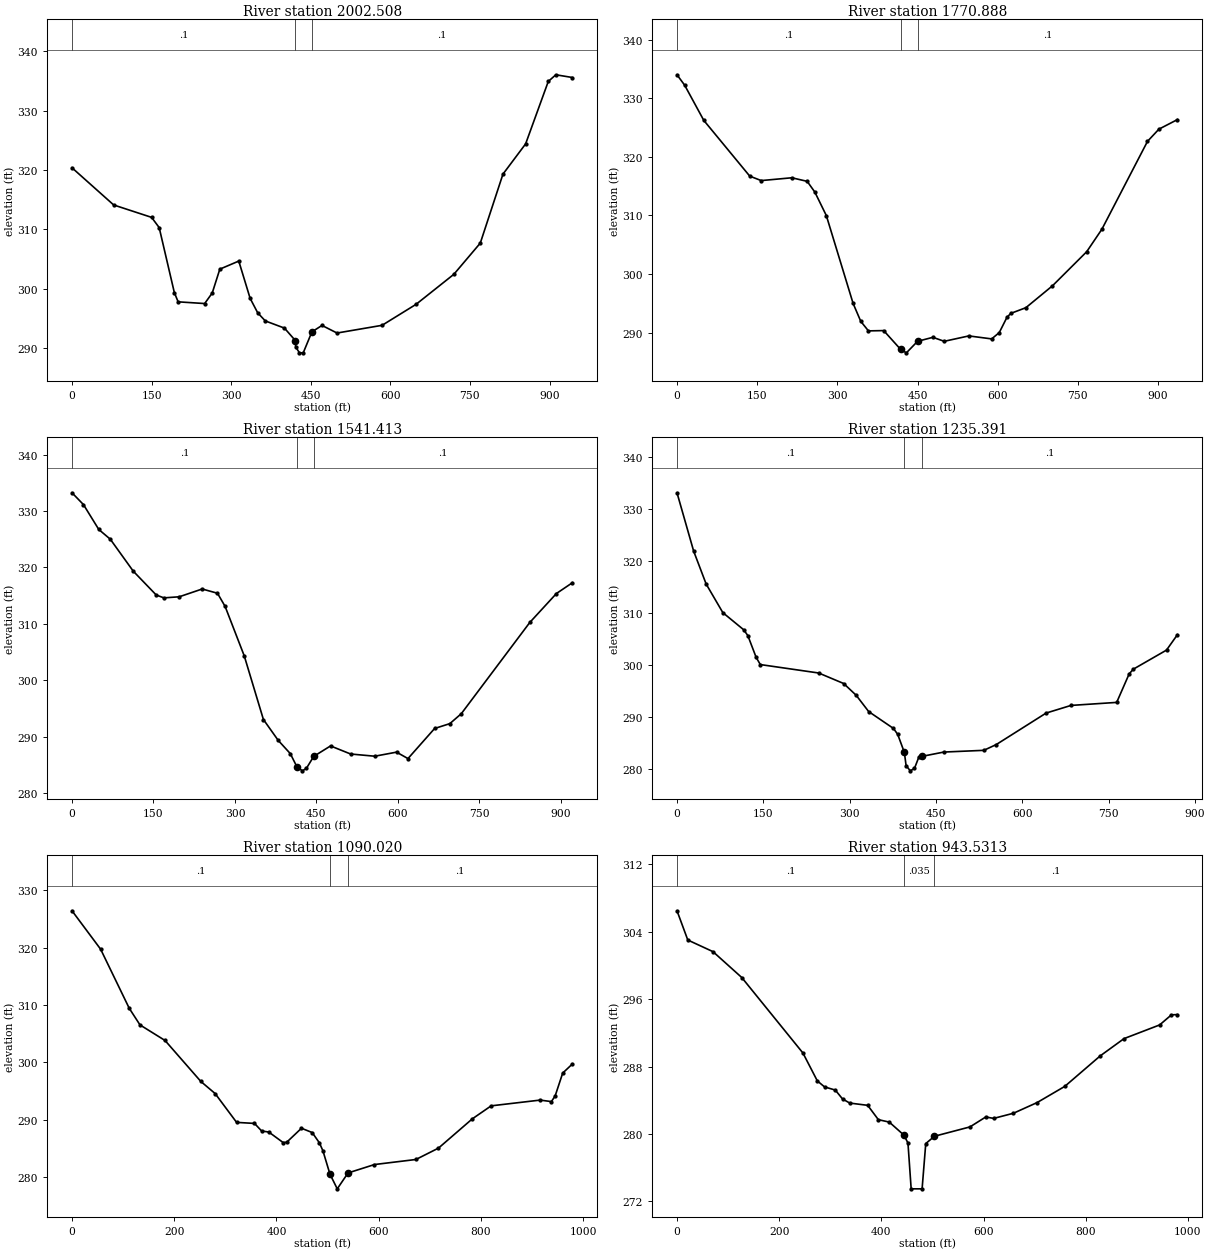
Type RM Length L Ch R = 1 ,2002.508,230.43,231.62,222.49
XS GIS Cut Line= 4
1573091.57453205741859.4885243481573463.12943679741935.242436945
1573630.87024333741960.4937411841574018.65812938742032.640324622
#Sta/Elev= 30
       0  320.39   78.58  314.12  150.02  312.03  164.31  310.31  192.89  299.35
  200.03  297.79  250.04   297.5  264.33  299.28  278.62   303.3  314.34  304.66
  335.77  298.37  350.06  295.93  364.34  294.57  400.44  293.36  420.98  291.26
  421.67  290.18  428.75  289.19  435.83  289.19   452.2  292.73  471.22  293.81
  499.54  292.53  584.43  293.83  648.51  297.37  719.71  302.43  769.55  307.69
  812.27  319.32  854.99  324.42  897.72  334.95  911.96  336.07  943.27  335.61
#Mann= 3 , 0 , 0
       0      .1       0  420.98    .035       0   452.2      .1       0
Bank Sta=420.98,452.2
XS Rating Curve= 0 ,0
Exp/Cntr=0.3,0.1

Type RM Length L Ch R = 1 ,1770.888,152.94,229.48,184.58
XS GIS Cut Line= 4
 1573008.6059611742066.9099517461573365.73154919742144.467528969
 1573544.2943432742171.5224977581573928.47490008742240.061752036
#Sta/Elev= 30
       0  334.02   14.33  332.24   50.14  326.23   136.1  316.71  157.59  315.95
   214.9  316.43  243.55  315.82  257.87  313.99  279.36  309.98  329.51  294.96
  343.83  291.91  358.16  290.28  386.69  290.33  418.15  287.14  429.17  286.53
  450.08   288.5  478.73  289.18  499.97   288.5  546.05  289.42  588.71  288.91
  602.94  289.99  617.16  292.57  624.27  293.26  652.71  294.24  702.48  297.98
  766.48   303.8  794.92  307.64  880.25  322.65  901.58  324.73   936.3  326.37
#Mann= 3 , 0 , 0
       0      .1       0  418.15    .035       0  450.08      .1       0
Bank Sta=418.15,450.08
XS Rating Curve= 0 ,0
Exp/Cntr=0.3,0.1

Type RM Length L Ch R = 1 ,1541.413,293.93,306.02,287.5
XS GIS Cut Line= 4
 1572941.8703714742240.0617520361573311.62161157742283.349702105
1573504.61372229742350.0852918031573849.11365825742366.318273082
#Sta/Elev= 30
       0  333.23   21.14  331.13   49.33  326.73   70.48  325.01  112.76  319.35
  155.05  315.13  169.15  314.62  197.34  314.81  239.63  316.19  267.82  315.44
  281.91   313.1  317.15  304.34  352.39  293.08  379.68  289.38   401.9  287.04
  413.88  284.74  424.12  283.99  431.53  284.43  445.02  286.55  475.97   288.4
     513  286.97  557.44  286.58   597.5   287.3  618.53  286.16  667.58  291.49
  695.61  292.35  716.64   294.1  842.78  310.26  891.83  315.39  921.36  317.31
#Mann= 3 , 0 , 0
       0      .1       0  413.88    .035       0  445.02      .1       0
Bank Sta=413.88,445.02
XS Rating Curve= 0 ,0
Exp/Cntr=0.3,0.1

Type RM Length L Ch R = 1 ,1235.391,149.93,145.37,118.84
XS GIS Cut Line= 4
1572885.95676924742470.9308190641573221.43838227742559.310383812
1573400.00117633742611.6166567951573726.46446639742530.451750413
#Sta/Elev= 30
       0  333.12   28.96   321.9   50.67  315.58   79.63  310.09  115.82   306.8
  123.06  305.68  137.54  301.48  144.78  300.11  246.12  298.49  289.55  296.47
  311.27  294.21  332.99  291.08   376.1  287.83   383.4   286.7  394.97  283.23
  397.99  280.69  405.28  279.69  412.58  280.17  419.87  282.26  424.96  282.46
  463.63   283.3  532.99  283.63  554.63  284.74  641.19  290.79  684.47  292.26
  763.81  292.84  785.45  298.31  792.66  299.22  850.37  302.89  869.39  305.86
#Mann= 3 , 0 , 0
       0      .1       0  394.97    .035       0  424.96      .1       0
Bank Sta=394.97,424.96
XS Rating Curve= 0 ,0
Exp/Cntr=0.3,0.1

Type RM Length L Ch R = 1 ,1090.020,172.19,146.49,144.69
XS GIS Cut Line= 4
1572711.00130436742705.4072152971573152.89912798742712.621873632
1573295.38863032742710.8182090371573670.55086423742588.169017181
#Sta/Elev= 30
       0  326.41   56.01  319.72  112.01  309.43  133.02  306.54  182.02  303.83
  252.03   296.7  280.04  294.59  322.04  289.57  357.05  289.39  371.05  288.07
  385.05  287.89  413.06  286.06  420.06  286.11  448.96  288.55  469.96   287.8
  483.96  286.02  490.96  284.62  504.66  280.57  518.96     278   540.1280.7672
  591.82  282.23  672.83  283.11  717.02  285.09   783.3  290.19  820.12  292.45
  915.86  293.45  937.96  293.19  945.32  294.18  960.05  298.15  979.16  299.75
#Mann= 3 , 0 , 0
       0      .1       0  504.66    .035       0   540.1      .1       0
Bank Sta=504.66,540.1
XS Rating Curve= 0 ,0
Exp/Cntr=0.5,0.3

Type RM Length L Ch R = 1 ,943.5313,106.06,105.17,124.32
BEGIN DESCRIPTION:
Ground elevation lowered to accomodate culvert opening.
END DESCRIPTION:
XS GIS Cut Line= 4
1572713.05796067742905.2800193881573090.60255641742863.611217827
1573212.23113927742839.5263499171573642.85867408742637.395058095
#Sta/Elev= 30
       0   306.5   21.13  303.03   70.43  301.65  126.77  298.58  246.49  289.62
  274.66  286.31  288.74   285.6  309.87  285.22  323.96  284.17  338.04  283.68
  373.25  283.41  394.11  281.71  415.52  281.42  444.06  279.88  452.06  278.94
  458.33   273.5  479.74   273.5  486.88  278.87  503.83  279.74  573.42  280.85
  604.35  282.03  619.82  281.86  658.48  282.47  704.88  283.74  759.01  285.66
   828.6  289.29     875  291.33   944.6  292.95  967.79  294.15  979.53  294.18
#Mann= 3 , 0 , 0
       0      .1       0  444.06    .035       0  503.83      .1       0
Bank Sta=444.06,503.83
XS Rating Curve= 0 ,0
Exp/Cntr=0.5,0.3

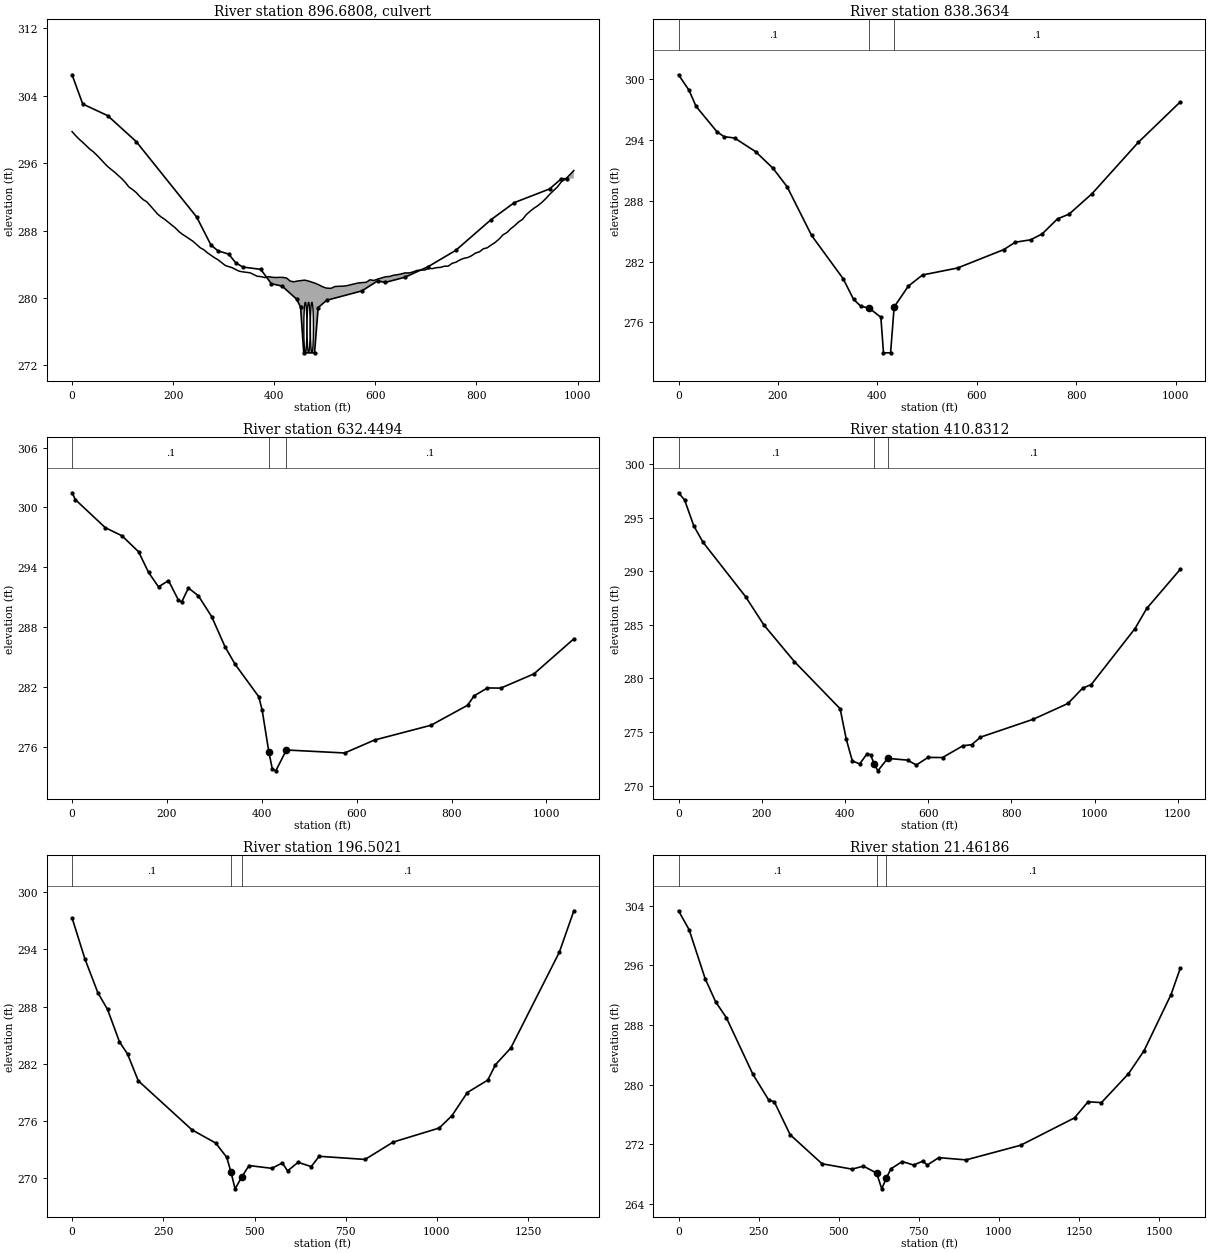
Type RM Length L Ch R = 2 ,896.6808,,,
BEGIN DESCRIPTION:
West Pearl Street.  MDE Bridge #: CE042407FS-6
Bridge Deck taken from DEM
Structure information taken from survey data.
END DESCRIPTION:
Bridge Culvert--1,0,-1,-1, 0
Deck Dist Width WeirC Skew NumUp NumDn MinLoCord MaxHiCord MaxSubmerge Is_Ogee
30,30,2.6,0, 135, 135, , , 0.98, 0, 0,0,,
       0    7.04   14.09   21.13   28.17   35.21   42.26    49.3   56.34   63.38
   70.43   77.47   84.51   91.55    98.6  105.64  112.68  119.72  126.77  133.81
  140.85  147.89  154.94  161.98  169.02  176.06  183.11  190.15  197.19  204.23
  211.28  218.32  225.36   232.4  239.45  246.49  253.53  260.57  267.62  274.66
   281.7  288.74  295.79  302.83  309.87  316.91  323.96     331  338.04  345.08
  352.13  359.17  366.21  373.25  381.55  388.69  395.82  402.96  410.09  417.23
  424.37   431.5  438.64  445.77  452.91  460.04  467.18  474.32  481.45  488.59
  495.72  502.86  512.14  519.88  527.61  535.34  543.08  550.81  558.54  566.27
  574.01  581.74  589.47   597.2  604.94  612.67   620.4  628.14  635.87   643.6
  651.33  659.07   666.8  674.53  682.27     690  697.73  705.46   713.2  720.93
  728.66  736.39  744.13  751.86  759.59  767.33  775.06  782.79  790.52  798.26
  805.99  813.72  821.46  829.19  836.92  844.65  852.39  860.12  867.85  875.58
  883.32  891.05  898.78  906.52  914.25  921.98  929.71  937.45  945.18  952.91
  960.65  968.38  976.11  983.84  992.74
  299.75  299.28  298.85  298.48  298.08  297.67  297.35  296.94   296.5  296.04
  295.61  295.27  294.92  294.54  294.16   293.7  293.17  292.88  292.53  292.07
  291.68  291.42  290.95  290.46  289.98  289.63  289.35  289.01  288.67  288.33
   287.9  287.57   287.3  287.01  286.73  286.35  285.97  285.74  285.38  285.08
  284.79  284.55  284.22  283.88  283.73   283.6  283.38  283.18  283.11  283.06
     283  282.79  282.59  282.55  282.43  282.54  282.47  282.44  282.46  282.45
  282.38  282.02  281.93  282.02  282.08  282.13  282.03  281.89  281.75  281.56
  281.34  281.19  281.15  281.37   281.4  281.41  281.46  281.58  281.69  281.79
  281.84  281.87  282.17  282.09  282.26   282.4  282.53  282.56  282.71  282.77
  282.87  282.99  282.98   283.1  283.28  283.32  283.33  283.52   283.5  283.61
  283.64  283.78  283.79  284.12  284.26  284.53  284.72  284.81  285.03  285.34
  285.49  285.85  285.97   286.3   286.6  286.99   287.5  287.77  288.23  288.59
  289.03  289.33  289.91  290.32  290.68  290.99  291.37  291.82  292.33  292.77
  293.22  293.83  294.11  294.58  295.14
                                                                                
                                                                                
                                                                                
                                                                                
                                                                                
                                                                                
                                                                                
                                                                                
                                                                                
                                                                                
                                                                                
                                                                                
                                                                                
                                        
       0    7.04   14.09   21.13   28.17   35.21   42.26    49.3   56.34   63.38
   70.43   77.47   84.51   91.55    98.6  105.64  112.68  119.72  126.77  133.81
  140.85  147.89  154.94  161.98  169.02  176.06  183.11  190.15  197.19  204.23
  211.28  218.32  225.36   232.4  239.45  246.49  253.53  260.57  267.62  274.66
   281.7  288.74  295.79  302.83  309.87  316.91  323.96     331  338.04  345.08
  352.13  359.17  366.21  373.25  381.55  388.69  395.82  402.96  410.09  417.23
  424.37   431.5  438.64  445.77  452.91  460.04  467.18  474.32  481.45  488.59
  495.72  502.86  512.14  519.88  527.61  535.34  543.08  550.81  558.54  566.27
  574.01  581.74  589.47   597.2  604.94  612.67   620.4  628.14  635.87   643.6
  651.33  659.07   666.8  674.53  682.27     690  697.73  705.46   713.2  720.93
  728.66  736.39  744.13  751.86  759.59  767.33  775.06  782.79  790.52  798.26
  805.99  813.72  821.46  829.19  836.92  844.65  852.39  860.12  867.85  875.58
  883.32  891.05  898.78  906.52  914.25  921.98  929.71  937.45  945.18  952.91
  960.65  968.38  976.11  983.84  992.74
  299.75  299.28  298.85  298.48  298.08  297.67  297.35  296.94   296.5  296.04
  295.61  295.27  294.92  294.54  294.16   293.7  293.17  292.88  292.53  292.07
  291.68  291.42  290.95  290.46  289.98  289.63  289.35  289.01  288.67  288.33
   287.9  287.57   287.3  287.01  286.73  286.35  285.97  285.74  285.38  285.08
  284.79  284.55  284.22  283.88  283.73   283.6  283.38  283.18  283.11  283.06
     283  282.79  282.59  282.55  282.43  282.54  282.47  282.44  282.46  282.45
  282.38  282.02  281.93  282.02  282.08  282.13  282.03  281.89  281.75  281.56
  281.34  281.19  281.15  281.37   281.4  281.41  281.46  281.58  281.69  281.79
  281.84  281.87  282.17  282.09  282.26   282.4  282.53  282.56  282.71  282.77
  282.87  282.99  282.98   283.1  283.28  283.32  283.33  283.52   283.5  283.61
  283.64  283.78  283.79  284.12  284.26  284.53  284.72  284.81  285.03  285.34
  285.49  285.85  285.97   286.3   286.6  286.99   287.5  287.77  288.23  288.59
  289.03  289.33  289.91  290.32  290.68  290.99  291.37  291.82  292.33  292.77
  293.22  293.83  294.11  294.58  295.14
                                                                                
                                                                                
                                                                                
                                                                                
                                                                                
                                                                                
                                                                                
                                                                                
                                                                                
                                                                                
                                                                                
                                                                                
                                                                                
                                        
BR Coef=-1 , 0 , 0 ,, 0 ,,,0.8,0,,0,
WSPro=,,,, 1 ,,,, 0 ,,,, 0 ,,,,-1 ,-1 ,-1 , 0 , 0 , 0 , 0 , 0
Multiple Barrel Culv=1,6,,30,0.014,0.2,1,1,3,273.5,273, 3,Culvert #1  , 0 ,30
   461.5   412.9     468   419.4   474.5   425.9
Culvert Bottom n=0.014
BC Design=,, 0 ,, 0 ,,,,,,
BC Use User HTab Curves=0
BC User HTab FreeFlow(D)= 0

Type RM Length L Ch R = 1 ,838.3634,170.5,205.91,178.09
BEGIN DESCRIPTION:
Ground elevation lowered to accomodate culvert opening.
END DESCRIPTION:
XS GIS Cut Line= 4
1572722.93112019 742994.736828641573104.30536382742952.645356923
1573240.50978173742925.6741850231573681.10031641742718.866383061
#Sta/Elev= 30
       0  300.43   21.13   298.9   35.21  297.32   77.47   294.8   91.55  294.33
  112.68  294.19  154.94  292.85  190.15   291.2  218.32  289.39  267.62  284.58
     331  280.32  352.13  278.27  366.21  277.62  383.69   277.4  406.93  276.51
  412.23     273  426.51     273  433.64  277.52  462.19  279.58  490.73  280.68
   561.2  281.37     654  283.18   677.2  283.91  708.13  284.15  731.32  284.73
  762.26  286.22  785.45  286.68  831.85  288.71  924.64  293.76 1009.25  297.76
#Mann= 3 , 0 , 0
       0      .1       0  383.69    .035       0  433.64      .1       0
Bank Sta=383.69,433.64
XS Rating Curve= 0 ,0
Exp/Cntr=0.5,0.3

Type RM Length L Ch R = 1 ,632.4494,196.2,221.62,237.79
XS GIS Cut Line= 4
1572579.33378956743062.5328033861572950.88869436743080.569449246
1573100.59285499 743114.839076371573632.67390792743109.428082615
#Sta/Elev= 30
       0  301.47    7.01  300.78   70.08  297.97  105.12  297.16  140.16  295.56
  161.19  293.49  182.21  292.04  203.24  292.67  224.26   290.7  231.27  290.54
  245.29  291.93  266.31  291.14  294.35  289.05  322.38  286.04   343.4   284.3
  393.54  281.03  400.72  279.67  414.82  275.48  422.26  273.74  429.44   273.6
  451.73  275.69  574.57  275.39  637.57  276.69  756.58  278.17  833.58  280.17
  847.59  281.12  875.59  281.91  903.59  281.89  973.59  283.32 1057.68  286.83
#Mann= 3 , 0 , 0
       0      .1       0  414.82    .035       0  451.73      .1       0
Bank Sta=414.82,451.73
XS Rating Curve= 0 ,0
Exp/Cntr=0.3,0.1

Type RM Length L Ch R = 1 ,410.8312,169.87,214.33,112.51
XS GIS Cut Line= 4
1572505.38354149743136.4830514041572913.01173803743262.739572436
1573012.21329029743336.6898204981573666.94353506743370.959447637
#Sta/Elev= 30
       0  297.31   14.66  296.63   36.64  294.23   58.62  292.71  161.22  287.62
  205.19  284.98  278.47  281.57  388.39  277.17  403.04  274.35   417.7   272.3
  435.46  272.03  452.93  272.96  461.66  272.88  469.89  272.05  479.12  271.38
  502.58  272.54  550.47  272.38  571.49  271.92  599.53  272.63  634.58  272.62
  683.65  273.72  704.68  273.82  725.71  274.52  851.88  276.18  935.99  277.66
  971.04  279.08  992.07  279.43 1097.21  284.65 1125.25  286.52 1206.09  290.18
#Mann= 3 , 0 , 0
       0      .1       0  469.89    .035       0  502.58      .1       0
Bank Sta=469.89,502.58
XS Rating Curve= 0 ,0
Exp/Cntr=0.3,0.1

Type RM Length L Ch R = 1 ,196.5021,184.15,175.04,153.14
XS GIS Cut Line= 6
1572404.37832466743185.1819952431572507.18720609743264.543237031
1572750.68192527743343.9044788181572866.11645876743392.603422657
 1573149.2917988743462.9463415291573721.05347262743484.590316549
#Sta/Elev= 30
       0  297.29   35.37  292.98   70.74  289.45   97.27   287.7  129.88  284.31
  151.96  283.04  181.41  280.23  328.66  275.09  393.58  273.71  423.97  272.21
  435.12  270.71  446.76  268.91  465.51  270.17  484.74  271.35  547.33  271.06
  576.18  271.62   590.6  270.79  619.46  271.69  655.52  271.24  677.16  272.32
  803.05  271.99   880.1  273.81 1006.19  275.28 1041.22  276.58 1083.25     279
 1139.29   280.3  1160.3  281.91 1202.33  283.66 1335.43   293.7 1375.22  298.04
#Mann= 3 , 0 , 0
       0      .1       0  435.12    .035       0  465.51      .1       0
Bank Sta=435.12,465.51
XS Rating Curve= 0 ,0
Exp/Cntr=0.3,0.1

Type RM Length L Ch R = 1 ,21.46186,18.66,21.46,31.22
XS GIS Cut Line= 5
1572211.38621393743219.451622382 1572662.3023605743506.234291613
1572822.82850873743538.7002541421573124.04049461743596.417520896
1573684.98018095743571.166216701
#Sta/Elev= 30
       0  303.31   33.18  300.76   82.96  294.23  116.14  291.09  149.32  288.98
  232.28  281.39  282.06  277.91  298.65  277.74  348.42   273.3  447.97  269.41
  541.53  268.69  577.24  269.09  618.24  268.16  634.37  266.05  648.32  267.46
  662.94  268.73  698.16  269.71   733.8  269.24  762.31  269.76  776.56  269.24
   812.2  270.23  897.73  269.93 1067.92  271.89 1236.09  275.56 1278.13  277.71
 1320.18  277.61 1404.26  281.46 1453.31  284.57 1537.39  292.09 1566.36  295.63
#Mann= 3 , 0 , 0
       0      .1       0  618.24    .035       0  648.32      .1       0
Bank Sta=618.24,648.32
XS Rating Curve= 0 ,0
Exp/Cntr=0.3,0.1

Chan Stop Cuts=-1
Use User Specified Reach Order=0