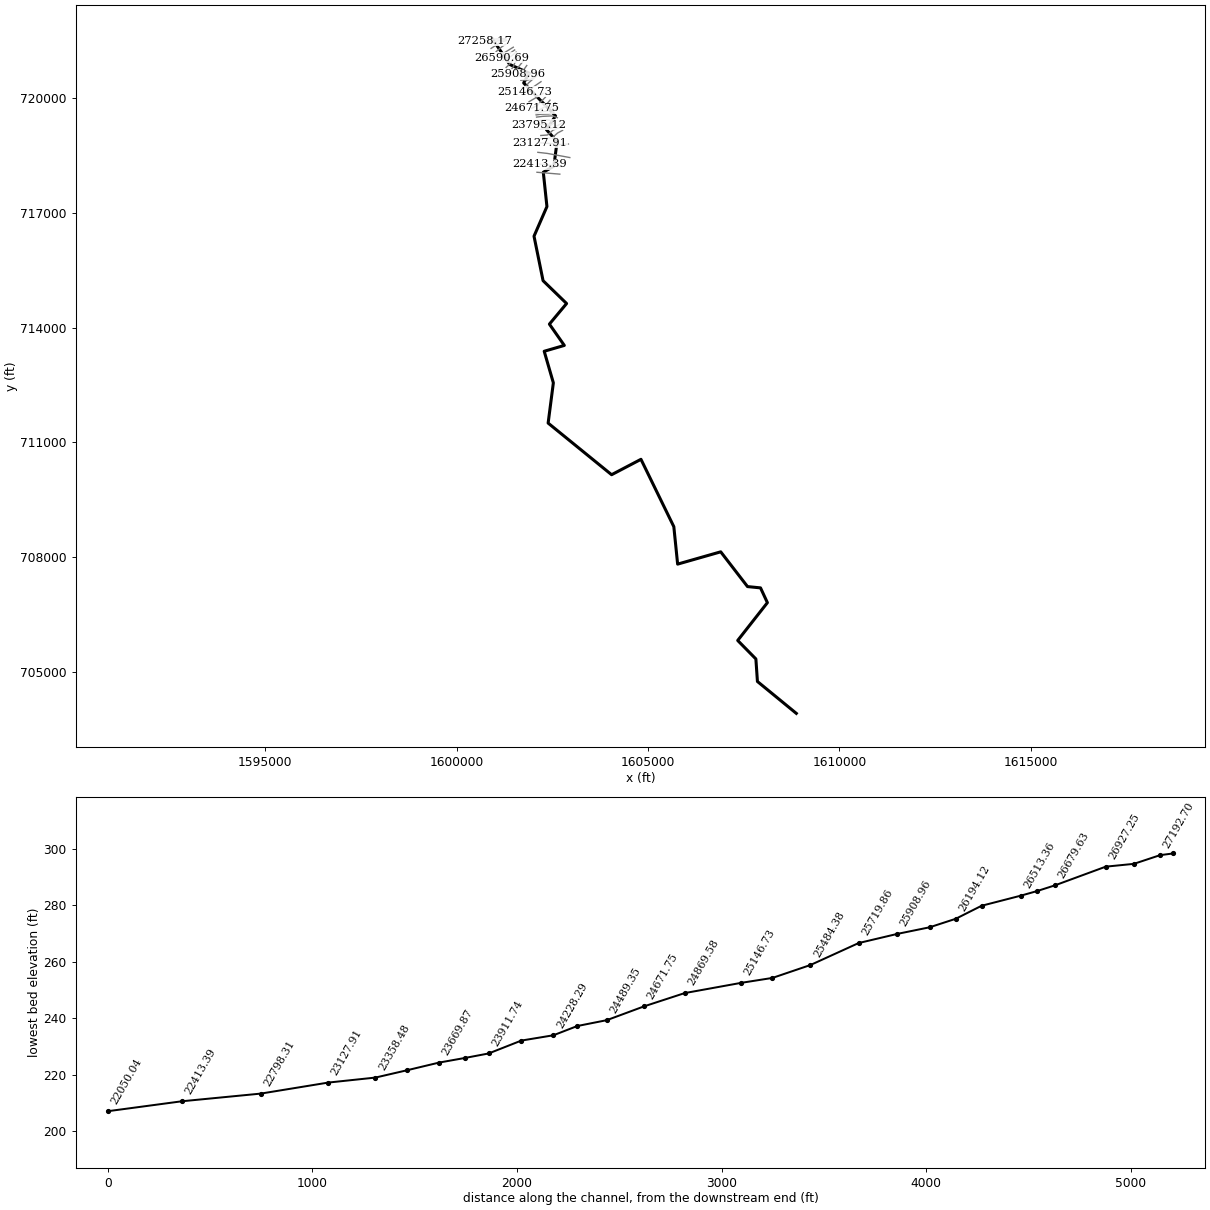
--- StonyRun.prj (project) ---

Proj Title=StonyRun
Current Plan=p01
Default Exp/Contr=0.3,0.1
English Units
Geom File=g01
Flow File=f01
Plan File=p01
Y Axis Title=Elevation
X Axis Title(PF)=Main Channel Distance
X Axis Title(XS)=Station
BEGIN DESCRIPTION:
Stony Run - Georeferenced HEC-RAS model.  This was formerly an approximate method stream.  Projection:  MD Stateplane.  Horizontal datum:  NAD83.  Vertrial datum: NAVD88.  Units:Feet.  Created by: Aaron W. Buesing, USACE- St Paul District as part of FEMA Map Modernization study for Cecil County, MD.
END DESCRIPTION:
DSS Export Rating Curves= 0
DSS Export Rating Curve Sorted= 0
DSS Export Volume Flow Curves= 0
DXF OffsetX= 0
DXF OffsetY= 0
DXF ScaleX= 1
DXF ScaleY= 10

--- StonyRun.p01 (plan) ---

Plan Title=StonyRun_100yr
Program Version=4.00
Short Identifier=StonyRun100
Geom File=g01
Flow File=f01
Subcritical Flow
K Sum by GR= 0
Std Step Tol= 0.01
Critical Tol= 0.01
Num of Std Step Trials= 20
Max Error Tol= 0.3
Flow Tol Ratio= 0.001
Split Flow NTrial= 30
Split Flow Tol= 0.02
Split Flow Ratio= 0.02
Log Output Level= 0
Friction Slope Method= 1
Unsteady Friction Slope Method= 2
Unsteady Bridges Friction Slope Method= 1
Secant Critical Depth
Global Vel Dist= 0 , 0 , 0
Global Log Level= 0
CheckData=True
Encroach Param=-1 ,0,0, 0
Computation Interval=1HOUR
Output Interval=1HOUR
Run HTab= 0
Run UNet= 0
Run PostProcess= 0
Run WQNet= 0
UNET Theta= 1
UNET Theta Warmup= 1
UNET ZTol= 0.02
UNET ZSATol= 0.05
UNET MxIter= 20
UNET MaxInSteps= 0
UNET DtIC= 0
UNET DtMin= 0
UNET MaxCRTS= 20
UNET WFStab= 2
UNET SFStab= 1
UNET WFX= 1
UNET SFX= 1
UNET DSS MLevel= 4
UNET DZMax Abort= 100
UNET Convert EG Bridges= 0
UNET Use Existing IB Tables=-1
UNET Froude Reduction=False
UNET Froude Limit= 1
UNET Froude Power= 10
UNET Time Slicing=0,0, 5
Instantaneous Interval=1HOUR
Write IC File= 0
Echo Input=False
Echo Output=False
Write Detailed= 0
Detailed Automatic Start=False, 10
WQ ULTIMATE=-1
WQ Max Comp Step=1HOUR
WQ Output Interval=15MIN
WQ Output Selected Increments= 0
WQ Output face flow=0
WQ Output face velocity=0
WQ Output face area=0
WQ Output face dispersion=0
WQ Output cell volume=0
WQ Output cell surface area=0
WQ Output cell continuity=0
WQ Output face conc=0
WQ Output face dconc_dx=0
WQ Output face courant=0
WQ Output face peclet=0
WQ Output face adv mass=0
WQ Output face disp mass=0
WQ Output cell mass=0
WQ Output cell source sink temp=0
WQ Output cell source sink nsm=0
WQ Output MaxMinRange=-1
WQ Create Restart=0
WQ Fixed Restart=0
Sorting and Armoring Iterations= 10
XS Update Threshold= 0.02
Hydraulics Update Threshold= 0.02
Energy Slope Method= 1
Volume Change Method= 0
XS Weighting Method= 0
Number of US Weighted Cross Sections= 1
Number of DS Weighted Cross Sections= 1
Upstream XS Weight=0.25
Main XS Weight=0.5
Downstream XS Weight=0.25
Number of DS XS's Weighted with US Boundary= 1
Upstream Boundary Weight= 1
Weight of XSs Associated with US Boundary= 0
Number of US XS's Weighted with DS Boundary= 1
Downstream Boundary Weight= 0.5
Weight of XSs Associated with DS Boundary= 0.5
Sediment Output Level= 4
Mass or Volume Output= 0
Output Increment Type= 1
Profile and TS Output Increment= 10
XS Output Flag= 0
XS Output Increment= 10
Disregard all LS=0
Disregard all Conn=0
Disregard all Breaches=0
Disregard all Pumps=0

--- StonyRun.f01 (steady flow) ---

Flow Title=StonyRun_100yr
Program Version=4.00
Number of Profiles= 2
Profile Names=100CUR,100ULT
River Rch & RM=StonyRun,Reach1          ,27258.17
    1760    1950
River Rch & RM=StonyRun,Reach1          ,24071.52
    1900    2230
River Rch & RM=StonyRun,Reach1          ,23911.74
    1980    2290
River Rch & RM=StonyRun,Reach1          ,21192.53
    2040    2500
River Rch & RM=StonyRun,Reach1          ,20926.71
    2060    2690
River Rch & RM=StonyRun,Reach1          ,19182.20
    2120    2840
River Rch & RM=StonyRun,Reach1          ,18604.05
    3600    4950
River Rch & RM=StonyRun,Reach1          ,6165.706
    4640    6390
Boundary for River Rch & Prof#=StonyRun,Reach1          , 1
Up Type= 0
Dn Type= 3
Dn Slope=0.0006
Boundary for River Rch & Prof#=StonyRun,Reach1          , 2
Up Type= 0
Dn Type= 3
Dn Slope=0.0006
DSS Import GetInterval= 0
DSS Import GetPeak= 0
DSS Import FillOption= 0

--- StonyRun.g01 (geometry) ---

Geom Title=StonyRun
Program Version=4.00

River Reach=StonyRun        ,Reach1
Reach XY= 30
1600923.53643607721558.1458056721601384.20174091720876.424313694
 1601893.4204582720648.2627490161601750.52342249720391.679674581
1602583.82630008 719531.534259931602345.40141217719170.738982812
1602623.56378137  718860.47083431602539.35190044718219.407891184
1602263.55799046718058.3526689261602358.29635648717161.496137723
1602020.63766608716387.0686860981602257.24209951715224.622877538
 1602872.1958037714627.8633093241602422.74135327714089.657889232
1602812.75708103713532.7252002211602286.90145873713380.082061917
 1602526.1484458712554.8360784051602389.73256266711503.161815017
 1604048.1180263710153.9122511151604815.72394805710556.570410296
1605674.40518165 708796.034026311605773.94504516 707817.42524597
1606900.06470788 708138.831070841607600.16097617707230.380090222
1607940.19179621707196.5808763211608119.92881645706810.224764913
1607343.60884911705822.2941163031607818.86006258705339.109495312
1607859.29246537704750.3016861981608875.53466025703916.884262189

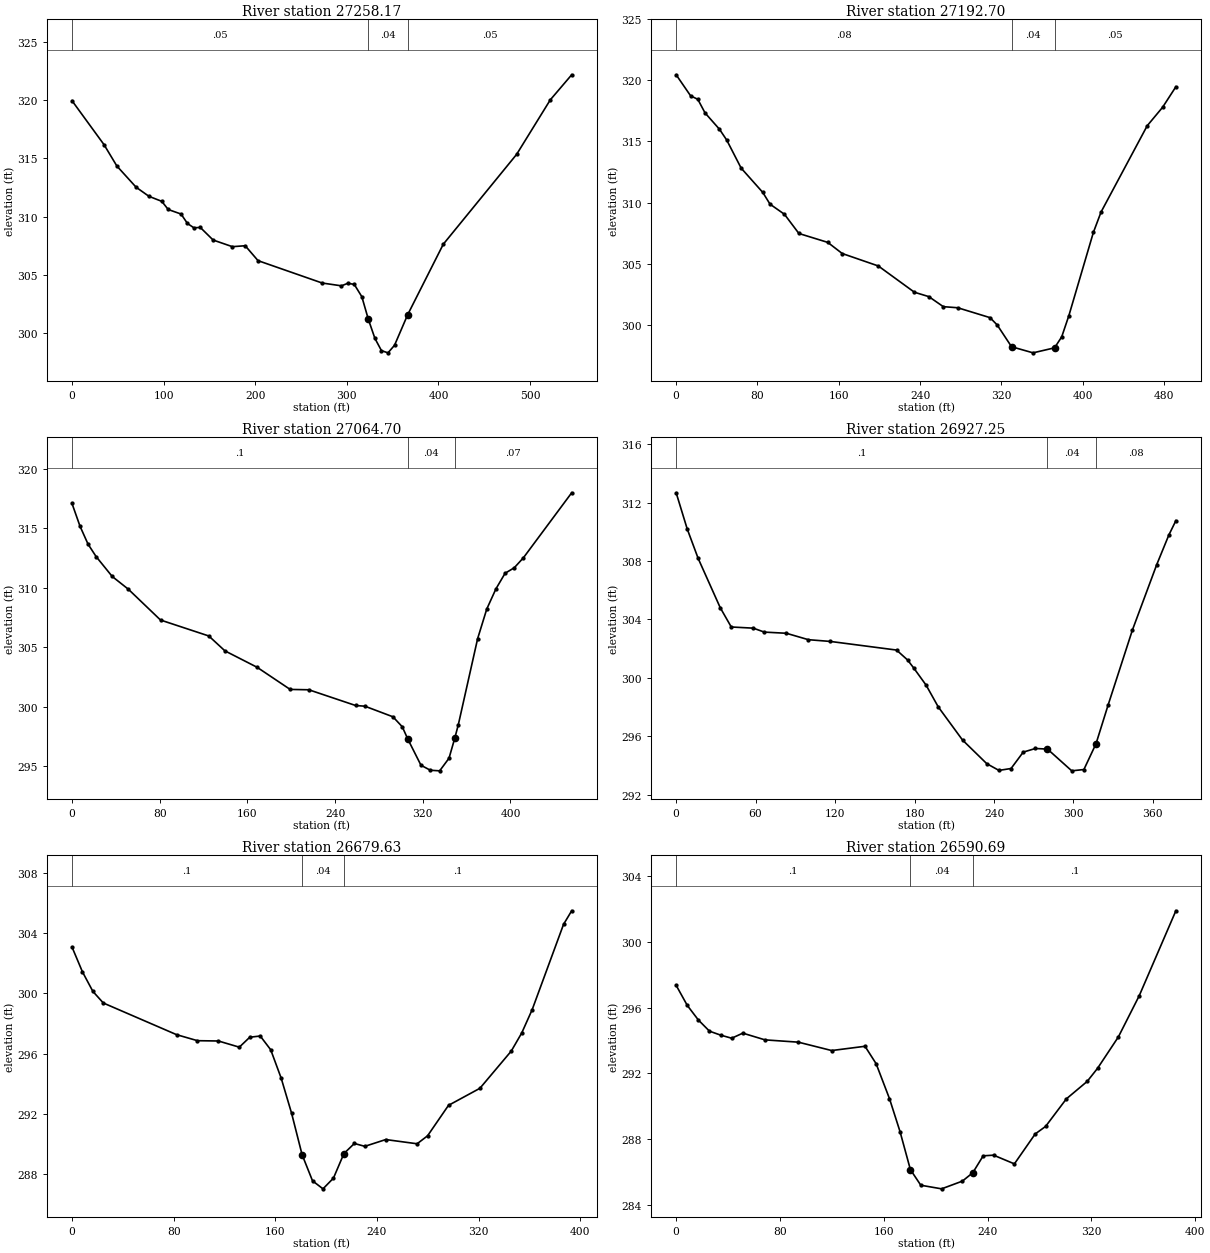
Type RM Length L Ch R = 1 ,27258.17,75.52,65.47,62.03
XS GIS Cut Line= 5
1601273.16499098721548.4317886681600956.93801801721538.776003256
1600890.55449311 721525.499298261600804.85939741721513.429566473
1600733.64797984721490.497076079
#Sta/Elev= 30
       0  319.96   35.02  316.18   49.02  314.35   70.03  312.53   84.04  311.75
   98.05  311.32  105.05  310.62  119.06  310.23  126.06  309.42  133.06  309.05
  140.07  309.08  154.07     308  175.08  307.43  189.09  307.51  203.09  306.23
  273.13  304.31  294.14  304.07  301.14  304.29  308.14  304.19  316.37  303.14
  323.51  301.19  330.65  299.56  337.79  298.51  344.93  298.32  352.07  298.97
  366.34  301.58  405.28  307.64  485.32  315.35  522.09  320.03  545.43  322.18
#Mann= 3 , 0 , 0
       0     .05       0  323.51     .04       0  366.34     .05       0
Bank Sta=323.51,366.34
XS Rating Curve= 0 ,0
Exp/Cntr=0.3,0.1

Type RM Length L Ch R = 1 ,27192.70,100.42,128,139.81
XS GIS Cut Line= 4
1601288.39566195721527.9864233291600997.97510611721477.220371097
1600890.55449311 721463.943666131600808.48031695721430.148417115
#Sta/Elev= 30
       0  320.46   14.21  318.74   21.32  318.45   28.42  317.34   42.64     316
   49.74  315.12   63.96  312.82   85.27  310.83   92.38  309.87  106.59  309.04
   120.8  307.47  149.23  306.74  163.44  305.83  198.97  304.81   234.5  302.66
  248.71   302.3  262.93  301.48  277.14  301.39  308.93  300.58  315.98  299.98
  330.09   298.2  351.25   297.7  372.41  298.11  379.46  299.01  386.52  300.75
  410.63  307.56   418.2  309.23  463.62  316.29  478.76   317.8  491.82  319.48
#Mann= 3 , 0 , 0
       0     .08       0  330.09     .04       0  372.41     .05       0
Bank Sta=330.09,372.41
XS Rating Curve= 0 ,0
Exp/Cntr=0.3,0.1

Type RM Length L Ch R = 1 ,27064.70,136.55,137.44,136.96
XS GIS Cut Line= 4
1601299.18429151721501.0148494541601117.57569404721443.475491837
1600970.13109018 721340.983511091600898.20689315 721294.23278302
#Sta/Elev= 30
       0  317.09    7.34  315.17   14.69  313.66   22.03  312.62   36.71  310.95
    51.4  309.88   80.77  307.29  124.83  305.95  139.52   304.7  168.89  303.32
  199.03  301.46  216.08  301.43  258.71  300.11  267.23  300.05  292.81  299.16
  301.33  298.32  306.34  297.29  318.38  295.09  326.91  294.67  335.43  294.62
  343.96  295.68  349.31   297.4  352.48  298.51  370.07  305.73  378.42  308.22
  386.77  309.91  395.12  311.22  403.47  311.68  411.82  312.52  455.86  317.98
#Mann= 3 , 0 , 0
       0      .1       0  306.34     .04       0  349.31     .07       0
Bank Sta=306.34,349.31
XS Rating Curve= 0 ,0
Exp/Cntr=0.3,0.1

Type RM Length L Ch R = 1 ,26927.25,211.93,247.62,195.33
XS GIS Cut Line= 3
1601333.34828508721436.2830721441601182.30747135721339.185406178
1601031.26665767 721211.51995647
#Sta/Elev= 30
       0  312.67    8.32   310.2   16.64  308.17   33.29   304.8   41.61  303.48
   58.25   303.4   66.57  303.13   83.22  303.05   99.86  302.61   116.5  302.49
  166.43   301.9  174.75  301.22  179.56  300.65  188.72   299.5  197.89  298.01
  216.22  295.74  234.55  294.12  243.72  293.66  252.88  293.79  262.05  294.91
  271.21  295.16  280.38  295.12  298.71  293.63  307.88  293.72  317.04  295.49
  326.21  298.15  344.54  303.28  362.87  307.75  372.03  309.78  377.33  310.76
#Mann= 3 , 0 , 0
       0      .1       0  280.38     .04       0  317.04     .08       0
Bank Sta=280.38,317.04
XS Rating Curve= 0 ,0
Exp/Cntr=0.3,0.1

Type RM Length L Ch R = 1 ,26679.63,89.65,88.94,85.67
XS GIS Cut Line= 2
1601478.99478404721326.5986716751601144.54726794 721119.81660527
#Sta/Elev= 30
       0  303.08    8.23  301.43   16.46  300.13   24.69  299.36    82.3  297.26
   98.76  296.86  115.22  296.84  131.68  296.43  139.91  297.09  148.14  297.17
  156.37  296.26   164.6  294.38  172.83  292.04  181.06   289.3  189.29  287.56
  197.52  287.03  205.75  287.74  213.98  289.37  222.21  290.04  230.44  289.85
   246.9   290.3  271.59  290.02  279.82  290.55  296.28  292.57  320.97   293.7
  345.66  296.17  353.89  297.37  362.12  298.92  386.81  304.58  393.21  305.48
#Mann= 3 , 0 , 0
       0      .1       0  181.06     .04       0  213.98      .1       0
Bank Sta=181.06,213.98
XS Rating Curve= 0 ,0
Exp/Cntr=0.3,0.1

Type RM Length L Ch R = 1 ,26590.69,82.44,77.33,63.42
XS GIS Cut Line= 3
1601514.27061559721254.4326000361601379.76939552721159.713935837
  1601187.052462721052.284496278
#Sta/Elev= 30
       0  297.36    8.56  296.14   17.12  295.25   25.68  294.57   34.25  294.33
   42.81  294.14   51.37  294.45   68.49  294.04   94.18   293.9  119.86  293.39
  145.55  293.65  154.11  292.59  164.42  290.46  172.52  288.46  180.53  286.14
  188.55  285.19  204.58  284.97   220.6  285.44  228.62  285.95  236.63  286.98
  244.65  287.02  260.68  286.49   276.7  288.31  284.72  288.77  300.75  290.45
  316.77  291.51  324.79  292.31  340.82  294.22  356.85  296.72  385.14   301.9
#Mann= 3 , 0 , 0
       0      .1       0  180.53     .04       0  228.62      .1       0
Bank Sta=180.53,228.62
XS Rating Curve= 0 ,0
Exp/Cntr=0.3,0.1

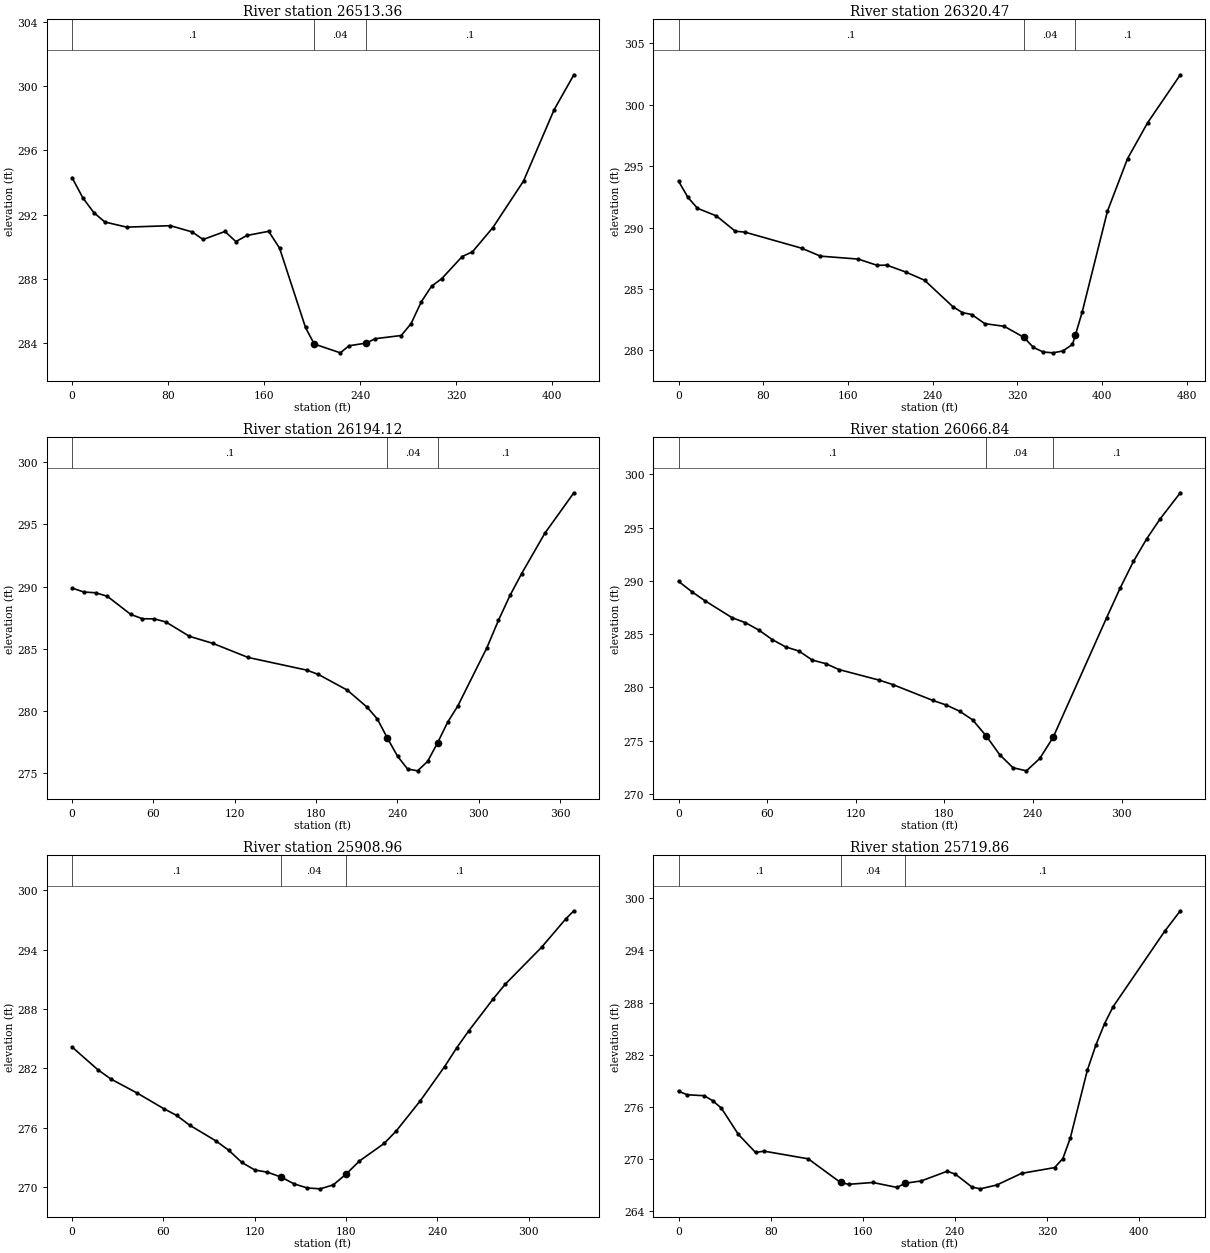
Type RM Length L Ch R = 1 ,26513.36,149.41,192.88,198.25
XS GIS Cut Line= 4
1601552.71708597721197.1351170841601414.26300673721082.056401849
1601315.36723585 721055.084827961601203.88473047 720977.76631619
#Sta/Elev= 30
       0   294.3     9.1  293.03    18.2  292.12   27.31  291.54   45.51  291.22
   81.92  291.31  100.12  290.92  109.23  290.45  127.43  290.95  136.53  290.32
  145.64   290.7  163.84  290.96  172.94  289.91  194.55  284.97   201.8  283.94
  223.57  283.39  230.82  283.83  245.34     284  252.59  284.27  274.36  284.47
  282.54  285.21  291.06  286.57  299.58  287.54   308.1  288.01  325.14  289.39
  333.66  289.68  350.69  291.19  376.25  294.09  401.81  298.54  418.21  300.71
#Mann= 3 , 0 , 0
       0      .1       0   201.8     .04       0  245.34      .1       0
Bank Sta=201.8,245.34
XS Rating Curve= 0 ,0
Exp/Cntr=0.3,0.1

Type RM Length L Ch R = 1 ,26320.47,99.13,126.35,131.37
XS GIS Cut Line= 4
1601599.46781404721157.5768087211601419.65732151 720931.01558812
 1601356.7236491720857.2932861891601291.99187179 720797.95582366
#Sta/Elev= 30
       0  293.78    8.94  292.45   17.87  291.57   35.75  290.95   53.62   289.7
   62.56  289.63  116.18  288.32  134.05  287.67   169.8  287.43  187.67  286.92
  196.61  286.94  214.48  286.38  232.35  285.71  259.16  283.55   268.1  283.07
  277.04  282.91  289.24  282.17  307.65  281.95  326.06  281.06  335.26  280.23
  344.47  279.86  353.67  279.79  362.87  279.94  372.08  280.47  374.75  281.21
  381.28  283.11  405.17  291.34  424.16  295.62  443.15  298.55  473.99  302.45
#Mann= 3 , 0 , 0
       0      .1       0  326.06     .04       0  374.75      .1       0
Bank Sta=326.06,374.75
XS Rating Curve= 0 ,0
Exp/Cntr=0.3,0.1

Type RM Length L Ch R = 1 ,26194.12,135.55,127.28,114.74
XS GIS Cut Line= 4
1601631.83370268721073.0658772141601516.75498745720914.832643807
1601486.18720372720826.7255024761601439.43647569720760.195620224
#Sta/Elev= 30
       0  289.88    8.66  289.56   17.31   289.5   25.97  289.22   43.28  287.76
   51.93  287.41   60.59   287.4   69.24  287.15   86.55     286  103.87  285.43
  129.83   284.3  173.11  283.28  181.77  282.93  203.06  281.67  217.88  280.28
  225.29  279.34   232.7   277.8  240.11  276.36  247.52  275.33  254.93  275.18
  262.34  275.94  269.75  277.45  277.16   279.1  284.57  280.39  306.02  285.07
  314.58  287.28  323.14  289.29  331.69  291.04   348.8  294.28  370.23  297.54
#Mann= 3 , 0 , 0
       0      .1       0   232.7     .04       0  269.75      .1       0
Bank Sta=232.7,269.75
XS Rating Curve= 0 ,0
Exp/Cntr=0.3,0.1

Type RM Length L Ch R = 1 ,26066.84,157.35,157.89,158.92
XS GIS Cut Line= 2
1601752.30673268720979.5644211321601536.53414163720717.041102007
#Sta/Elev= 30
       0  289.96    9.06  288.98   18.12  288.12   36.24  286.55   45.31  286.08
   54.37  285.39   63.43   284.5   72.49  283.81   81.55  283.42   90.61  282.57
   99.67  282.24  108.73  281.68  135.92  280.69  144.98  280.28  172.16  278.79
  181.22  278.36  190.28  277.78   199.1  276.97   208.4  275.45  217.46   273.7
  226.53  272.47  235.59  272.18  244.65  273.34  253.71  275.33  289.95  286.56
  299.01  289.31  308.07  291.83  317.14  293.97   326.2  295.83  339.82  298.27
#Mann= 3 , 0 , 0
       0      .1       0   208.4     .04       0  253.71      .1       0
Bank Sta=208.4,253.71
XS Rating Curve= 0 ,0
Exp/Cntr=0.3,0.1

Type RM Length L Ch R = 1 ,25908.96,212.43,189.09,107.69
XS GIS Cut Line= 3
1601831.42334938 720848.302761571601712.74842432720681.079003513
1601603.06402388720621.741540983
#Sta/Elev= 30
       0  284.16   17.17  281.84   25.75  280.91   42.92   279.5   60.09  277.95
   68.67  277.26   77.25  276.27   94.42  274.69     103  273.73  111.59   272.5
  120.17  271.74  128.41  271.52  137.34  271.03  145.92  270.34  154.51  269.93
  163.09  269.84  171.67  270.24  180.26  271.35  188.84  272.65  205.05  274.42
  213.01  275.68  228.93  278.75  244.85  282.19  252.81  284.09  260.77  285.81
  276.68  289.01  284.64   290.5  308.52  294.23  324.44   297.1  329.76  297.92
#Mann= 3 , 0 , 0
       0      .1       0  137.34     .04       0  180.26      .1       0
Bank Sta=137.34,180.26
XS Rating Curve= 0 ,0
Exp/Cntr=0.3,0.1

Type RM Length L Ch R = 1 ,25719.86,232.35,235.48,152.39
XS GIS Cut Line= 5
1602048.99404533720670.2903739511601942.90585478720632.530170545
1601822.43282478720625.337750822 1601718.1427391720601.962386817
1601628.23749284720569.596498162
#Sta/Elev= 30
       0  277.82    7.43  277.41   22.29   277.3   29.72  276.72   37.15  275.88
   52.01  272.85   66.87  270.78    74.3  270.93  112.61  270.05  140.66  267.33
  147.67  267.12  168.71  267.33  189.75  266.76  196.76  267.24  210.78  267.51
   233.3  268.62  240.47  268.28  254.82   266.8  261.99   266.6  276.34  267.04
  297.86  268.38  326.55  269.04  333.73  270.08  340.17  272.43  355.05  280.26
  362.49  283.15  369.93  285.58  377.37  287.53  422.01  296.17  435.73  298.55
#Mann= 3 , 0 , 0
       0      .1       0  140.66     .04       0  196.76      .1       0
Bank Sta=140.66,196.76
XS Rating Curve= 0 ,0
Exp/Cntr=0.3,0.1

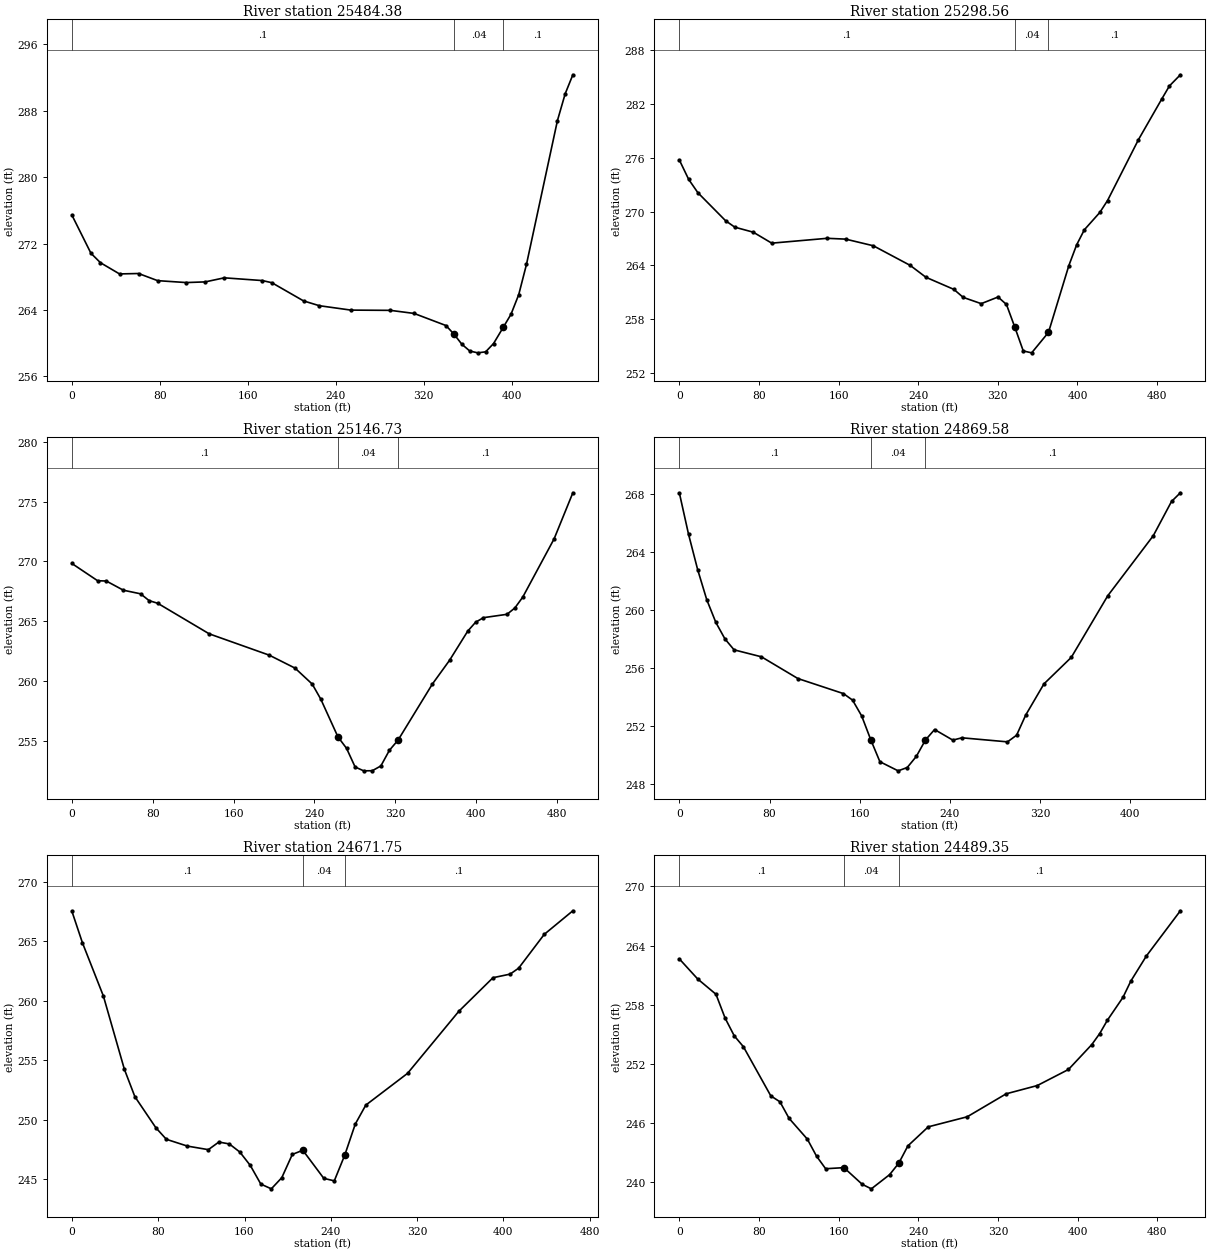
Type RM Length L Ch R = 1 ,25484.38,116.34,185.82,199.3
XS GIS Cut Line= 5
1602090.35045862 720600.16428189   1601937.51154720488.681776509
1601797.25935581720456.3158878541601739.71999818720470.700727254
1601676.78632581720463.508307546
#Sta/Elev= 30
       0  275.43   17.33  270.83   25.99  269.69   43.32  268.34   60.65  268.39
   77.98  267.53  103.97   267.3   121.3  267.38  138.63  267.87  173.29  267.54
  181.95  267.28  210.73  265.09   225.1  264.51  253.83  263.98  289.75  263.95
   311.3  263.58  340.33  262.12  347.55  261.09  354.76  259.87  361.98  259.05
  369.19  258.83  376.41  258.95  383.62  259.95  392.43   261.9  399.47  263.47
  406.52  265.84  413.56  269.48  441.74  286.82  448.79  290.05  455.77  292.34
#Mann= 3 , 0 , 0
       0      .1       0  347.55     .04       0  392.43      .1       0
Bank Sta=347.55,392.43
XS Rating Curve= 0 ,0
Exp/Cntr=0.3,0.1

Type RM Length L Ch R = 1 ,25298.56,161.32,151.83,135.85
XS GIS Cut Line= 5
1602102.93719313720589.375652313 1601923.1267006720432.940523818
1601874.57786758720389.7860056461601829.62524444720323.256123394
1601721.73894894720271.111080542
#Sta/Elev= 30
       0  275.73    9.28  273.59   18.56   272.1   46.39  268.98   55.67  268.26
   74.23   267.7   92.78  266.48  148.45  267.02  167.01  266.93  194.85  266.19
  231.96     264   247.7  262.68   275.8  261.33  285.16  260.44  303.29  259.74
  320.19  260.48  328.64  259.65  337.08  257.11  345.53  254.47  353.98  254.26
  370.88  256.54  391.36  263.99  399.13  266.28  406.91  267.97  422.46   269.9
  430.23  271.23  461.33  278.02  484.66  282.53  492.43     284  503.41  285.24
#Mann= 3 , 0 , 0
       0      .1       0  337.08     .04       0  370.88      .1       0
Bank Sta=337.08,370.88
XS Rating Curve= 0 ,0
Exp/Cntr=0.3,0.1

Type RM Length L Ch R = 1 ,25146.73,279.76,277.15,281.24
XS GIS Cut Line= 3
 1602203.6310689 720425.748104141601887.16460209720208.177408174
1601786.47072625720159.628575176
#Sta/Elev= 30
       0  269.83   25.48  268.39   33.98  268.37   50.97   267.6   67.96   267.3
   76.45  266.73   84.95  266.51  135.92  263.96  195.38  262.18  220.86   261.1
  237.85  259.77  246.35  258.51  263.34  255.36  271.83  254.41  280.33  252.85
  288.82  252.53  297.32  252.54  305.81  252.94   314.3  254.25   322.8  255.09
  356.78  259.77  373.77  261.75  391.81  264.19  399.58  264.93  407.36  265.31
  430.67  265.59  438.44  266.12  446.21  267.02   477.3  271.89  495.83  275.73
#Mann= 3 , 0 , 0
       0      .1       0  263.34     .04       0   322.8      .1       0
Bank Sta=263.34,322.8
XS Rating Curve= 0 ,0
Exp/Cntr=0.3,0.1

Type RM Length L Ch R = 1 ,24869.58,161.97,197.83,185.22
XS GIS Cut Line= 2
1602275.55526593720125.4645816091601890.76081191719902.499570861
#Sta/Elev= 30
       0  268.05    8.09  265.22   16.18  262.78   24.27   260.7   32.36  259.13
   40.45  257.99   48.54  257.24   72.81  256.76  105.17  255.26  145.62  254.22
  153.71  253.77   161.8  252.68  169.89  251.03  177.98  249.52  194.17  248.89
  202.26  249.12  210.35  249.89  218.44  251.02  226.53  251.74  242.71  251.01
   250.8  251.17  291.25  250.89  299.34  251.35  307.43  252.74  323.61  254.89
  347.88  256.72  380.24  260.97  420.69  265.12  436.87  267.48  444.72  268.08
#Mann= 3 , 0 , 0
       0      .1       0  169.89     .04       0  218.44      .1       0
Bank Sta=169.89,218.44
XS Rating Curve= 0 ,0
Exp/Cntr=0.3,0.1

Type RM Length L Ch R = 1 ,24671.75,160.47,182.39,172.35
XS GIS Cut Line= 3
1602316.91167918720019.3763910231602117.32203253719812.594324619
  1601960.886904719729.881498054
#Sta/Elev= 30
       0  267.52    9.73  264.88   29.19   260.4   48.64  254.25   58.37  251.95
   77.83  249.34   87.56  248.37  107.02   247.8  126.48   247.5   136.2  248.14
  145.93  247.98  155.66   247.3  165.39  246.17  175.12  244.61  184.85  244.21
  194.58  245.15  204.31   247.1  214.03  247.45  233.49  245.09  243.22  244.88
  252.95  247.05  262.68  249.65  272.41  251.24  311.15  253.91  358.66  259.12
  390.33  261.94  406.17  262.24  414.09  262.74  437.84  265.58  464.35  267.56
#Mann= 3 , 0 , 0
       0      .1       0  214.03     .04       0  252.95      .1       0
Bank Sta=214.03,252.95
XS Rating Curve= 0 ,0
Exp/Cntr=0.3,0.1

Type RM Length L Ch R = 1 ,24489.35,147.84,144.43,135.91
XS GIS Cut Line= 3
1602439.18281414719942.0578792391602277.35337089719751.458757147
1602050.79215027719638.178146869
#Sta/Elev= 30
       0  262.64   18.37  260.61   36.73  259.06   45.91  256.64    55.1  254.84
   64.28  253.74   91.83  248.75  101.01  248.15  110.19  246.47  128.56  244.36
  137.74  242.64  146.92  241.36  165.29  241.47  183.66  239.78  192.84  239.32
   211.2  240.76  220.39  241.92  229.57  243.68  250.03  245.61  289.16  246.63
   328.3  248.96   359.6   249.8  390.91  251.43  414.38  253.96  422.21  255.06
  430.04  256.43  445.69  258.75  453.52  260.39  469.17  262.94  503.34  267.53
#Mann= 3 , 0 , 0
       0      .1       0  165.29     .04       0  220.39      .1       0
Bank Sta=165.29,220.39
XS Rating Curve= 0 ,0
Exp/Cntr=0.3,0.1

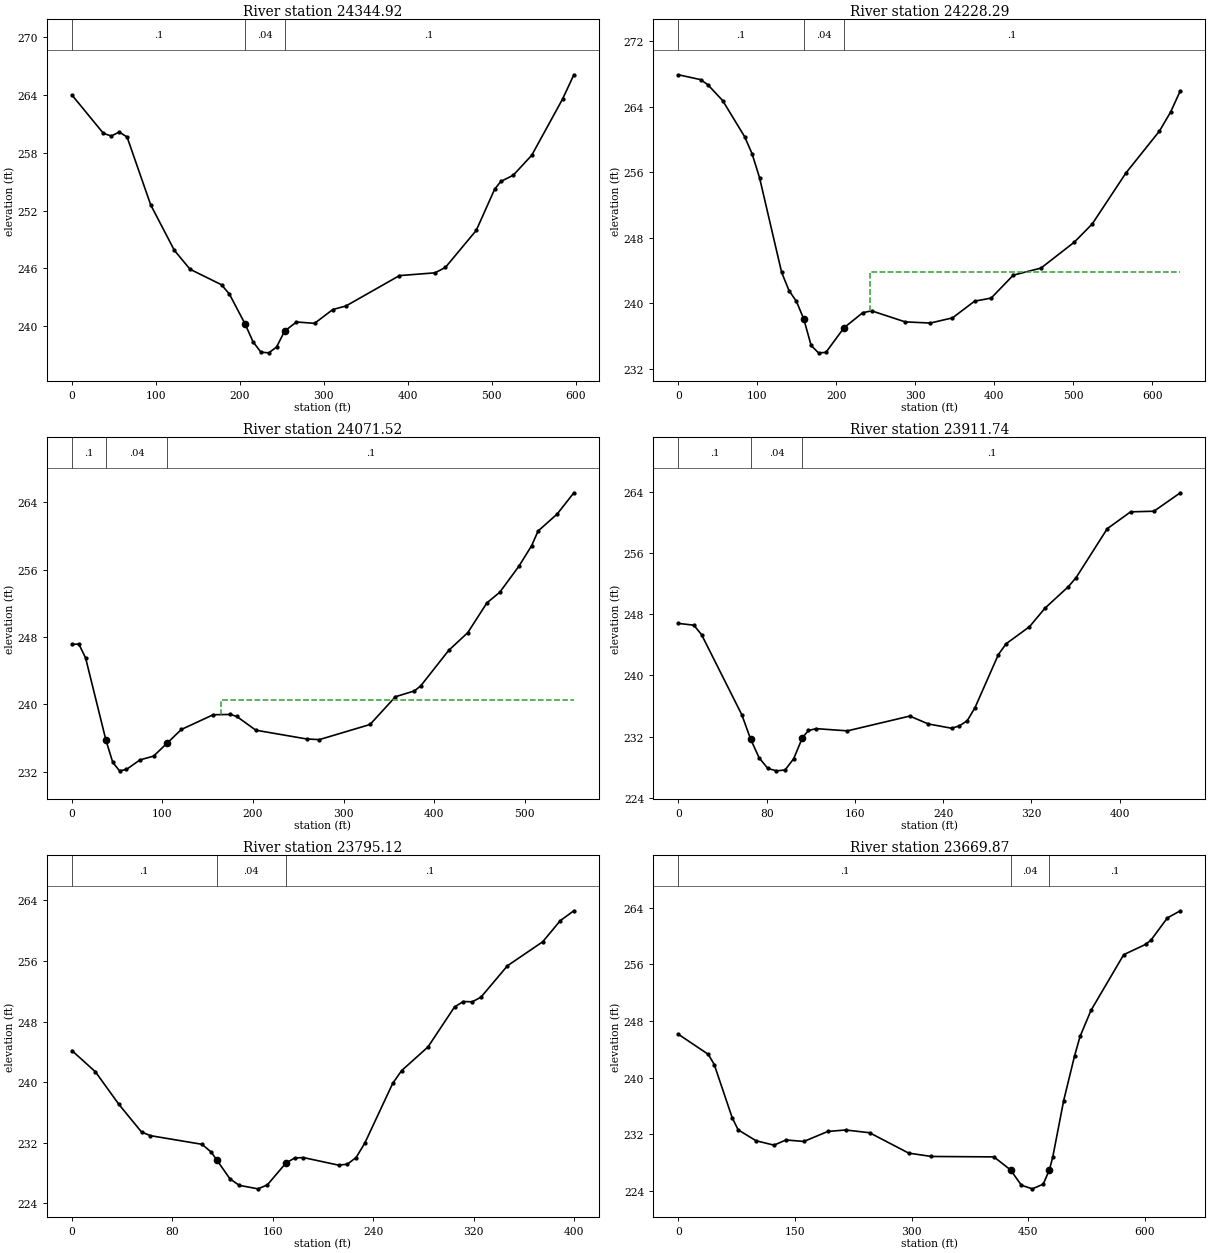
Type RM Length L Ch R = 1 ,24344.92,119.57,116.63,119.48
XS GIS Cut Line= 5
1602570.44447364719868.3355772791602392.43208605719668.745930597
 1602342.0851482719656.1591961231602225.20832802719638.178146869
 1602072.3694094719589.629313871
#Sta/Elev= 30
       0  263.98   37.52     260    46.9  259.73   56.28  260.14   65.66  259.63
    93.8  252.59  121.94  247.88  140.69  245.91  178.21   244.3  187.59  243.33
  206.35  240.22  215.73  238.39  225.11  237.31  234.49  237.24  243.87  237.85
  253.25  239.48  267.44  240.44  289.09   240.3  310.73  241.73  326.42   242.1
  390.16  245.25  432.65  245.54  444.93   246.1  481.66  249.94  503.69  254.23
  511.04  255.02  525.73  255.66  547.76  257.73  584.48  263.56  597.95  266.08
#Mann= 3 , 0 , 0
       0      .1       0  206.35     .04       0  253.25      .1       0
Bank Sta=206.35,253.25
XS Rating Curve= 0 ,0
Exp/Cntr=0.3,0.1

Type RM Length L Ch R = 1 ,24228.29,170.45,156.77,99.88
XS GIS Cut Line= 5
1602649.56109041719753.2568620891602466.15438804719591.427418813
1602399.62450577719580.6387892511602201.83296396719575.244474471
1602077.76372412719555.465320289
#Sta/Elev= 30
       0  267.93   28.01  267.34   37.34  266.71   56.01  264.78   84.02  260.34
   93.35  258.26  102.69  255.37  130.69  243.79  140.03  241.58  149.37  240.26
   158.7  238.11  168.04  234.87  177.37  233.97  186.71  234.02  209.65  237.03
  233.38  238.87   244.6   239.1  287.14  237.75     319  237.61  347.01  238.24
  375.02  240.28  396.03  240.66  424.04  243.46  459.05  244.32  501.06  247.47
  524.04  249.72  566.57  255.93   609.1  261.06  623.27  263.39  635.49  265.98
#Mann= 3 , 0 , 0
       0      .1       0   158.7     .04       0  209.65      .1       0
#XS Ineff= 2 , 0
                          243.03          243.82
Permanent Ineff=
       F       F
Bank Sta=158.7,209.65
XS Rating Curve= 0 ,0
Exp/Cntr=0.3,0.1

Type RM Length L Ch R = 1 ,24071.52,160.04,159.78,141.18
XS GIS Cut Line= 5
1602631.58004111719483.5411232861602525.49185057719524.897536561
1602471.54870282719530.2918513421602244.98748221 719519.50322178
 1602086.7542488719499.724067599
#Sta/Elev= 30
       0  247.11    7.51  247.17   15.03  245.53   37.57  235.72   45.08   233.1
   52.59  232.09    60.1  232.25   75.13  233.39   90.16  233.84  105.18  235.39
   120.9  237.01  156.07  238.76  175.08  238.79  182.09  238.55  203.12  236.92
  259.18  235.88   273.2   235.8  329.26   237.6  357.29   240.9  378.31  241.59
  385.32   242.2  416.06   246.4  437.22  248.52  458.38  252.06  472.49  253.31
  493.66  256.41  507.77  258.86  514.82  260.59  535.98  262.62  554.36  265.14
#Mann= 3 , 0 , 0
       0      .1       0   37.57     .04       0  105.18      .1       0
#XS Ineff= 2 , 0
                          165.04          240.47
Permanent Ineff=
       F       F
Bank Sta=37.57,105.18
XS Rating Curve= 0 ,0
Exp/Cntr=0.3,0.1

Type RM Length L Ch R = 1 ,23911.74,114.17,116.63,127.13
XS GIS Cut Line= 5
1602548.86721458719391.8377721011602491.32785694719390.039667159
1602437.38470919719417.0112410631602336.69083342719431.396080449
1602102.93719313719402.626401633
#Sta/Elev= 30
       0  246.78   14.01  246.55   21.01  245.31   57.57  234.83   65.39   231.7
   73.22  229.22   81.05  227.85   88.87  227.53    96.7  227.64  104.52  229.11
  112.35  231.83  117.88   232.8  124.95  233.04  153.23  232.75   209.8  234.68
  226.65  233.65  247.81  233.09  254.86  233.41  261.91  234.08  268.96  235.79
  290.12  242.71  297.18  244.13  318.33  246.35  332.44  248.78   353.6  251.58
  360.65  252.77  388.86  259.15  410.02  261.35  431.18  261.43  455.11  263.84
#Mann= 3 , 0 , 0
       0      .1       0   65.39     .04       0  112.35      .1       0
Bank Sta=65.39,112.35
XS Rating Curve= 0 ,0
Exp/Cntr=0.3,0.1

Type RM Length L Ch R = 1 ,23795.12,110.83,125.24,129.07
XS GIS Cut Line= 6
1602527.20479232719338.1114632931602485.70923696 719301.35825713
1602438.28574514719293.0591460621602375.44961847719315.585304677
1602304.31438079719314.3997174051602146.63127048719300.172669858
#Sta/Elev= 30
       0  244.18    18.7  241.38    37.4  237.08   55.43  233.43   62.54  232.95
  103.58  231.81  111.01  230.77  115.18  229.78  125.88  227.25  133.32  226.39
  148.19  225.93  155.63  226.45  170.33  229.31  177.33     230  184.33  230.06
  212.33  229.06  219.33  229.18  226.34  230.06  233.34  231.99  255.53  239.86
  262.56  241.53  283.64  244.67  304.73  249.94  311.76  250.66  318.79  250.62
  325.81  251.23   346.9  255.38  375.01  258.55  389.07  261.35   399.8  262.64
#Mann= 3 , 0 , 0
       0      .1       0  115.18     .04       0  170.33      .1       0
Bank Sta=115.18,170.33
XS Rating Curve= 0 ,0
Exp/Cntr=0.3,0.1

Type RM Length L Ch R = 1 ,23669.87,136.57,159.26,175.86
XS GIS Cut Line= 5
1602773.63033023 719345.087044031602523.69374561719231.806433752
1602390.63398117719192.2481253891602322.30599396719194.046230316
1602158.67844577719181.459495828
#Sta/Elev= 30
       0  246.13   38.43   243.3   46.11  241.86   69.17  234.35   76.85  232.64
   99.91   231.1  122.97  230.48  138.34  231.21  161.39     231  192.14  232.41
  215.19  232.62  245.93  232.23  296.32  229.35  325.53  228.88  405.86  228.82
  427.23  226.99  441.23  224.82  455.24  224.31  469.24  224.96  477.34  227.02
  481.58   228.8  495.62  236.77  509.66  243.09  516.68  245.82  530.72   249.5
  572.85  257.37  600.93  258.82  607.95  259.43  629.01  262.56  645.69  263.57
#Mann= 3 , 0 , 0
       0      .1       0  427.23     .04       0  477.34      .1       0
Bank Sta=427.23,477.34
XS Rating Curve= 0 ,0
Exp/Cntr=0.3,0.1

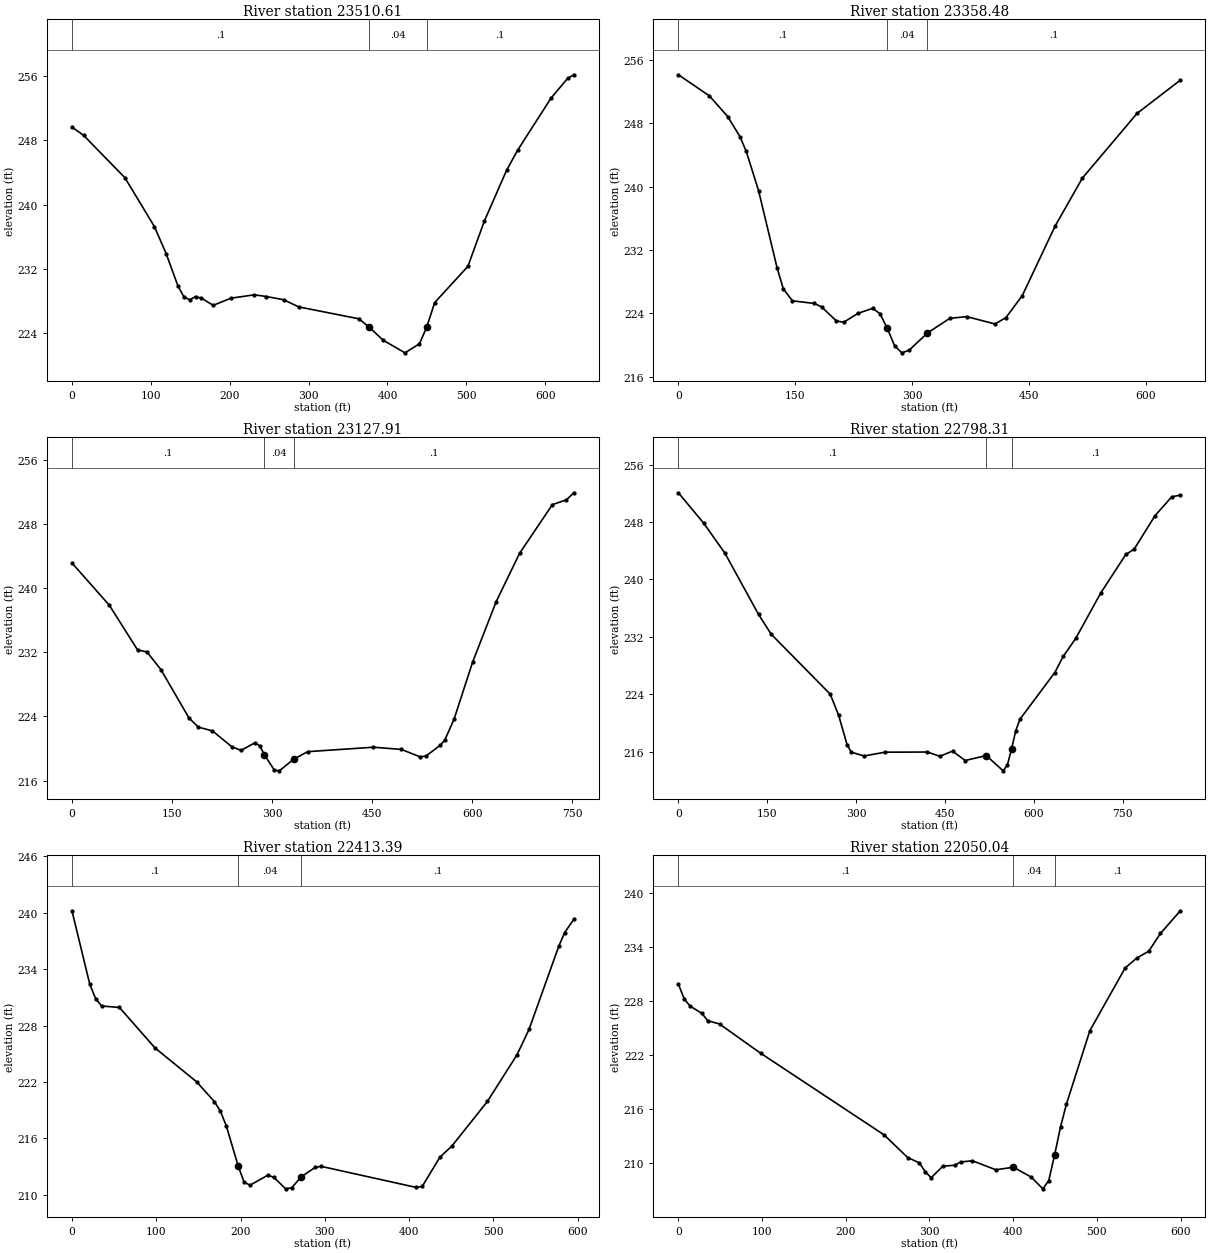
Type RM Length L Ch R = 1 ,23510.61,136.38,152.13,115.93
XS GIS Cut Line= 5
1602767.87971945719253.3118030881602516.28531696719160.236417204
1602430.48144558719080.2497574391602373.76363224719032.257761568
1602197.79298081 719019.16903545
#Sta/Elev= 30
       0  249.64   14.93   248.6   67.17  243.33  104.49  237.27  119.42   233.9
  134.35  229.88  141.81  228.54  149.27  228.14  156.74  228.55   164.2  228.35
  179.13  227.46  201.52  228.35  231.37  228.77   246.3  228.56  268.26  228.16
   287.4  227.27  363.96  225.78  376.68  224.75  394.73  223.11  422.24  221.55
  440.58  222.68  449.75  224.74  459.86   227.8  501.98  232.31  523.03  237.99
  551.11  244.28  565.15  246.78  607.27  253.23  628.32  255.69  636.32  256.15
#Mann= 3 , 0 , 0
       0      .1       0  376.68     .04       0  449.75      .1       0
Bank Sta=376.68,449.75
XS Rating Curve= 0 ,0
Exp/Cntr=0.3,0.1

Type RM Length L Ch R = 1 ,23358.48,254.6,230.58,154.79
XS GIS Cut Line= 5
1602766.43791051719152.6898170411602636.97435589719084.361829862
1602507.51080127718969.2831146721602430.19228952 718949.50396049
1602185.65001968718936.917226017
#Sta/Elev= 30
       0  254.13   39.58  251.48   63.32  248.85   79.15  246.29   87.07  244.45
   102.9  239.49  126.64  229.75  134.56   227.1  146.39  225.57  174.49  225.24
  183.85   224.8  202.58  223.05  211.95  222.85  230.68     224  249.41  224.62
  258.78  223.94  268.14  222.09  277.51  219.89  286.87     219  296.24  219.34
   319.6   221.5  348.51  223.37  370.18  223.57  406.42  222.65  420.44  223.45
  441.47  226.24  483.52  235.01  518.57  241.08  588.66  249.24  644.28  253.45
#Mann= 3 , 0 , 0
       0      .1       0  268.14     .04       0   319.6      .1       0
#XS Ineff= 2 , 0
          249.35  224.61
Permanent Ineff=
       F       F
Bank Sta=268.14,319.6
XS Rating Curve= 0 ,0
Exp/Cntr=0.3,0.1

Type RM Length L Ch R = 1 ,23127.91,285.95,329.6,278.45
XS GIS Cut Line= 6
 1602919.2768292718796.6650418341602694.51371354718780.482097492
1602631.58004111718785.8764122721602590.22362788718800.261251673
1602392.43208605718812.8479861471602171.26518027718827.232825547
#Sta/Elev= 30
       0  243.12   56.14  237.84   98.25   232.3  112.29  232.04  133.34  229.84
  175.45   223.8  189.49  222.67  210.54  222.21   239.4  220.24  253.45  219.78
  274.52  220.73  281.55  220.33  288.51  219.21  303.33  217.32  310.74  217.23
   332.3  218.68  353.34  219.62  451.54  220.17  493.62   219.9  521.68  218.97
  530.49  219.07  551.53  220.39  558.55  221.03  572.58  223.66  600.64  230.82
  635.71   238.3  670.78  244.32  719.89  250.38  740.93  250.98  752.12  251.86
#Mann= 3 , 0 , 0
       0      .1       0  288.51     .04       0   332.3      .1       0
Bank Sta=288.51,332.3
XS Rating Curve= 0 ,0
Exp/Cntr=0.3,0.1

Type RM Length L Ch R = 1 ,22798.31,296.47,384.92,315.04
XS GIS Cut Line= 3
1602956.46531829 718442.645813541602373.29255126 718549.99602437
1602120.87448797718579.009594858
#Sta/Elev= 30
       0  252.08   42.71  247.84   78.29  243.69  135.23  235.13  156.59  232.37
  256.23  224.01  270.47  221.06   284.7  216.95  291.82  215.93  313.17   215.4
  348.76  215.93  419.94  215.95  441.29  215.36  462.64  216.08     484  214.77
  519.59  215.46  548.06  213.33  555.17  214.15  562.29  216.41  569.41  218.94
  576.53  220.54  635.25  227.03  649.34  229.27  670.48  231.78  712.75  238.11
  755.03  243.48  769.12  244.22  804.35  248.89  832.54  251.51  847.05  251.76
#Mann= 3 , 0 , 0
       0      .1       0  519.59     .04       0  562.29      .1       0
Bank Sta=519.59,562.29
XS Rating Curve= 0 ,0
Exp/Cntr=0.3,0.1

Type RM Length L Ch R = 1 ,22413.39,276.79,363.35,259.28
XS GIS Cut Line= 2
1602756.27168186718206.1852139831602164.39484367718271.465747595
#Sta/Elev= 30
       0  240.21   21.13   232.4   28.17  230.84   35.21  230.08   56.34  229.92
   98.59  225.61  147.89  222.01  169.02   219.9  176.06   218.9   183.1  217.33
  197.19  213.06  204.23  211.33  211.27  211.01   232.4  212.07  239.44  211.85
  253.53  210.62  260.57  210.73  272.19   211.9  288.74  212.92  295.78  213.01
  408.46  210.77   415.5  210.87  436.63     214  450.72  215.17  492.97  219.93
  528.18  224.91  542.27  227.58  577.48  236.41  584.52  237.89  595.47   239.3
#Mann= 3 , 0 , 0
       0      .1       0  197.19     .04       0  272.19      .1       0
Bank Sta=197.19,272.19
XS Rating Curve= 0 ,0
Exp/Cntr=0.3,0.1

Type RM Length L Ch R = 1 ,22050.04,164.27,219.76,171.83
XS GIS Cut Line= 2
1602695.34318377718008.8929345761602097.66363157718058.216004446
#Sta/Elev= 30
       0  229.83    7.02  228.17   14.05  227.39    28.1  226.57   35.12  225.77
   49.17   225.4   98.33  222.15  245.83  213.08  273.93  210.57  287.98  209.97
     295  208.97  302.02  208.33  316.07  209.61  330.12  209.71  337.14  210.07
  351.19  210.21  379.28  209.21  400.36  209.49  421.43   208.4  435.48  207.09
   442.5  208.01  449.52  210.87  456.55  213.96  463.57  216.49  491.67  224.67
  533.81  231.63  547.86  232.74   561.9  233.48  575.95  235.46  599.71  237.98
#Mann= 3 , 0 , 0
       0      .1       0  400.36     .04       0  449.52      .1       0
Bank Sta=400.36,449.52
XS Rating Curve= 0 ,0
Exp/Cntr=0.3,0.1