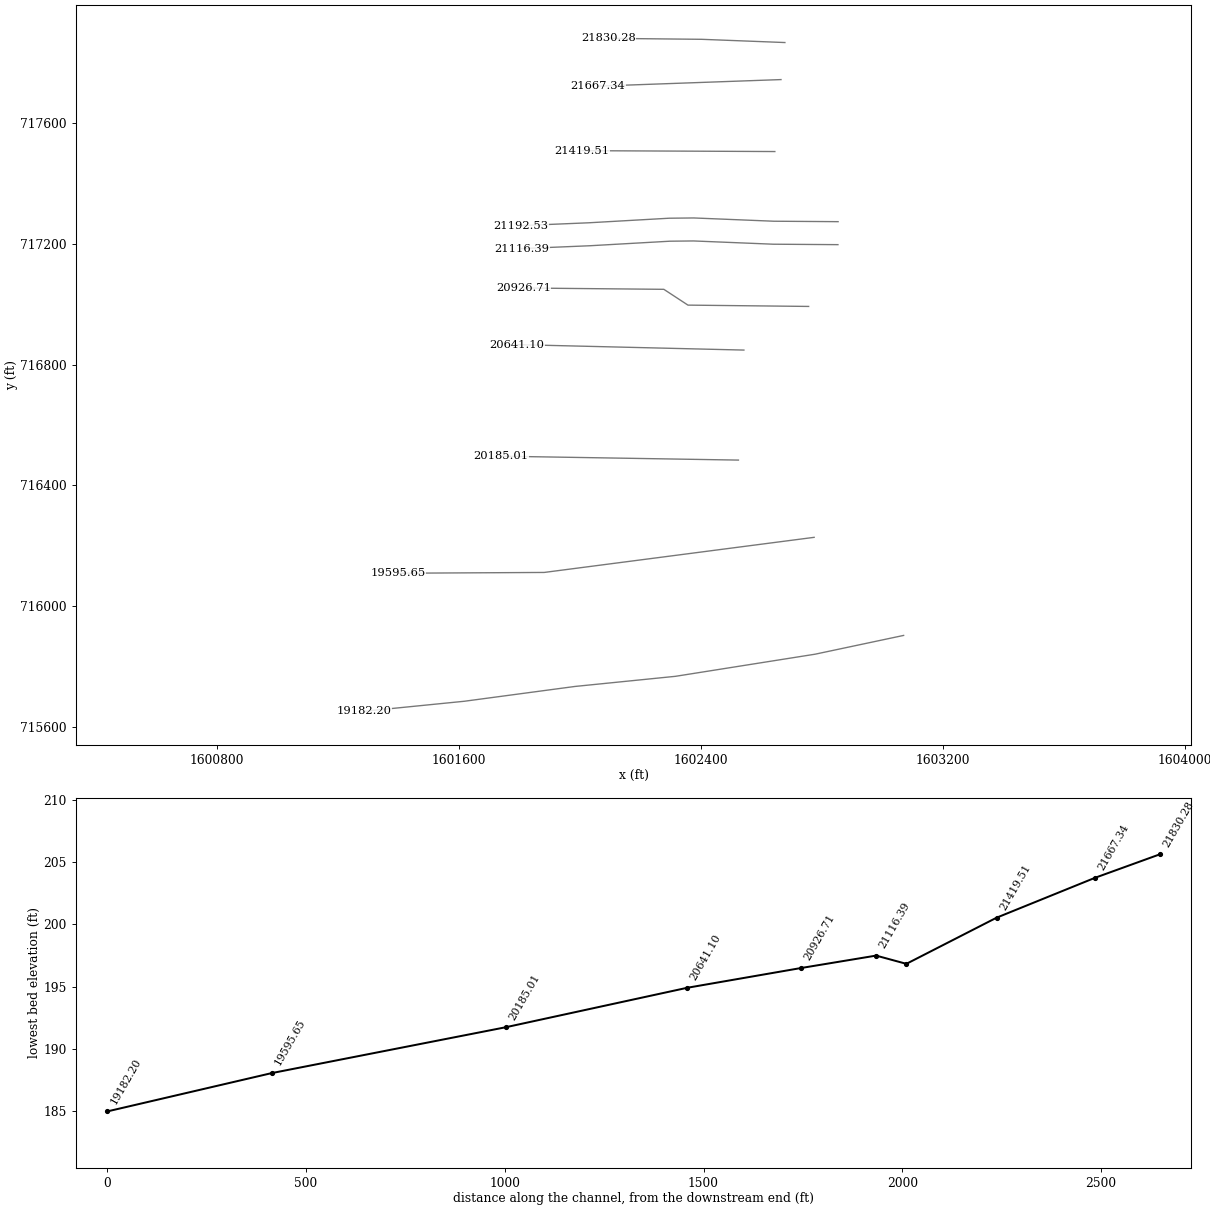
HEC-RAS study StonyRun.prj: StonyRun

--- StonyRun.g01 (geometry) --- (continued)

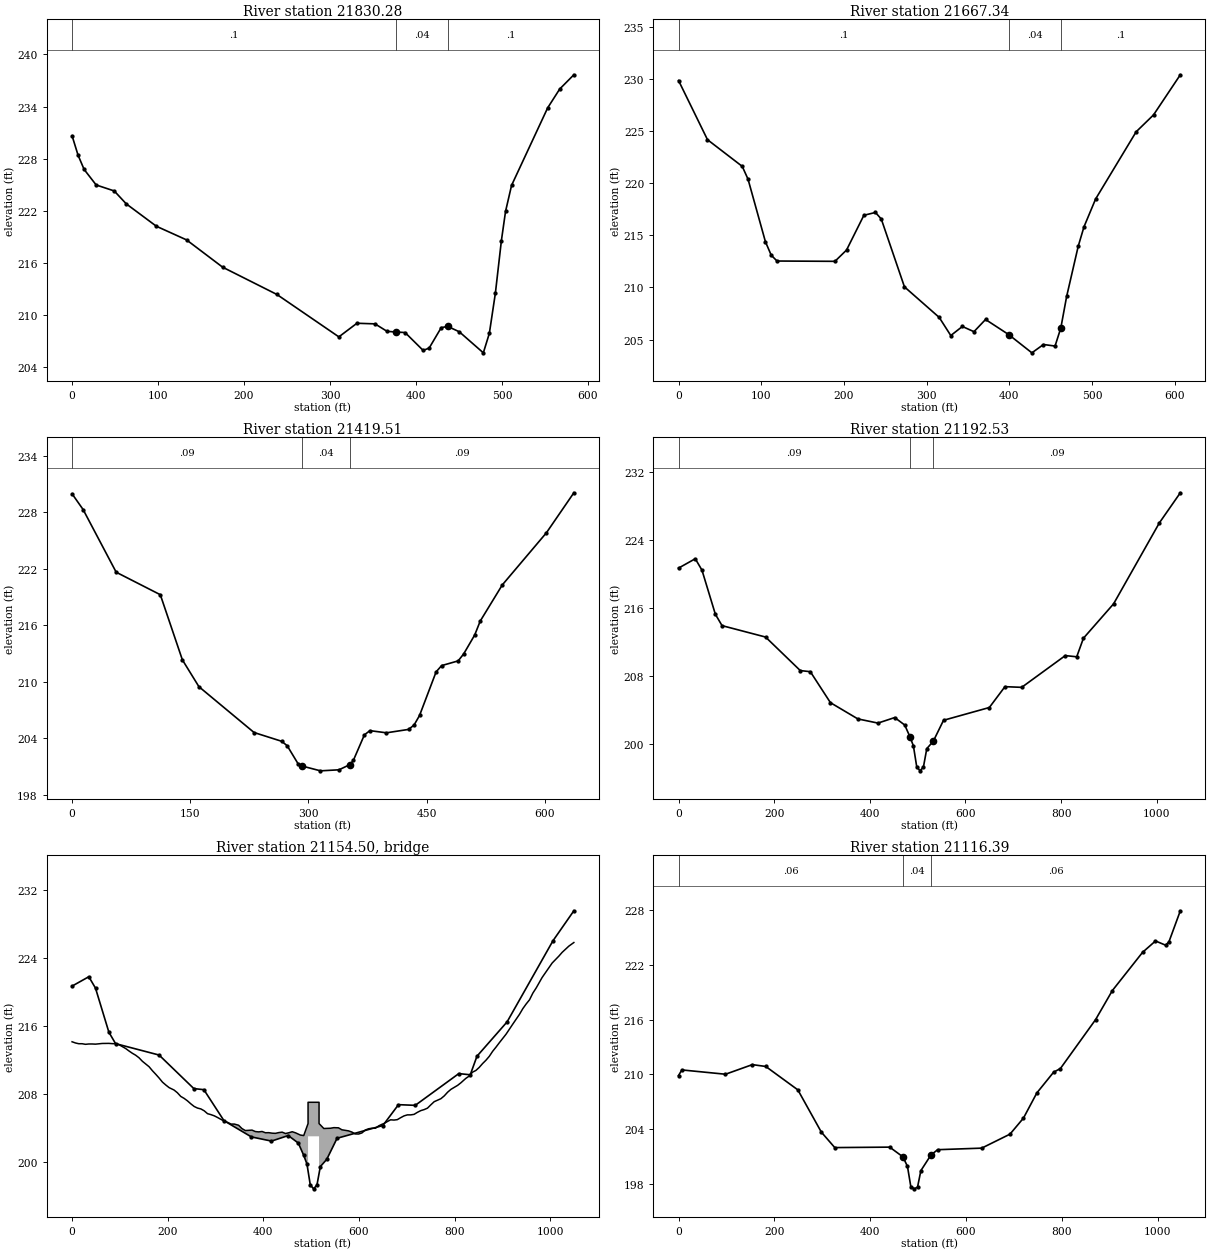
Type RM Length L Ch R = 1 ,21830.28,147.68,162.94,153
XS GIS Cut Line= 4
1602677.77437885717864.4264551251602402.71812631717875.096740782
1602173.89977831717877.4679153561602094.46542951717878.653502673
#Sta/Elev= 30
       0  230.63    7.01  228.38   14.01  226.75   28.02  224.96   49.04  224.27
   63.05  222.78   98.07   220.2   133.1  218.63  175.13  215.48  238.18  212.34
  310.26  207.45  331.27  209.02  352.27  208.95  366.27  208.09  376.44  208.01
  387.27  207.95  408.27  205.89  415.27  206.16  429.27  208.51  436.78  208.66
  450.27  208.04  478.27  205.61  485.27  207.86  492.27  212.48  499.27  218.55
  504.09  221.91  511.09  224.91   553.1  233.85   567.1  236.02  583.54  237.66
#Mann= 3 , 0 , 0
       0      .1       0  376.44     .04       0  436.78      .1       0
Bank Sta=376.44,436.78
XS Rating Curve= 0 ,0
Exp/Cntr=0.3,0.1

Type RM Length L Ch R = 1 ,21667.34,235.5,247.83,262.77
XS GIS Cut Line= 2
1602664.87893479717741.9680860191602058.49531136717720.207908139
#Sta/Elev= 30
       0  229.86   35.02  224.18   77.05  221.62   84.05  220.39  105.07  214.39
  112.07   213.1  119.08  212.54  189.12  212.51  203.13  213.59  224.14  216.93
  238.15   217.2  245.16  216.57  273.18  210.06   315.2  207.13  329.21  205.39
  343.22  206.26  357.23  205.76  371.24  206.93  399.26  205.48  427.28  203.73
  441.28  204.53  455.29  204.38   462.3  206.13   469.3  209.14  483.31  213.96
  490.32  215.83  504.32  218.49  553.36  224.94  574.37  226.56  606.77  230.41
#Mann= 3 , 0 , 0
       0      .1       0  399.26     .04       0   462.3      .1       0
Bank Sta=399.26,462.3
XS Rating Curve= 0 ,0
Exp/Cntr=0.3,0.1

Type RM Length L Ch R = 1 ,21419.51,225.34,226.98,225.1
XS GIS Cut Line= 2
1602644.56943546717504.056807935  1602007.721563 717506.95816499
#Sta/Elev= 30
       0  229.96      14  228.29      56  221.63     112  219.24     140  212.32
     161  209.47     231   204.6     266  203.67     273   203.2     287  201.26
  292.38  201.03  315.25  200.53  338.81  200.64   352.5  201.19     357  201.64
     371  204.35     378   204.8     399  204.57     427  204.93     434  205.39
     441  206.41     462  211.04     469  211.71     490  212.21     497  212.95
     511  214.96  518.01  216.44  546.01  220.28  602.01  225.82  636.85  230.07
#Mann= 3 , 0 , 0
       0     .09       0  292.38     .04       0   352.5     .09       0
Bank Sta=292.38,352.5
XS Rating Curve= 0 ,0
Exp/Cntr=0.5,0.3

Type RM Length L Ch R = 1 ,21192.53,76.11,76.14,76.37
BEGIN DESCRIPTION:
Channel bottom center lowered 1.5 ft based on bridge survey info
END DESCRIPTION:
XS GIS Cut Line= 6
 1602853.7256404717272.2297230961602641.16340764 717273.67572467
1602376.78034417717284.4809236971602295.18277009717283.622001842
1602028.68792845717268.4848916981601805.23301208 717259.16511634
#Sta/Elev= 30
       0  220.65      35  221.75      49  220.41      77  215.23      91  213.89
     182  212.55  254.61  208.61  275.63  208.48  317.66  204.84  375.02  202.93
  417.05  202.44  452.08  203.09  473.09  202.21  484.17   200.8  491.17  199.76
  498.17  197.29  505.17  196.83  512.17  197.29  519.17  199.44  532.66   200.3
  554.18  202.77  649.95  204.27  682.61  206.72  717.66  206.64  808.79  210.37
  832.71  210.23  846.73  212.41   909.8  216.45  1005.6  225.97 1049.37   229.5
#Mann= 3 , 0 , 0
       0     .09       0  484.17     .04       0  532.66     .09       0
Bank Sta=484.17,532.66
XS Rating Curve= 0 ,0
Exp/Cntr=0.5,0.3

Type RM Length L Ch R = 3 ,21154.50,,,
BEGIN DESCRIPTION:
Bailiff Road, MDE Bridge #: CE041307PF-2
Top of road obtained from DEM.
Openings from MDE2 bridge/culvert surveys.
END DESCRIPTION:
Bridge Culvert--1,0,-1,-1, 0
Deck Dist Width WeirC Skew NumUp NumDn MinLoCord MaxHiCord MaxSubmerge Is_Ogee
28.5,19,2.6,0, 148, 148, , , 0.95, 0, 2,2,,
       0       7      14      21      28      35      42      49      56      63
      70      77      84      91      98     105     112     119     126     133
     140     147     154     161     168     175     182     189     196     203
  213.25  220.26  227.27  234.27  241.28  248.29  255.29   262.3  269.31  276.31
  283.32  290.33  297.33  304.34  311.35  318.35  325.36  332.36  339.37  348.29
   355.3   362.3  369.31  376.31  383.32  390.32  397.33  404.33  411.34  418.34
  425.35  432.36  439.36  446.37  453.37  460.38  467.38  477.45  484.45   493.5
   493.5   516.5   516.5  526.45  533.45  540.45  547.45  557.14  564.15  571.17
  578.18  585.19  592.21  599.22  606.23  613.25  620.26  627.27  634.29   641.3
  648.31  652.11  659.12  666.13  673.14  680.15  687.16  694.17  701.18  708.19
   715.2  722.21  729.22  736.23  743.24  750.25  757.26  764.27  771.28  778.29
   785.3  792.31  799.32  806.33  813.34  823.48  830.48  837.49   844.5  851.51
  858.52  865.53  872.54  879.54  886.55  893.56  900.57  907.58  914.59   921.6
   928.6  935.61  942.62  949.63  956.64  963.65  970.66  977.66  982.97  989.97
  996.97 1003.97 1010.97 1017.97 1024.98 1031.98 1038.98 1049.37
  214.11  213.97  213.88  213.88  213.81  213.85  213.85  213.83  213.87  213.91
  213.92  213.92  213.89  213.88  213.77  213.54  213.32  213.03  212.76  212.53
  212.23  211.82   211.5  211.18  210.71  210.29  209.85  209.37  209.03  208.72
  208.44  208.12  207.69  207.46  207.17  206.82  206.51  206.32  206.22     206
  205.66  205.55  205.41  205.21  204.99  204.77  204.64  204.44  204.44   204.3
  203.91  203.68  203.71  203.73  203.56  203.52  203.57  203.42  203.43  203.37
  203.35  203.44  203.49  203.33  203.42  203.54  203.41  203.15  203.09   204.5
     207     207   204.5  203.92  203.94  203.95  204.02     204  203.77   203.7
  203.64   203.5  203.28  203.27   203.4  203.74  203.89  203.95  203.95  204.23
  204.42   204.5  204.73  204.94  204.91  204.96  205.19   205.4  205.52  205.52
  205.58  205.82  206.02  206.14  206.31   206.7  207.07  207.24  207.42  207.75
  208.18  208.52  208.75  208.99   209.3  209.81  210.08  210.54  210.74   211.1
  211.55  211.94   212.4  212.99  213.48     214  214.49     215   215.6  216.18
  216.75  217.33     218  218.55  219.04  219.83  220.44  221.14  221.66  222.23
   222.8  223.36  223.77  224.17  224.62  224.98  225.35  225.77
                                                                                
                                                                                
                                                                                
                                                                                
                                                                                
                                                                                
                                                                                
     203     203
                                                                                
                                                                                
                                                                                
                                                                                
                                                                                
                                                                                
                                                                
       0       7      14      21      28      35      42      49      56      63
      70      77      84      91      98     105     112     119     126     133
     140     147     154     161     168     175     182     189     196     203
  213.25  220.26  227.27  234.27  241.28  248.29  255.29   262.3  269.31  276.31
  283.32  290.33  297.33  304.34  311.35  318.35  325.36  332.36  339.37  348.29
   355.3   362.3  369.31  376.31  383.32  390.32  397.33  404.33  411.34  418.34
  425.35  432.36  439.36  446.37  453.37  460.38  467.38   480.5   480.5   503.5
   503.5  512.45  519.45  526.45  533.45  540.45  547.45  557.14  564.15  571.17
  578.18  585.19  592.21  599.22  606.23  613.25  620.26  627.27  634.29   641.3
  648.31  652.11  659.12  666.13  673.14  680.15  687.16  694.17  701.18  708.19
   715.2  722.21  729.22  736.23  743.24  750.25  757.26  764.27  771.28  778.29
   785.3  792.31  799.32  806.33  813.34  823.48  830.48  837.49   844.5  851.51
  858.52  865.53  872.54  879.54  886.55  893.56  900.57  907.58  914.59   921.6
   928.6  935.61  942.62  949.63  956.64  963.65  970.66  977.66  982.97  989.97
  996.97 1003.97 1010.97 1017.97 1024.98 1031.98 1038.98 1047.16
  214.11  213.97  213.88  213.88  213.81  213.85  213.85  213.83  213.87  213.91
  213.92  213.92  213.89  213.88  213.77  213.54  213.32  213.03  212.76  212.53
  212.23  211.82   211.5  211.18  210.71  210.29  209.85  209.37  209.03  208.72
  208.44  208.12  207.69  207.46  207.17  206.82  206.51  206.32  206.22     206
  205.66  205.55  205.41  205.21  204.99  204.77  204.64  204.44  204.44   204.3
  203.91  203.68  203.71  203.73  203.56  203.52  203.57  203.42  203.43  203.37
  203.35  203.44  203.49  203.33  203.42  203.54  203.41   204.5     207     207
   204.5  203.96  203.95  203.92  203.94  203.95  204.02     204  203.77   203.7
  203.64   203.5  203.28  203.27   203.4  203.74  203.89  203.95  203.95  204.23
  204.42   204.5  204.73  204.94  204.91  204.96  205.19   205.4  205.52  205.52
  205.58  205.82  206.02  206.14  206.31   206.7  207.07  207.24  207.42  207.75
  208.18  208.52  208.75  208.99   209.3  209.81  210.08  210.54  210.74   211.1
  211.55  211.94   212.4  212.99  213.48     214  214.49     215   215.6  216.18
  216.75  217.33     218  218.55  219.04  219.83  220.44  221.14  221.66  222.23
   222.8  223.36  223.77  224.17  224.62  224.98  225.35  225.77
                                                                                
                                                                                
                                                                                
                                                                                
                                                                                
                                                                                
                                                                     203     203
                                                                                
                                                                                
                                                                                
                                                                                
                                                                                
                                                                                
                                                                                
                                                                
BR Coef=-1 , 0 , 0 ,, 0 ,,,0.8,0,,0,
WSPro=,,,, 1 ,,,, 0 ,,,, 0 ,,,,-1 ,-1 ,-1 , 0 , 0 , 0 , 0 , 0
BC Design=,, 0 ,, 0 ,,,,,,
BC Use User HTab Curves=0
BC User HTab FreeFlow(D)= 0

Type RM Length L Ch R = 1 ,21116.39,223.06,189.69,183.23
BEGIN DESCRIPTION:
Channel bottom center lowered 1.5 ft based on bridge survey info
END DESCRIPTION:
XS GIS Cut Line= 6
 1602853.2086456717196.2314815521602639.27139215717197.686837018
1602375.71174957 717208.465464921602297.93403925717207.646752164
 1602032.6187212717192.5864400421601806.92148411717183.183874831
#Sta/Elev= 30
       0  209.88       7  210.49      98  210.02     154  211.07     182  210.87
  248.97  208.31  298.02  203.69  326.05     202  440.65  202.05  468.19  200.99
  477.72  199.95  484.72  197.74  491.72  197.49  498.72  197.67  505.72  199.48
  526.73  201.19  540.73  201.77  632.65  201.94  691.71  203.47  719.75  205.22
  747.79  207.98  782.84  210.25  796.86  210.64  870.31  215.99  905.35  219.17
  968.43  223.35  995.35  224.59 1016.35  224.13 1023.35  224.49 1047.16  227.89
#Mann= 3 , 0 , 0
       0     .06       0  468.19     .04       0  526.73     .06       0
Bank Sta=468.19,526.73
XS Rating Curve= 0 ,0
Exp/Cntr=0.5,0.3

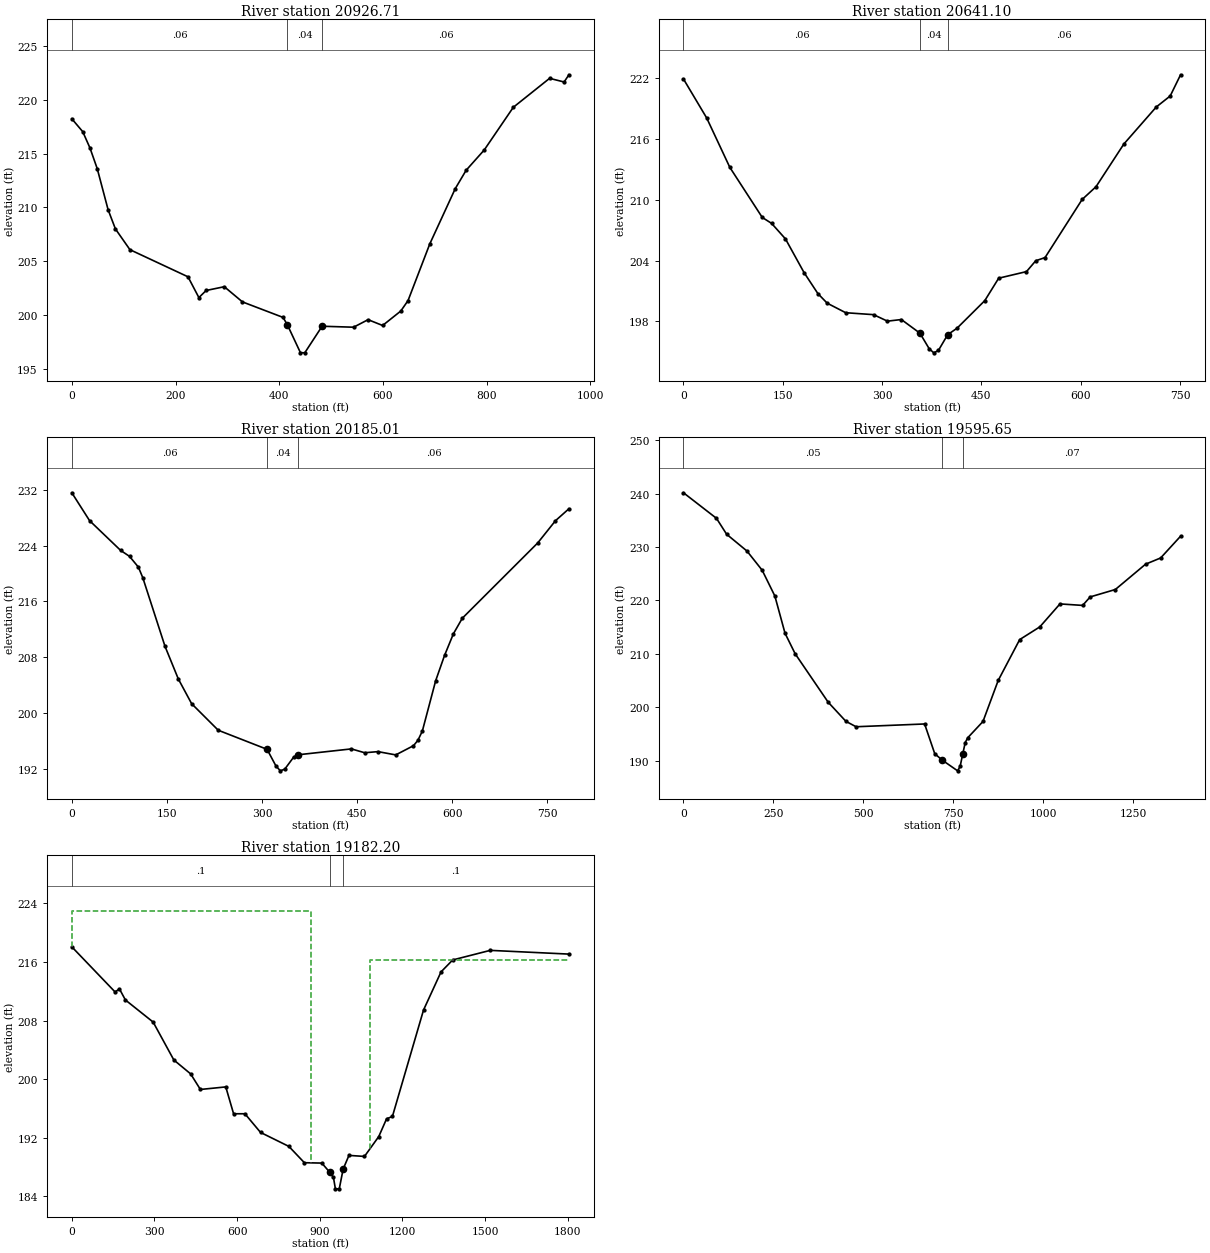
Type RM Length L Ch R = 1 ,20926.71,179.98,285.61,216.62
XS GIS Cut Line= 4
1602756.27168186716991.9672886581602357.33508749 716996.31932421
1602277.54776864717048.5437511061601813.33064067717052.895786688
#Sta/Elev= 30
       0  218.22      21  217.03      35  215.51      49  213.59      70  209.77
   84.01     208  112.01  206.07  224.01  203.55  245.01  201.62  259.02  202.28
  294.02  202.63  329.02  201.22  407.33  199.78  415.69  199.09  440.79  196.51
  449.16  196.49  482.62  198.96  543.32  198.87  571.32  199.57  599.32  199.03
  634.33  200.37  648.33  201.34  690.33  206.61  739.33  211.73  760.33  213.44
  795.33  215.33  851.34  219.29  921.34  221.98  949.34  221.64  958.56  222.31
#Mann= 3 , 0 , 0
       0     .06       0  415.69     .04       0  482.62     .06       0
Bank Sta=415.69,482.62
XS Rating Curve= 0 ,0
Exp/Cntr=0.3,0.1

Type RM Length L Ch R = 1 ,20641.10,366.8,456.08,398.05
XS GIS Cut Line= 2
1602542.26387735716847.6902195811601791.60318488716865.747349635
#Sta/Elev= 30
       0  221.87   35.01  218.04   70.02  213.17  119.03  208.24  133.04  207.66
  154.04  206.13  182.05  202.82  203.06  200.74  217.06   199.8  245.07  198.86
  287.08  198.67  308.09  198.03   329.1  198.19   357.1  196.85  371.11  195.32
  378.11  194.91  385.11  195.15  399.12   196.7  413.12  197.33  455.13  200.05
  476.14  202.26  518.15  202.91  532.15  203.98  546.16  204.29  602.17  210.01
  623.18  211.27  665.19  215.47  714.21  219.12  735.21   220.2  750.88  222.29
#Mann= 3 , 0 , 0
       0     .06       0   357.1     .04       0  399.12     .06       0
Bank Sta=357.1,399.12
XS Rating Curve= 0 ,0
Exp/Cntr=0.3,0.1

Type RM Length L Ch R = 1 ,20185.01,335.52,589.36,372.14
XS GIS Cut Line= 2
1602524.20674732716483.968028367 1601740.0113847716496.865978405
#Sta/Elev= 30
       0  231.55      28  227.56   77.01   223.3   91.01  222.45  105.01  220.91
  112.02  219.38  147.02  209.57  168.02   204.9  189.03  201.36  231.03  197.56
  308.04  194.83  322.04  192.45  329.04  191.75  336.05     192  350.05  193.72
  357.05  194.05  441.06  194.89  462.06  194.34  483.07   194.5  511.07  194.03
  539.07  195.35  546.07  196.12  553.07  197.45  574.08  204.65  588.08  208.27
  602.08  211.37  616.08  213.59   735.1  224.37   763.1  227.55   784.3  229.26
#Mann= 3 , 0 , 0
       0     .06       0  308.04     .04       0  357.05     .06       0
Bank Sta=308.04,357.05
XS Rating Curve= 0 ,0
Exp/Cntr=0.3,0.1

Type RM Length L Ch R = 1 ,19595.65,395.92,413.45,389.58
XS GIS Cut Line= 3
 1602774.4269781716228.5886175331601881.88883519716112.507067129
1601399.50550359716109.927477121
#Sta/Elev= 30
       0  240.16   91.77  235.37     120  232.39  176.47  229.25  218.83  225.65
  254.12  220.82  282.36  213.85  310.59     210  402.36  200.93  451.77  197.34
  480.01  196.33   670.6  196.85  698.84  191.27  720.01  190.06  762.37  188.07
  769.43  188.92  776.49  191.17  783.54  193.37   790.6  194.27  832.96  197.32
  875.31  205.01  935.06  212.66  991.06  215.04 1047.06  219.34 1110.06  219.06
 1131.06  220.65 1201.06  222.04 1285.06  226.78 1327.06  227.95 1382.45  232.02
#Mann= 3 , 0 , 0
       0     .05       0  720.01     .04       0  776.49     .07       0
Bank Sta=720.01,776.49
XS Rating Curve= 0 ,0
Exp/Cntr=0.5,0.3

Type RM Length L Ch R = 1 ,19182.20,410.59,419.23,412.79
BEGIN DESCRIPTION:
Channel bottom center lowered 1.0 ft based on bridge survey info.
END DESCRIPTION:
XS GIS Cut Line= 6
1603070.27266228715904.2911850961602777.57621066715842.212522134
1602315.90432283715769.0780598821601984.24347186715735.654873341
1601617.99495272715686.6497897951601284.97097258715653.347391799
#Sta/Elev= 30
       0  218.07  156.86  211.91  172.89  212.32  194.46  210.81  295.14  207.79
  370.27  202.61  431.21  200.71  466.64  198.58  558.77  198.93  587.12  195.26
  628.29  195.26  684.92  192.71  787.81   190.8   844.1  188.57  907.42  188.52
  935.56  187.29  949.63  186.55  956.67     185  970.74     185  984.81   187.7
 1005.91  189.57  1062.2  189.43 1114.17  192.15 1142.42  194.57 1163.61  194.89
 1276.61  209.44 1340.17  214.65 1382.54  216.28 1518.81  217.59 1804.25  217.08
#Mann= 3 , 0 , 0
       0      .1       0  935.56     .04       0  984.81      .1       0
#XS Ineff= 2 , 0
       0  866.82     223 1080.61       0  216.33
Permanent Ineff=
       F       F
Bank Sta=935.56,984.81
XS Rating Curve= 0 ,0
Exp/Cntr=0.5,0.3