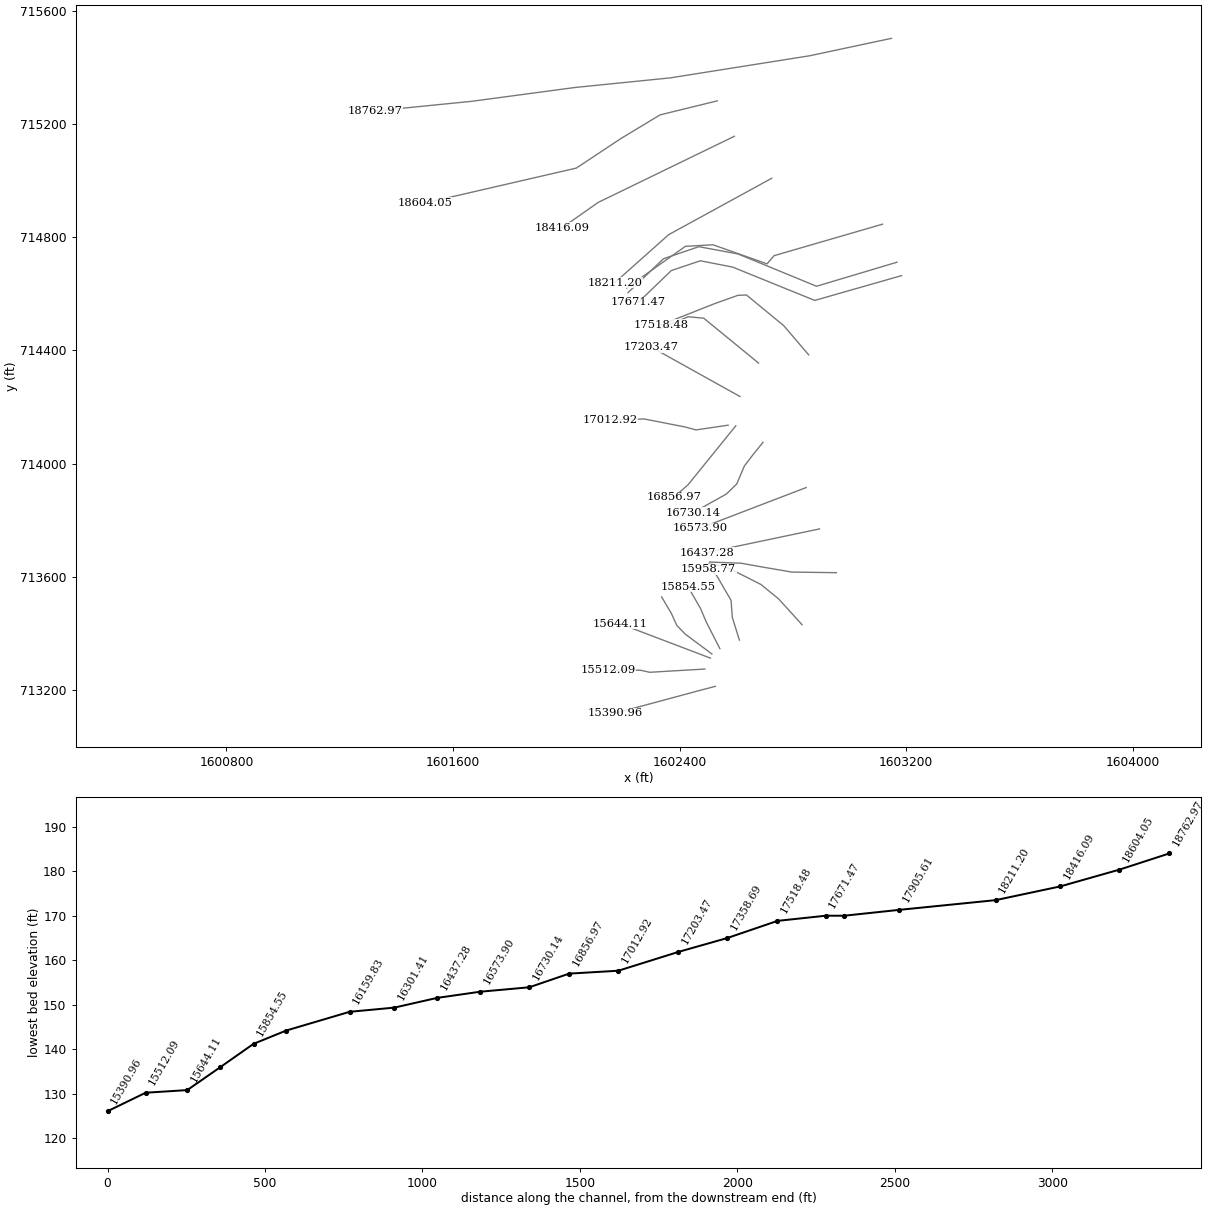
HEC-RAS study StonyRun.prj: StonyRun

--- StonyRun.g01 (geometry) --- (continued)

Type RM Length L Ch R = 2 ,19038.44,,,
BEGIN DESCRIPTION:
John F. Kennedy Memorial Highway
MDE Bridge #: CE041307FS-2
Top of road obtained from DEM.
Openings from MDE2 bridge/culvert surveys.
END DESCRIPTION:
Bridge Culvert--1,0,-1,-1, 0
Deck Dist Width WeirC Skew NumUp NumDn MinLoCord MaxHiCord MaxSubmerge Is_Ogee
94,216,2.6,0, 60, 60, , , 0.95, 0, 2,2,,
       0   28.52   49.91   85.56   99.82   142.6  156.86  170.09  220.43   249.2
  263.58  270.77  292.34  312.26  354.86  411.67  428.13  449.39  484.82  506.08
  527.34   548.6  633.67  647.83  669.07  683.22  697.38  732.77  776.02  790.09
  818.24  853.41  867.48   909.7  951.91  987.09  1029.3 1117.54 1131.66 1138.73
 1166.97  1181.1 1223.47  1237.6 1315.28 1329.41 1357.66 1392.97 1414.16 1435.35
 1456.53 1480.04  1571.5 1599.64 1662.95 1691.09 1698.12 1712.19 1747.37 1804.25
  244.08  243.07  242.99  241.86  241.64  240.44  240.28  239.73  238.79  237.99
  237.81  237.46  236.93  236.68  235.33   234.2  233.64  233.26  232.23  231.91
  231.23  230.93  228.68  228.53  227.89  227.82  227.21  226.62  225.49  225.39
  224.56  223.94   223.5  223.01  222.01  221.62  220.68  219.75  219.32  219.41
  218.84   218.8  218.12  218.11  217.14   217.2  216.73  216.48     216  215.82
  215.98  215.52  215.08   214.7  214.42  214.46  214.31  214.41     214   213.9
                                                                                
                                                                                
                                                                                
                                                                                
                                                                                
                                                                                
       0   28.52   49.91   85.56   99.82   142.6  156.86  170.09  220.43   249.2
  263.58  270.77  292.34  312.26  354.86  411.67  428.13  449.39  484.82  506.08
  527.34   548.6  633.67  647.83  669.07  683.22  697.38  732.77  776.02  790.09
  818.24  853.41  867.48   909.7  951.91  987.09  1029.3 1117.54 1131.66 1138.73
 1166.97  1181.1 1223.47  1237.6 1315.28 1329.41 1357.66 1392.97 1414.16 1435.35
 1456.53 1480.04  1571.5 1599.64 1691.09 1698.12 1712.19 1747.37 1803.65 1841.78
  244.08  243.07  242.99  241.86  241.64  240.44  240.28  239.73  238.79  237.99
  237.81  237.46  236.93  236.68  235.33   234.2  233.64  233.26  232.23  231.91
  231.23  230.93  228.68  228.53  227.89  227.82  227.21  226.62  225.49  225.39
  224.56  223.94   223.5  223.01  222.01  221.62  220.68  219.75  219.32  219.41
  218.84   218.8  218.12  218.11  217.14   217.2  216.73  216.48     216  215.82
  215.98  215.52  215.08   214.7  214.46  214.31  214.41     214   213.9     214
                                                                                
                                                                                
                                                                                
                                                                                
                                                                                
                                                                                
BR Coef=-1 , 1 , 0 ,, 0 ,,,0.8,0,0.5,0,
WSPro=,,,, 1 ,,,, 0 ,,,, 0 ,,,,-1 ,-1 ,-1 , 0 , 0 , 0 , 0 , 0
Multiple Barrel Culv=2,10,8,320,0.015,0.4,1,8,1,185,184, 2,Culvert #1  , 0 ,49.6
     959     909     968     918
Culvert Bottom n=0.015
BC Design=,, 0 ,, 0 ,,,,,,
BC Use User HTab Curves=0
BC User HTab FreeFlow(D)= 0

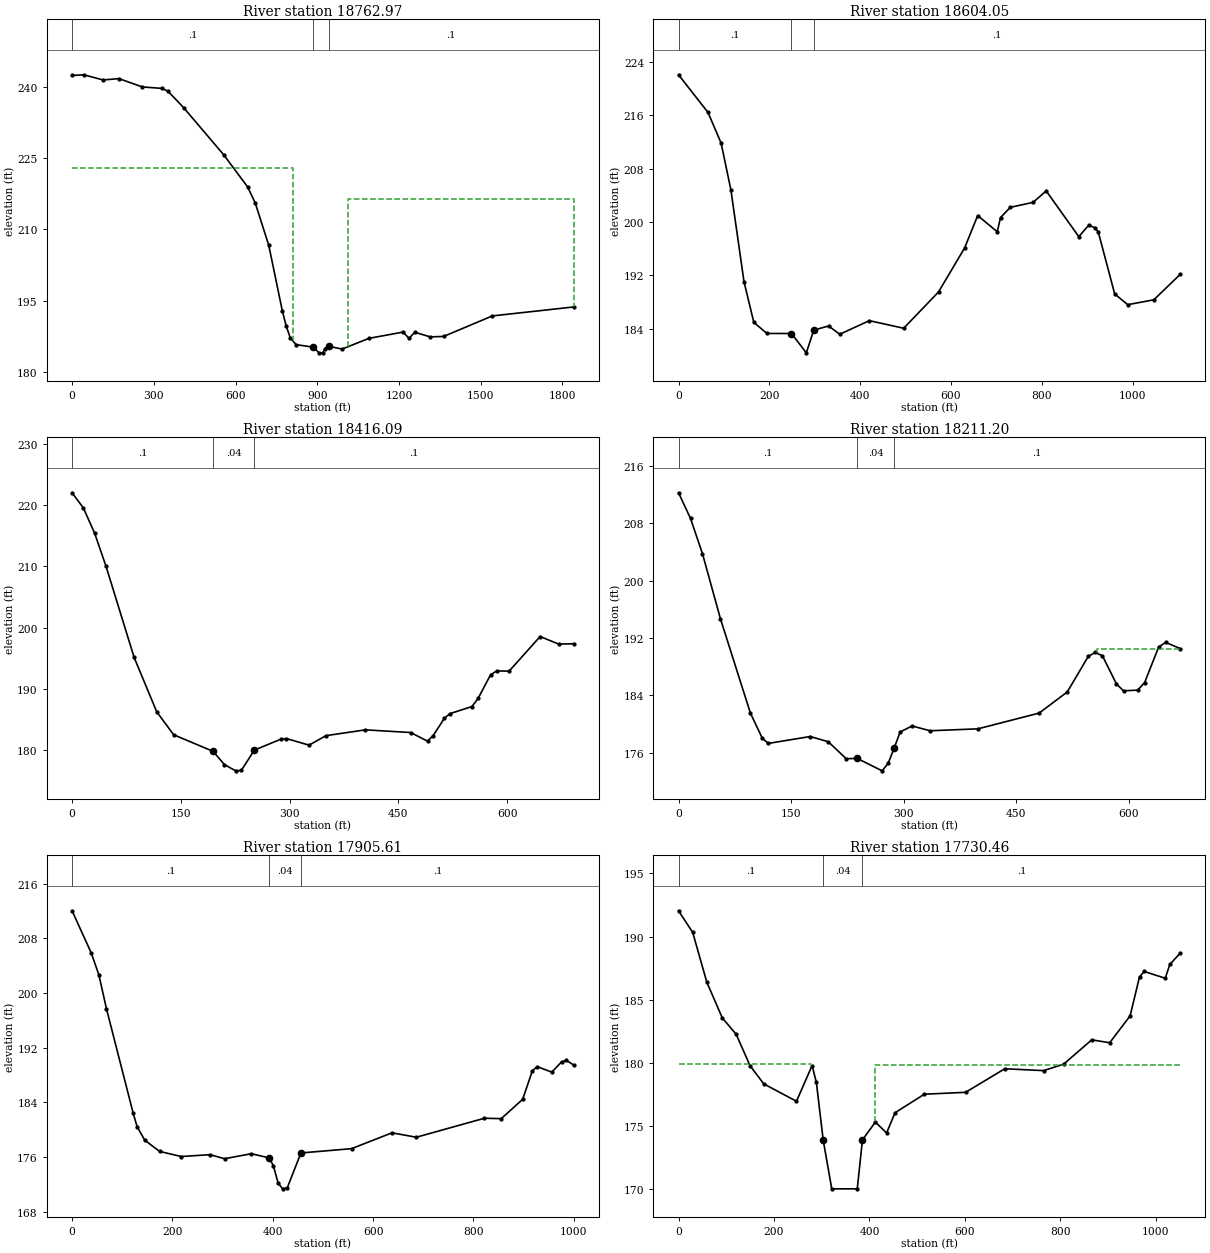
Type RM Length L Ch R = 1 ,18762.97,126.6,158.92,202.39
BEGIN DESCRIPTION:
Channel bottom center lowered 1.0 ft based on bridge survey info.
END DESCRIPTION:
XS GIS Cut Line= 6
1603148.18164398715501.7614463421602859.00762145715440.176255807
1602366.89884554715362.1403957611602031.99823283715328.390721619
1601665.59373184715279.3647672391601325.76749738 715245.38214381
#Sta/Elev= 30
       0  242.37   42.78  242.52  114.08  241.43   171.9  241.71  258.19  239.96
  331.22  239.65  352.52  239.03  409.33  235.61  556.32   225.7  644.06  218.94
  672.37  215.54  721.92  206.64  771.47   192.9  785.62   189.7  801.03  187.13
  822.13  185.73  885.71  185.19  906.56     184  920.63     184  927.66  184.89
  941.73  185.39  990.98  184.79 1089.48  187.05 1215.33  188.37 1236.52  187.04
 1257.71  188.33 1314.21  187.36 1363.64  187.45 1542.47  191.77 1841.78  193.66
#Mann= 3 , 0 , 0
       0      .1       0  885.71     .04       0  941.73      .1       0
#XS Ineff= 2 , 0
       0  811.53     223 1011.33       0  216.33
Permanent Ineff=
       F       F
Bank Sta=885.71,941.73
XS Rating Curve= 0 ,0
Exp/Cntr=0.5,0.3

Type RM Length L Ch R = 1 ,18604.05,189.34,187.96,172.29
XS GIS Cut Line= 5
  1602533.027456715280.9865266231602331.17208572715231.552558422
1602192.48234153715147.789445579 1602035.5319315715043.684291452
1601502.68910392714920.736483201
#Sta/Elev= 30
       0  222.09   64.86  216.44   93.69  211.85  115.31  204.81  144.14  191.04
  165.76  184.93  194.59  183.26  248.71  183.25  281.42  180.35  297.77  183.76
  330.49  184.38  355.02  183.14  420.24  185.18  495.84  184.04  572.55  189.49
  630.02   196.1  658.76  200.96  701.86  198.52  709.04  200.65  730.59  202.19
  780.88  202.94  809.62  204.66  881.46  197.79  903.01  199.49  917.38  199.13
  924.56  198.43  960.48  189.19  989.21  187.58 1046.69  188.31 1105.02  192.15
#Mann= 3 , 0 , 0
       0      .1       0  248.71     .04       0  297.77      .1       0
Bank Sta=248.71,297.77
XS Rating Curve= 0 ,0
Exp/Cntr=0.3,0.1

Type RM Length L Ch R = 1 ,18416.09,205.14,204.89,212.19
XS GIS Cut Line= 3
1602593.44675045715156.0284402821602112.83872609714922.590257004
 1601983.7611424714831.961315274
#Sta/Elev= 30
       0  222.02   15.56  219.55   31.13  215.41   46.69  210.06    85.6  195.11
  116.73  186.23  140.08  182.48  194.55  179.76  210.11   177.6  225.68  176.58
  233.46  176.65  251.34  179.97  287.94  181.75  295.72  181.85  326.85  180.78
  350.19  182.33  404.67  183.28  466.92  182.84  490.27  181.43  498.05  182.35
  513.61   185.2   521.4  185.94  551.41  187.08  559.96  188.42  577.07  192.26
  585.62  192.91  602.73  192.87  645.49  198.53  671.15  197.29  692.02  197.35
#Mann= 3 , 0 , 0
       0      .1       0  194.55     .04       0  251.34      .1       0
Bank Sta=194.55,251.34
XS Rating Curve= 0 ,0
Exp/Cntr=0.3,0.1

Type RM Length L Ch R = 1 ,18211.20,325.26,305.59,252.74
XS GIS Cut Line= 3
1602725.27066574715007.7265356031602361.38173299714808.617496923
1602171.88485481 714639.71810551
#Sta/Elev= 30
       0  212.22   15.96  208.65   31.92  203.73   55.86  194.67   95.75  181.54
  111.71  178.02  119.69  177.32  175.55  178.28  199.48  177.55  223.42  175.19
   238.1  175.23   271.3   173.5  279.28  174.54  287.26  176.64  295.24  178.91
   311.2  179.75  335.13  179.08  398.97  179.35  480.44  181.54  517.95  184.48
  546.08  189.45  555.45  189.99  564.83  189.52  583.59  185.59  592.96  184.64
  611.72  184.74  621.09  185.79  639.85  190.76  649.22  191.38  668.64  190.52
#Mann= 3 , 0 , 0
       0      .1       0   238.1     .04       0  287.26      .1       0
#XS Ineff= 1 ,-1
  557.49  668.64190.5204
Permanent Ineff=
       F
Bank Sta=238.1,287.26
XS Rating Curve= 0 ,0
Exp/Cntr=0.3,0.1

Type RM Length L Ch R = 1 ,17905.61,148.54,175.15,114.5
XS GIS Cut Line= 6
1603116.62291421714845.6929730921602733.50966047714734.466544598
1602708.79267634714705.630063131 1602517.9226324714772.915186554
1602420.42786172714767.4225234091602213.07982831714620.493784517
#Sta/Elev= 30
       0  212.01    38.1  205.86   53.34  202.65   68.58  197.67  121.91  182.36
  129.53  180.44  144.77  178.45  174.33   176.8  217.52  176.05  275.11  176.32
  303.91  175.73  357.57  176.46  392.77  175.85  401.35   174.7  410.57  172.19
  419.79  171.32  429.01  171.48  456.21  176.57  557.15   177.2  637.75  179.52
  686.16  178.87  821.92  181.65  855.45  181.59  898.19  184.42  917.56   188.6
  927.25  189.21  956.31  188.39  975.68   189.9  985.37  190.11 1000.24  189.43
#Mann= 3 , 0 , 0
       0      .1       0  392.77     .04       0  456.21      .1       0
Bank Sta=392.77,456.21
XS Rating Curve= 0 ,0
Exp/Cntr=0.5,0.3

Type RM Length L Ch R = 1 ,17730.46,50.61,58.99,51.69
BEGIN DESCRIPTION:
Channel bottom center lowered approx. 2 ft based on bridge survey info.
END DESCRIPTION:
XS GIS Cut Line= 6
1603167.48962133714711.4029859751602883.40968336714626.514639229
1602606.31955045714740.5840727541602468.04294449714766.220114842
1602343.12396233714723.622907028  1602217.943546714603.916452616
#Sta/Elev= 30
       0  192.04   29.63  190.33   59.26  186.38   91.61  183.55  120.72  182.25
  149.82  179.76  178.58  178.32  247.03  176.94  279.75  179.77  288.73  178.43
  303.07  173.85  320.94     170  374.35     170  385.24  173.88  412.24  175.29
  435.88  174.43  453.41  176.03   514.9   177.5  601.24  177.65  683.39  179.52
  764.61  179.37  806.54  179.88   865.5  181.81  903.14  181.58  945.87  183.71
  965.59   186.8  975.45  187.23  1019.5  186.69 1029.06  187.79 1051.07  188.69
#Mann= 3 , 0 , 0
       0      .1       0  303.07     .04       0  385.24      .1       0
#XS Ineff= 2 , 0
       0     278  179.87     412       0  179.81
Permanent Ineff=
       F       F
Bank Sta=303.07,385.24
XS Rating Curve= 0 ,0
Exp/Cntr=0.5,0.3

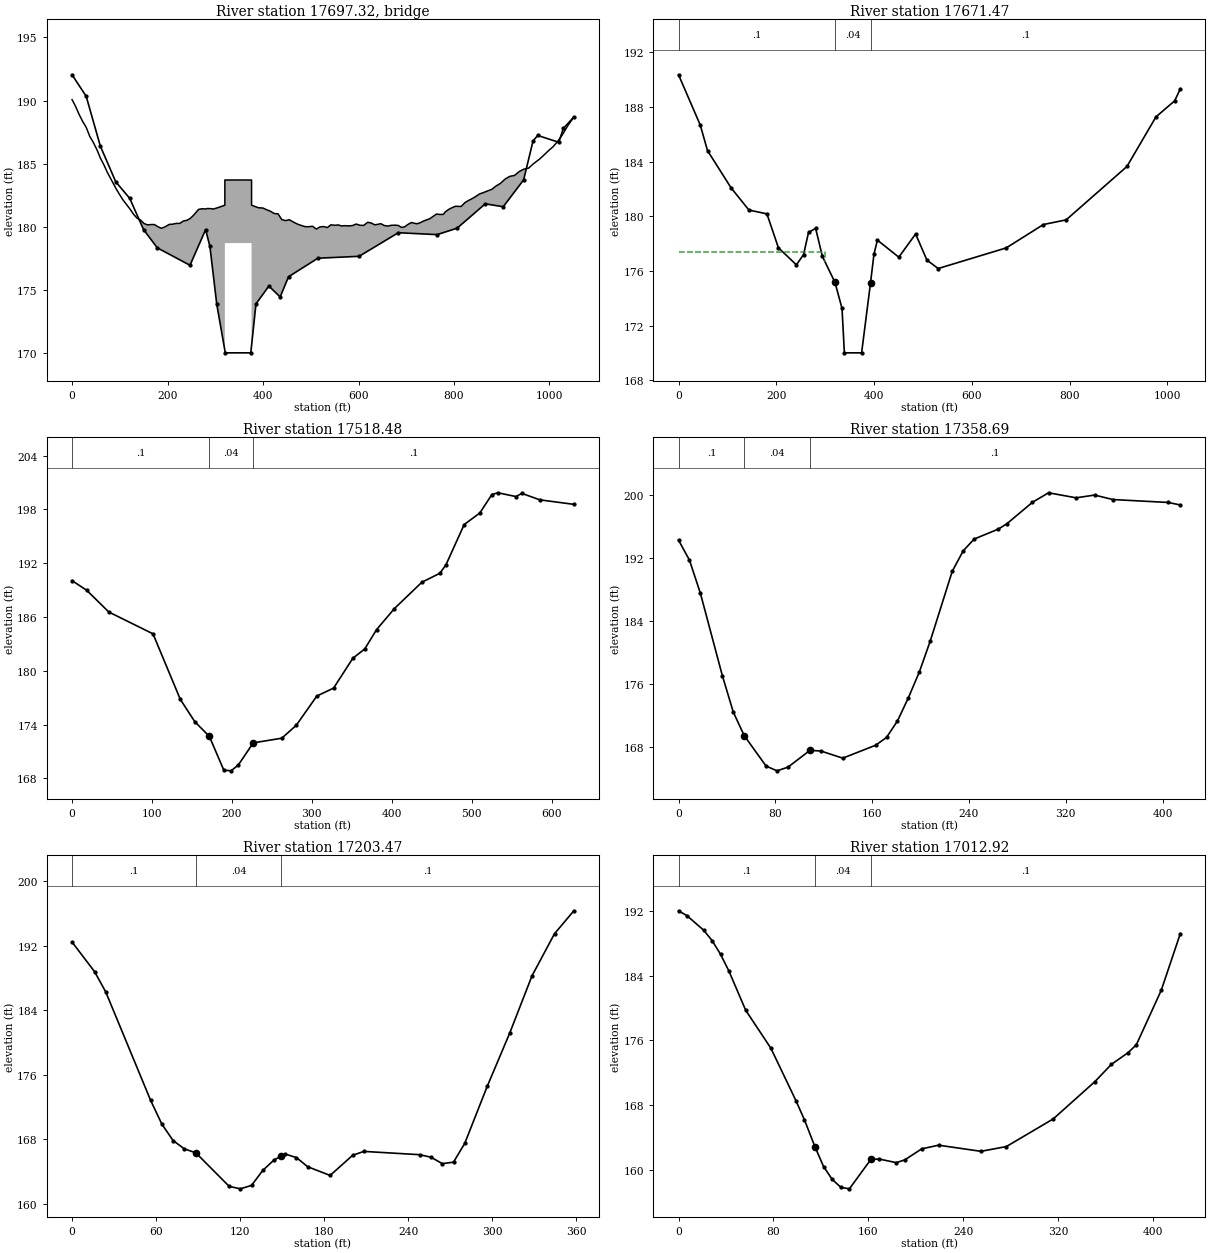
Type RM Length L Ch R = 3 ,17697.32,,,
BEGIN DESCRIPTION:
Bethel Church Road, MDE Bridge #: CE041007PF-7
Top of road obtained from DEM.
Openings from MDE2 bridge/culvert surveys.
END DESCRIPTION:
Bridge Culvert--1,0,-1,-1, 0
Deck Dist Width WeirC Skew NumUp NumDn MinLoCord MaxHiCord MaxSubmerge Is_Ogee
14,31,2.6,0, 130, 127, , , 0.95, 0, 2,2,,
       0    7.41   14.82   22.22   29.63   37.04   44.45   51.85   59.26   66.67
   74.08   85.05   92.33    99.6  106.88  114.15  121.43  128.71  135.98  143.26
  150.53  157.72  165.05  172.38  179.71  187.03  194.36   203.6  210.96  218.31
  225.66  233.01  240.37  247.72  255.07  264.99  272.28  279.58  283.48   290.5
  296.04  303.04     320     320     376     376  390.61  399.63   407.2  415.67
  423.56  431.44  439.32   447.2  455.08  465.38  473.06  480.75  488.43  496.12
  503.81  511.49  519.18  526.86  534.55  542.24  549.92  557.61  563.99   571.8
  579.61  587.43  595.24  603.05  610.86  619.22  626.57  633.92  641.27  646.61
  654.03  661.44  668.72  675.91  683.09  690.27  696.57  703.66  710.74  717.83
  722.99  730.01  737.03  744.05  749.16  756.22  763.27  770.33  777.39  781.78
  788.95  796.13   803.3  810.48  814.94  822.69  830.43  836.88  845.07  853.26
  861.45  871.06  879.66  888.27  896.87  906.97  916.83  926.69  936.55  946.41
  956.26  966.12  978.99  988.54  998.09 1007.64  1017.2 1026.75  1038.8 1051.07
  190.07  189.53  188.89  188.34  187.87  187.16  186.68  186.12  185.44   184.9
  184.29  183.52     183  182.54  182.11  181.75  181.39  180.99  180.68  180.53
  180.26  180.14  180.17  180.17     180  179.87  179.98  180.18   180.2  180.26
  180.26  180.45   180.5  180.66  180.93  181.37  181.42   181.4  181.44  181.43
   181.4  181.48   181.7   183.7   183.7   181.7   181.5  181.48  181.35  181.22
  181.04  181.02  180.56  180.48  180.55  180.33  180.19  180.09     180     180
  180.03  179.81  179.98  180.01  179.93  180.15  180.11  180.14  180.06  180.08
  180.06  180.09  180.21  180.11   180.1  180.35  180.29  180.15  180.19  180.24
  180.09  180.05  180.11  180.12   180.1  179.94  179.99  180.18  180.33  180.26
  180.23  180.33  180.46  180.56  180.63  180.81     181  180.97  180.97  181.17
  181.37  181.51  181.62  181.61   181.6   181.9  182.08   182.2  182.38  182.59
   182.7  182.84  182.97  183.23  183.42  183.77  183.99  184.06  184.37  184.56
  184.64  184.98  185.35  185.68  186.03  186.34  186.76  187.27  188.03  188.69
                                                                                
                                                                                
                                                                                
                                                                                
                           178.7   178.7
                                                                                
                                                                                
                                                                                
                                                                                
                                                                                
                                                                                
                                                                                
                                                                                
       0    7.41   14.82   22.22   29.63   37.04   44.45   51.85   59.26   66.67
   74.08   85.05   92.33    99.6  106.88  114.15  121.43  128.71  135.98  143.26
  150.53  157.72  165.05  172.38  179.71  187.03  194.36   203.6  210.96  218.31
  225.66  233.01  240.37  247.72  255.07  264.99  272.28  279.58  283.48   290.5
  296.04  303.04     330     330     386     386  399.63   407.2  415.67  423.56
  431.44  439.32   447.2  455.08  465.38  473.06  480.75  488.43  496.12  503.81
  511.49  519.18  526.86  534.55  542.24  549.92  557.61  563.99   571.8  579.61
  587.43  595.24  603.05  610.86  619.22  626.57  633.92  641.27  646.61  654.03
  661.44  668.72  675.91  683.09  690.27  696.57  703.66  710.74  717.83  722.99
  730.01  737.03  744.05  749.16  756.22  763.27  770.33  777.39  781.78  788.95
  796.13   803.3  810.48  814.94  822.69  830.43  836.88  845.07  853.26  861.45
  871.06  879.66  888.27  896.87  906.97  916.83  926.69  936.55  946.41  956.26
  966.12  978.99  988.54  998.09 1007.64  1017.2 1026.47
  190.07  189.53  188.89  188.34  187.87  187.16  186.68  186.12  185.44   184.9
  184.29  183.52     183  182.54  182.11  181.75  181.39  180.99  180.68  180.53
  180.26  180.14  180.17  180.17     180  179.87  179.98  180.18   180.2  180.26
  180.26  180.45   180.5  180.66  180.93  181.37  181.42   181.4  181.44  181.43
   181.4  181.48   181.7   183.7   183.7   181.7  181.48  181.35  181.22  181.04
  181.02  180.56  180.48  180.55  180.33  180.19  180.09     180     180  180.03
  179.81  179.98  180.01  179.93  180.15  180.11  180.14  180.06  180.08  180.06
  180.09  180.21  180.11   180.1  180.35  180.29  180.15  180.19  180.24  180.09
  180.05  180.11  180.12   180.1  179.94  179.99  180.18  180.33  180.26  180.23
  180.33  180.46  180.56  180.63  180.81     181  180.97  180.97  181.17  181.37
  181.51  181.62  181.61   181.6   181.9  182.08   182.2  182.38  182.59   182.7
  182.84  182.97  183.23  183.42  183.77  183.99  184.06  184.37  184.56  184.64
  184.98  185.35  185.68  186.03  186.34  186.76  187.27
                                                                                
                                                                                
                                                                                
                                                                                
                           178.7   178.7
                                                                                
                                                                                
                                                                                
                                                                                
                                                                                
                                                                                
                                                                                
                                                        
BR Coef=-1 , 0 , 0 ,, 0 ,,,0.8,0,,0,
WSPro=,,,, 1 ,,,, 0 ,,,, 0 ,,,,-1 ,-1 ,-1 , 0 , 0 , 0 , 0 , 0
BC Design=,, 0 ,, 0 ,,,,,,
BC Use User HTab Curves=0
BC User HTab FreeFlow(D)= 0

Type RM Length L Ch R = 1 ,17671.47,158.04,152.99,85.36
BEGIN DESCRIPTION:
Channel bottom center lowered approx. 2 ft based on bridge survey info.
END DESCRIPTION:
XS GIS Cut Line= 6
1603183.84846455714664.1548299491602877.25440213714576.514639229
1602587.49732858714694.1095647661602473.23891257714716.476047471
1602370.66766831 714681.851802261602254.58322063714569.893897638
#Sta/Elev= 30
       0  190.35   44.45  186.67   59.26   184.8  107.59  182.07  143.97  180.45
  180.83  180.17   204.3  177.69  241.06  176.44  255.77  177.19  265.86  178.81
  280.45  179.11  294.23  177.06     320  175.16  334.43  173.25  339.25     170
   374.5     170  392.75  175.13  399.78  177.22  406.81  178.25  450.58     177
  484.98   178.7  508.04  176.79  531.09  176.17  670.41  177.68  746.31  179.39
  792.85  179.73  917.31  183.64  976.63  187.27 1014.84  188.44 1026.47  189.32
#Mann= 3 , 0 , 0
       0      .1       0     320     .04       0  392.75      .1       0
#XS Ineff= 2 , 0
       0     300   177.4     407       0   177.4
Permanent Ineff=
       F       F
Bank Sta=320,392.75
XS Rating Curve= 0 ,0
Exp/Cntr=0.5,0.3

Type RM Length L Ch R = 1 ,17518.48,161.6,159.79,159.49
XS GIS Cut Line= 6
1602855.72141519714384.3092696671602767.83880502714487.296703473
1602636.01488979714595.7768004241602605.80524251714594.403634623
1602524.78846128714565.5671531711602333.91841732 714490.04303506
#Sta/Elev= 30
       0  190.05    18.4  188.97   46.01  186.55  101.22  184.12  135.39  176.81
  153.52  174.32  171.65  172.69  189.78  168.92  198.85  168.84  207.91  169.49
  226.57171.9583   262.3  172.48  280.43  173.92  306.11  177.18  327.13  178.07
  351.21   181.4  366.07  182.43  380.93   184.6  403.22  186.94  437.47  189.87
  460.15  190.88  467.71  191.83  490.39   196.3  510.04   197.6  525.06  199.65
  532.57  199.85   555.1  199.43  562.61  199.78  585.15  199.06  627.62  198.56
#Mann= 3 , 0 , 0
       0      .1       0  171.65     .04       0  226.57      .1       0
Bank Sta=171.65,226.57
XS Rating Curve= 0 ,0
Exp/Cntr=0.3,0.1

Type RM Length L Ch R = 1 ,17358.69,149.04,155.22,172
XS GIS Cut Line= 4
1602678.93014501714355.2408160871602485.28168963714513.771675929
1602430.04002222714518.8795165121602329.79891993714476.311377198
#Sta/Elev= 30
       0  194.28    9.05  191.74   18.09  187.52   36.19  177.08   45.23  172.45
   54.28  169.45   72.37  165.58   81.42  164.98   90.47  165.45  108.56  167.58
   117.6   167.5   135.7  166.59  162.84  168.23  171.88  169.22  180.93  171.32
  189.98  174.28  199.02  177.55  208.07   181.5  226.16  190.32  235.21  192.92
  244.26  194.42  264.32  195.69  271.35  196.37  292.44  199.09  305.74   200.3
  328.56  199.66  343.77  200.01  358.98  199.44  404.61  199.07  414.65  198.75
#Mann= 3 , 0 , 0
       0      .1       0   54.28     .04       0  108.56      .1       0
Bank Sta=54.28,108.56
XS Rating Curve= 0 ,0
Exp/Cntr=0.3,0.1

Type RM Length L Ch R = 1 ,17203.47,178.47,190.55,218.05
XS GIS Cut Line= 2
1602613.18755659714237.3215702471602300.12761194 714411.59160611
#Sta/Elev= 30
       0  192.44   16.02  188.79   24.03  186.27   56.08  172.83   64.09  169.89
    72.1  167.85   80.11  166.82   88.39  166.32  112.16  162.17  120.17  161.86
  128.18  162.29   136.2  164.15  144.21  165.44  149.12  165.89  152.22  166.17
  160.23  165.73  168.24   164.6  184.26  163.52  200.29  166.01   208.3   166.5
  248.36  166.09  256.37  165.77  264.38  164.98  272.39  165.17   280.4   167.5
  296.43  174.56  312.45  181.14  328.47  188.28  344.49  193.48   358.3  196.32
#Mann= 3 , 0 , 0
       0      .1       0   88.39     .04       0  149.12      .1       0
Bank Sta=88.39,149.12
XS Rating Curve= 0 ,0
Exp/Cntr=0.3,0.1

Type RM Length L Ch R = 1 ,17012.92,105.04,155.95,199.48
XS GIS Cut Line= 5
1602571.44623068714136.0988548251602457.70111744714119.402324423
1602419.09039094714129.8376559321602275.08281636714158.013050929
1602154.03297114714154.882451504
#Sta/Elev= 30
       0  192.04    7.08  191.44   21.23  189.63    28.3  188.35   35.38  186.66
   42.45  184.58    56.6  179.73   77.83  175.03   99.05  168.51  106.13  166.16
  114.96  162.84  122.22  160.39  129.47  158.81  136.72  157.83  143.97  157.64
  162.09  161.29  169.23  161.32  183.49  160.88  190.62  161.22  204.89  162.59
  219.15  163.04  254.82  162.28  276.22  162.87   315.7  166.29  350.71  170.89
  364.72  173.04  378.72  174.48  385.73  175.46  406.73  182.21  422.79  189.22
#Mann= 3 , 0 , 0
       0      .1       0  114.96     .04       0  162.09      .1       0
Bank Sta=114.96,162.09
XS Rating Curve= 0 ,0
Exp/Cntr=0.3,0.1

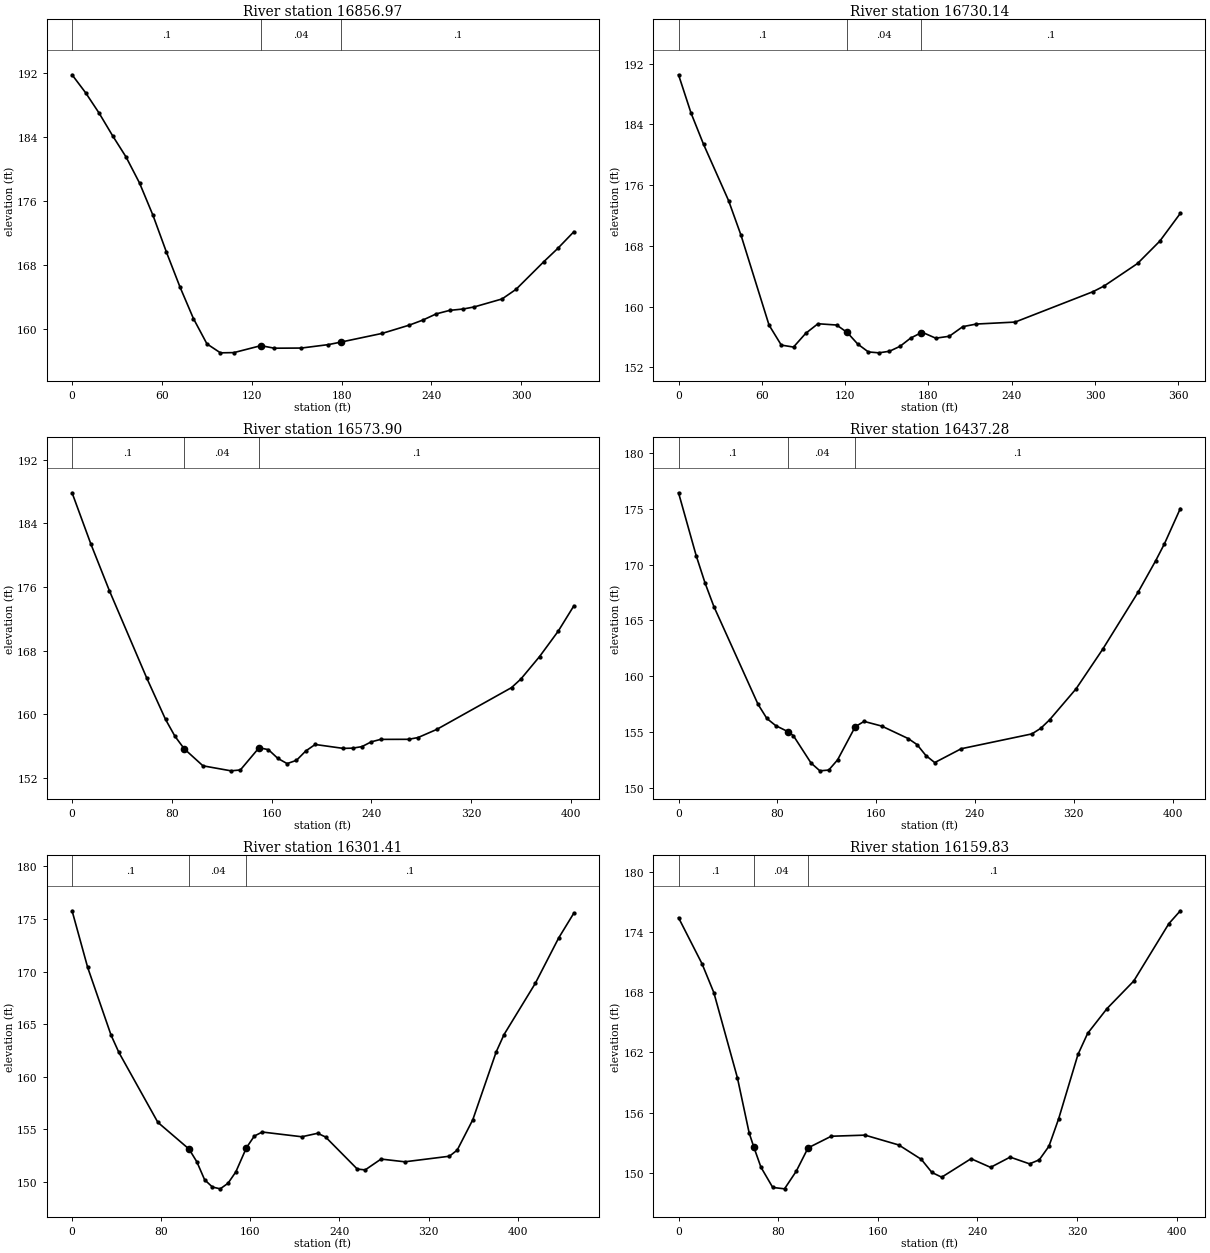
Type RM Length L Ch R = 1 ,16856.97,114.46,126.83,125.92
XS GIS Cut Line= 3
1602598.57809253714134.0117885171602429.52572244713925.305158749
1602379.43613128713881.476766497
#Sta/Elev= 30
       0  191.82    9.01  189.58   18.02  187.03   27.02   184.2   36.03  181.53
   45.04  178.27   54.05  174.21   63.06  169.59   72.07  165.24   81.07  161.28
   90.08  158.11   99.09  156.99   108.1  157.02  126.12  157.89  135.12  157.57
  153.14  157.59  171.16  158.02  179.64  158.34  207.19  159.43  225.21  160.46
  234.22  161.09  243.22  161.87  252.23  162.31  261.24  162.48  268.58  162.74
  287.19  163.74  296.49  164.94  315.09  168.41  324.39  170.07  335.14  172.16
#Mann= 3 , 0 , 0
       0      .1       0  126.12     .04       0  179.64      .1       0
Bank Sta=126.12,179.64
XS Rating Curve= 0 ,0
Exp/Cntr=0.3,0.1

Type RM Length L Ch R = 1 ,16730.14,180.73,156.24,93.35
XS GIS Cut Line= 6
1602694.58314222714075.573932186 1602659.1030152714031.745539948
1602628.84055386713992.091280282  1602601.708692713928.435758203
1602565.18503177713892.9556311371602447.26578598713827.213042751
#Sta/Elev= 30
       0  190.52    9.01  185.48   18.01  181.37   36.02  173.97   45.03  169.38
   65.19  157.57      74  154.94   82.81  154.68   91.61  156.49  100.42  157.75
  113.88  157.58  121.49   156.6   129.1  155.07  136.71  154.04  144.32  153.92
  151.93  154.13  159.54  154.78  167.15  155.86  174.37  156.53  175.47  156.63
  185.23  155.85  194.99   156.1  204.75  157.37   214.5  157.71  242.42  157.97
  298.52  161.97  306.53  162.72  330.58  165.68   346.6  168.62   361.4  172.28
#Mann= 3 , 0 , 0
       0      .1       0  121.49     .04       0  174.37      .1       0
Bank Sta=121.49,174.37
XS Rating Curve= 0 ,0
Exp/Cntr=0.3,0.1

Type RM Length L Ch R = 1 ,16573.90,141.35,136.62,124.68
XS GIS Cut Line= 2
1602846.93898197713915.9133604171602471.26704836713771.905785874
#Sta/Elev= 30
       0  187.84   14.99  181.44   29.99  175.52   59.97  164.54   74.97  159.37
   82.46  157.27   89.96  155.68  104.95  153.55  127.44  152.92  134.94  153.03
  149.93  155.82  157.43  155.58  164.93  154.49  172.42  153.83  179.92  154.24
  187.42  155.42  194.91  156.23   217.4  155.74   224.9  155.77   232.4  155.96
  239.89  156.56  247.39  156.87  269.88  156.88  277.38   157.1  292.37  158.12
  352.34  163.37  359.84  164.45  374.83  167.27  389.83  170.47  402.33  173.64
#Mann= 3 , 0 , 0
       0      .1       0   89.96     .04       0  149.93      .1       0
Bank Sta=89.96,149.93
XS Rating Curve= 0 ,0
Exp/Cntr=0.3,0.1

Type RM Length L Ch R = 1 ,16437.28,145.06,135.88,96.48
XS GIS Cut Line= 2
1602893.89797364713769.8187195661602496.31184395713686.336067662
#Sta/Elev= 30
       0  176.44   14.31   170.8   21.46  168.36   28.61  166.25   64.37  157.49
   71.53  156.22   78.68  155.58   88.44  155.05   92.98  154.68  107.29  152.23
  114.44  151.53   121.6   151.6  128.75  152.51  143.05  155.48  150.21  155.96
  164.51  155.54  185.97  154.42  193.12  153.88  200.27   152.9  207.43  152.27
  228.88  153.51  286.11  154.84  293.26  155.34  300.41   156.1  321.87  158.88
  343.33  162.41  371.94  167.51  386.24  170.34   393.4  171.87  406.26  175.03
#Mann= 3 , 0 , 0
       0      .1       0   88.44     .04       0  143.05      .1       0
Bank Sta=88.44,143.05
XS Rating Curve= 0 ,0
Exp/Cntr=0.3,0.1

Type RM Length L Ch R = 1 ,16301.41,160.95,141.57,64.43
XS GIS Cut Line= 5
1602953.37936316713615.375813544 1602796.8493908713617.462879851
1602698.75727484713634.1594102231602617.36168921713648.768874317
1602505.70364231713652.943006903
#Sta/Elev= 30
       0  175.78      14   170.4      35  163.96      42  162.32   77.01  155.67
  105.01  153.13  112.01  151.92  119.01  150.21  126.01  149.52  133.01  149.35
  140.01  149.88  147.01  150.96  156.54  153.26  163.64  154.37  170.75  154.75
  206.25   154.3  220.45  154.63  227.55  154.28  256.05  151.23  263.16  151.15
  277.38  152.18  298.72  151.92  338.74  152.45  345.75  153.03  359.76  155.92
  380.77  162.37  387.78  164.01   415.8  168.87  436.81  173.19  450.48  175.56
#Mann= 3 , 0 , 0
       0      .1       0  105.01     .04       0  156.54      .1       0
Bank Sta=105.01,156.54
XS Rating Curve= 0 ,0
Exp/Cntr=0.3,0.1

Type RM Length L Ch R = 1 ,16159.83,212.7,201.07,125.7
XS GIS Cut Line= 6
 1602832.3295179713431.7139793341602749.89039913713522.501363292
1602687.27841018713573.6344875841602617.36168921713609.114614651
1602554.74970026713639.3770759551602503.61657597713645.638274848
#Sta/Elev= 30
       0  175.42   18.91  170.82   28.37  167.95   47.28  159.47   56.73  153.97
   60.48  152.56   66.19  150.56   75.64  148.55    85.1  148.41   94.55  150.17
  104.01  152.49  122.63  153.65  149.74  153.76  176.86  152.78  194.93  151.35
  203.47  150.04  211.32  149.57  234.87  151.41  250.57  150.55  266.27  151.57
  281.87   150.9  289.65   151.3  297.42  152.65   305.2  155.38  320.75   161.8
  328.52   163.9  344.07  166.37  365.52  169.11  393.73  174.83  402.93  176.11
#Mann= 3 , 0 , 0
       0      .1       0   60.48     .04       0  104.01      .1       0
Bank Sta=60.48,104.01
XS Rating Curve= 0 ,0
Exp/Cntr=0.3,0.1

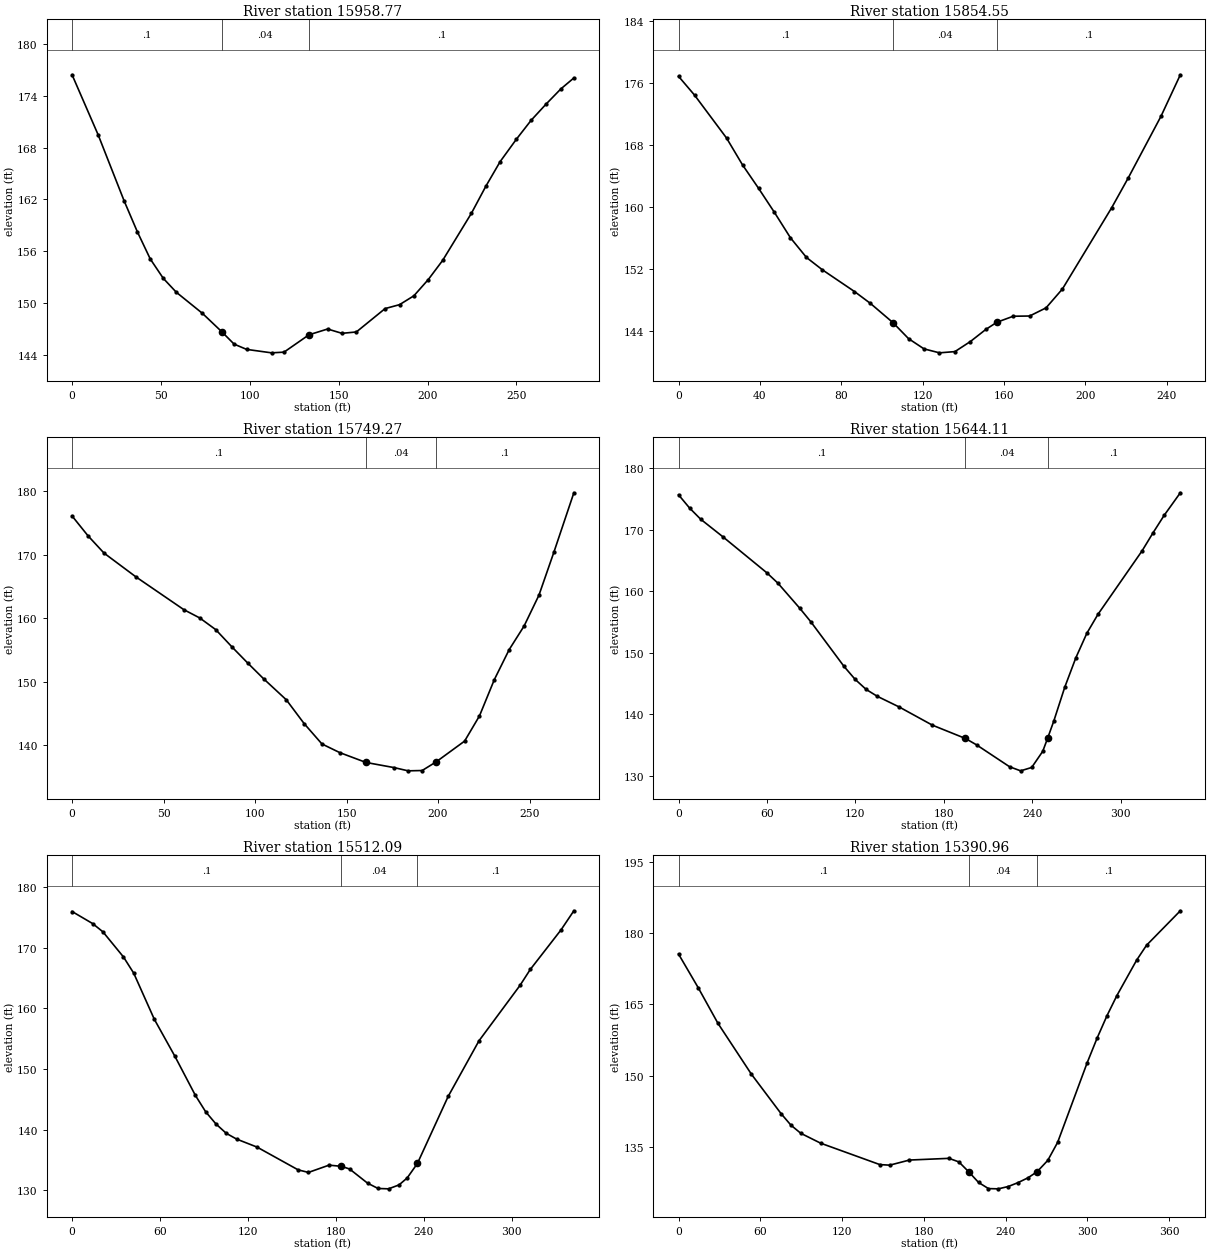
Type RM Length L Ch R = 1 ,15958.77,92.77,104.22,110.77
XS GIS Cut Line= 5
1602611.10049032713377.4502555881602586.05569474713457.802308053
1602581.88156219713517.2836975461602528.66137156713609.114614651
1602501.52950969713626.854678169
#Sta/Elev= 30
       0  176.43   14.66  169.48   29.33   161.8   36.66  158.27   43.99  155.09
   51.33  152.84   58.66  151.23   73.32  148.79   84.16  146.67   91.18  145.22
    98.2  144.61  112.23  144.21  119.25  144.29  133.29   146.3  143.79  146.97
  151.88  146.47  159.97  146.63  176.15  149.34  184.25  149.79  192.34  150.82
  200.43   152.7  208.52  154.92   224.7  160.38  232.79   163.5  240.88  166.37
  249.93  168.94  258.29  171.15  266.66  173.02  275.02  174.79  282.35  176.06
#Mann= 3 , 0 , 0
       0      .1       0   84.16     .04       0  133.29      .1       0
Bank Sta=84.16,133.29
XS Rating Curve= 0 ,0
Exp/Cntr=0.3,0.1

Type RM Length L Ch R = 1 ,15854.55,93.86,105.28,101.19
XS GIS Cut Line= 4
1602542.22730248713347.1877942831602494.22477767713441.105777696
1602474.39764784713488.0647693721602429.52572244 713566.32975553
#Sta/Elev= 27
       0  176.87    7.86  174.45   23.58  168.92   31.45  165.45   39.31  162.44
   47.17  159.31   55.03  156.04   62.89  153.51   70.75  151.91   86.47  149.12
   94.34  147.58  105.47  145.09  113.07  143.04  120.67  141.72  128.27  141.21
  135.87  141.37  143.47  142.67  151.06  144.23  156.45  145.15  164.52  145.93
  172.59  145.96  180.65  147.01  188.72  149.45  212.93  159.93     221  163.74
  237.14  171.71  246.66  177.07
#Mann= 3 , 0 , 0
       0      .1       0  105.47     .04       0  156.45      .1       0
Bank Sta=105.47,156.45
XS Rating Curve= 0 ,0
Exp/Cntr=0.3,0.1

Type RM Length L Ch R = 1 ,15749.27,68.08,105.16,122.39
XS GIS Cut Line= 5
1602514.05190748713328.4041976031602420.13392407713398.320918575
1602389.87146279713429.6269130561602371.08786611   713471.368239
1602336.65127216713529.806095332
#Sta/Elev= 27
       0   176.1    8.73  172.97   17.45  170.26   34.91  166.51   61.09  161.35
   69.81  160.04   78.54   158.2   87.27  155.52   95.99  152.95  104.72  150.46
  117.09  147.16  126.82  143.42  136.56  140.21  146.29  138.85  160.63   137.3
  175.98  136.49  183.66  135.98  191.33  136.03  199.01   137.4  214.52  140.66
  222.65  144.63  230.77  150.34   238.9  155.07  247.02  158.77  255.15  163.63
  263.27  170.36  274.23  179.75
#Mann= 3 , 0 , 0
       0      .1       0  160.63     .04       0  199.01      .1       0
Bank Sta=160.63,199.01
XS Rating Curve= 0 ,0
Exp/Cntr=0.3,0.1

Type RM Length L Ch R = 1 ,15644.11,106.82,132.02,135.47
XS GIS Cut Line= 2
1602508.83424173713313.7947335091602190.55663133713434.844578773
#Sta/Elev= 30
       0  175.71    7.49  173.56   14.98  171.75   29.96  168.91   59.91  163.03
    67.4  161.35   82.38  157.23   89.87  155.03  112.34  147.79  119.83   145.7
  127.32  144.06  134.81  142.95  149.78   141.2  172.25  138.25  194.72  136.08
  202.21  135.05  224.68  131.48  232.16  130.82  239.65  131.37  247.14  133.99
  250.43   136.1  254.63   138.9  262.12  144.44  269.61   149.2   277.1   153.2
  284.59  156.26  314.55  166.59  322.03  169.54  329.52  172.36  340.52  176.04
#Mann= 3 , 0 , 0
       0      .1       0  194.72     .04       0  250.43      .1       0
Bank Sta=194.72,250.43
XS Rating Curve= 0 ,0
Exp/Cntr=0.3,0.1

Type RM Length L Ch R = 1 ,15512.09,97.66,121.13,130.68
XS GIS Cut Line= 4
1602489.00711191713275.1840070041602294.90994625713263.705142379
1602261.51688544713271.0098744181602147.77177225 713272.05340758
#Sta/Elev= 30
       0  176.01   14.02  174.02   21.04  172.66   35.06  168.51   42.07  165.83
    56.1  158.23   70.12  152.13   84.15  145.65   91.16  142.95   98.17  140.94
  105.18   139.4   112.2  138.45  126.22  137.12  154.27  133.36  161.28  132.94
  175.31  134.14  183.65  133.95  189.33  133.51   201.6  131.17  208.77  130.29
  215.93  130.23   223.1  130.88  228.62  132.02  235.62  134.42  256.62  145.49
  277.62  154.66  305.62  163.81  312.62  166.44  333.62  172.98  342.37  176.13
#Mann= 3 , 0 , 0
       0      .1       0  183.65     .04       0  235.62      .1       0
Bank Sta=183.65,235.62
XS Rating Curve= 0 ,0
Exp/Cntr=0.3,0.1

Type RM Length L Ch R = 1 ,15390.96,116.04,118.03,115.64
XS GIS Cut Line= 3
1602526.40532635713214.1694815611602474.67513262713200.595490083
 1602170.7295015713118.654034674
#Sta/Elev= 30
       0  175.65   14.47  168.53   28.95  161.01   53.48  150.28   75.23  141.96
   82.48  139.52   89.73   137.8  104.23  135.72  147.73  131.19  154.98  131.07
  169.48  132.15  198.48  132.51  205.73  131.76  212.98  129.67  220.23  127.41
  227.48  126.12  234.73  126.07  241.98  126.56  249.23  127.39  256.48   128.4
  263.14  129.68  270.98  132.07  278.23  135.88  299.98  152.75  307.23  157.92
  314.48  162.65  321.73  166.89  336.23  174.37  343.48  177.51  368.28  184.79
#Mann= 3 , 0 , 0
       0      .1       0  212.98     .04       0  263.14      .1       0
Bank Sta=212.98,263.14
XS Rating Curve= 0 ,0
Exp/Cntr=0.3,0.1