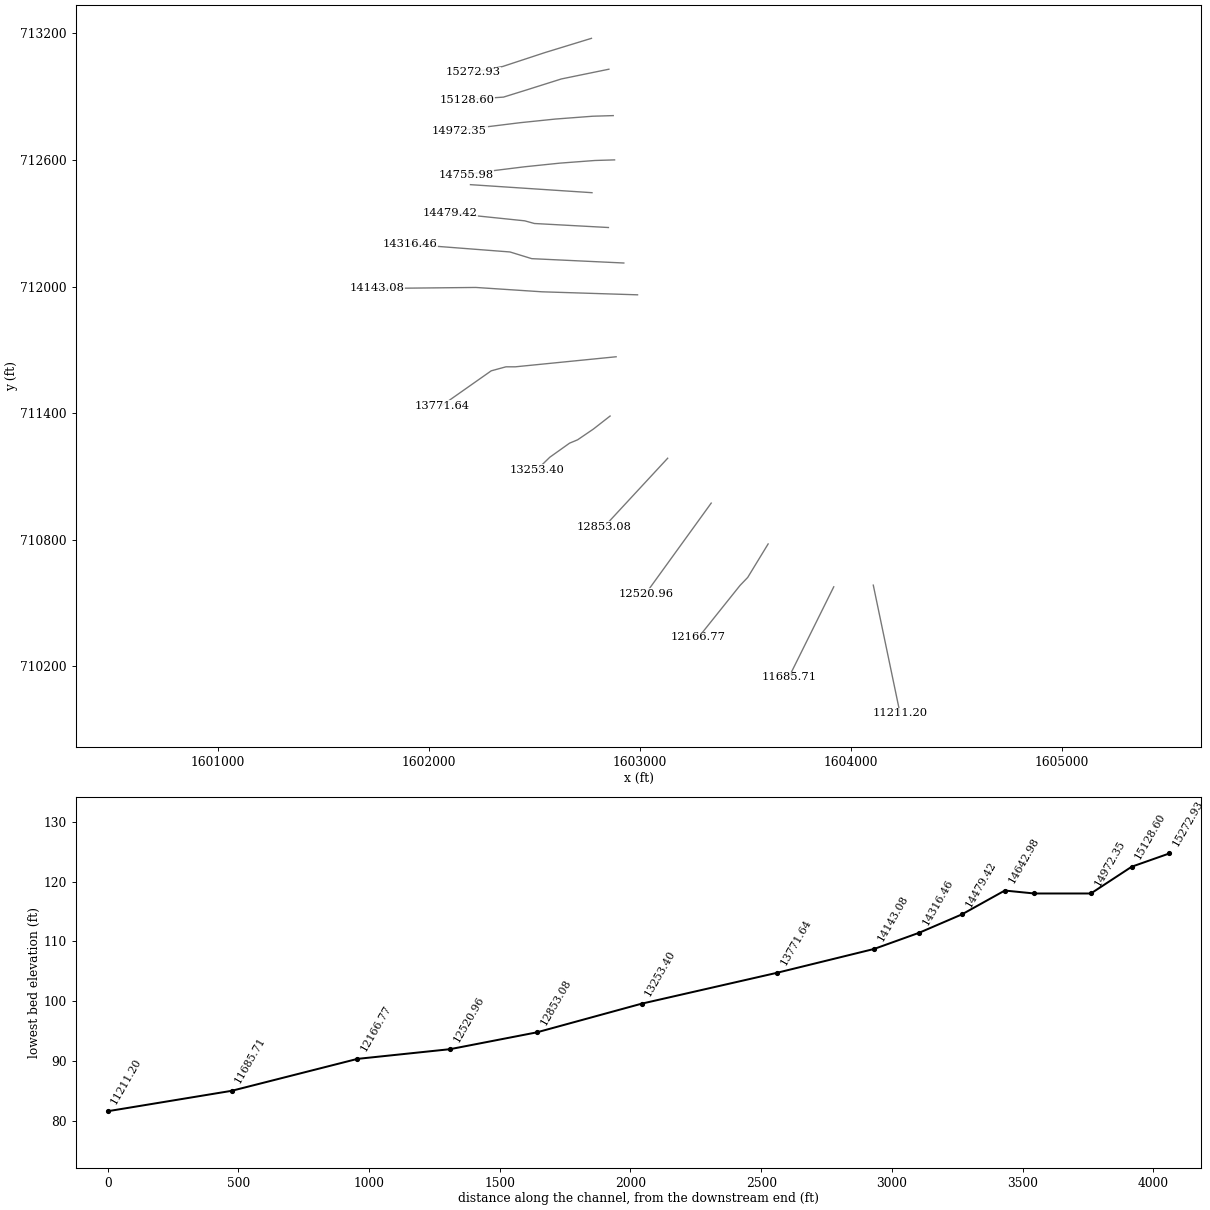
HEC-RAS study StonyRun.prj: StonyRun

--- StonyRun.g01 (geometry) --- (continued)

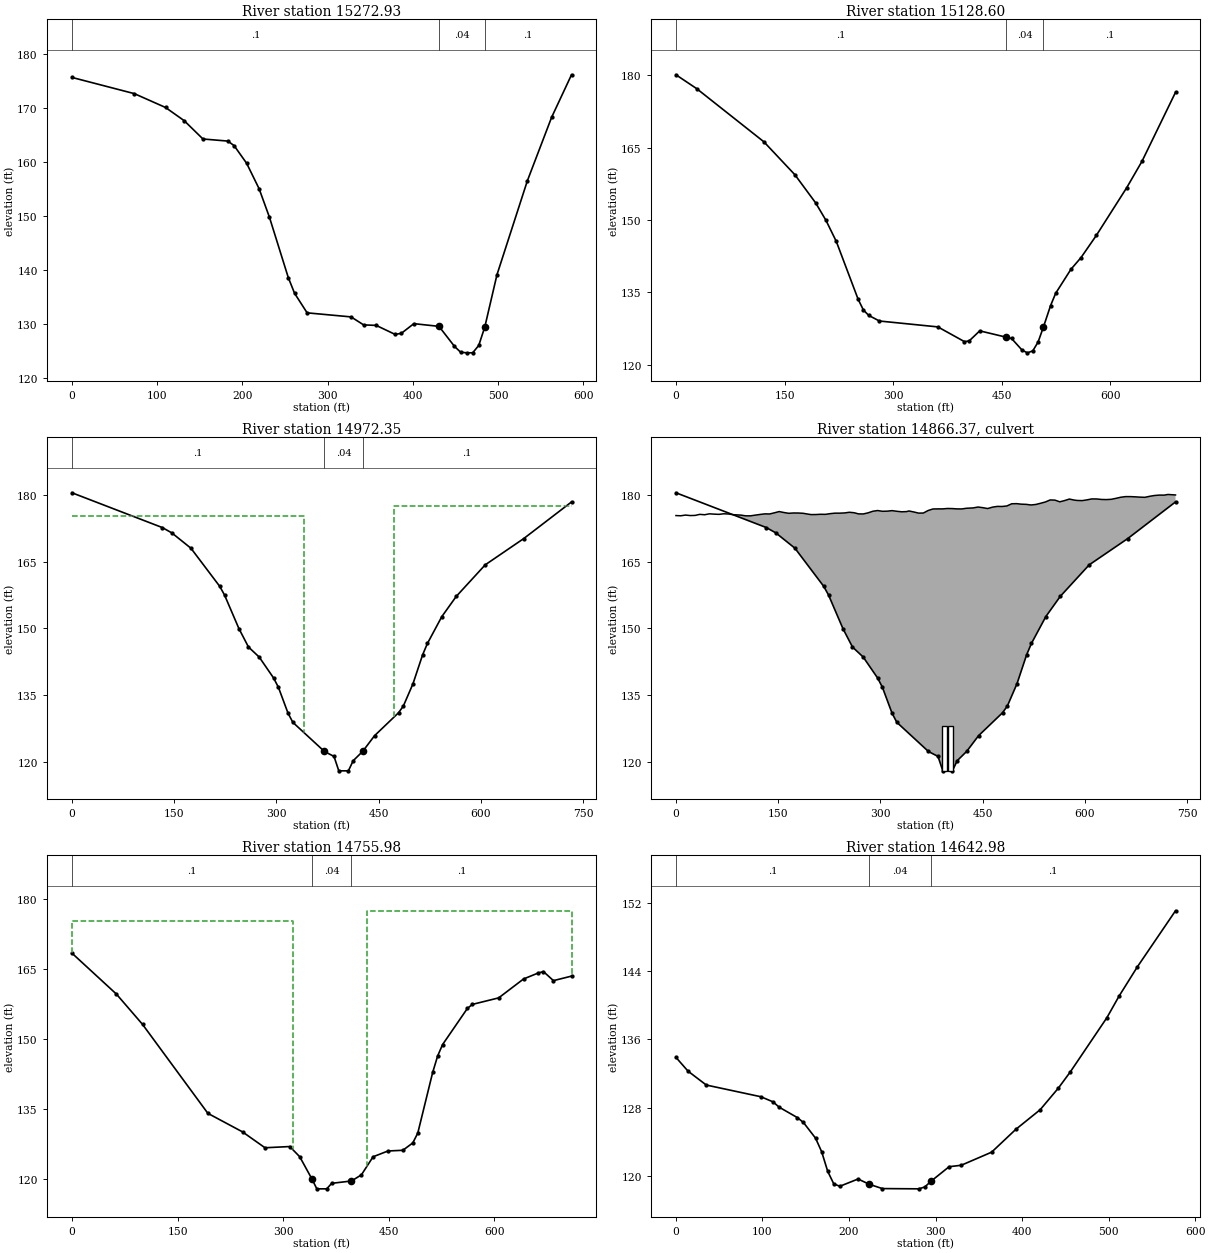
Type RM Length L Ch R = 1 ,15272.93,141.52,144.33,141.68
XS GIS Cut Line= 4
1602770.29525413713177.055796877 1602548.6805838713109.169358969
1602349.17366995713043.5196479711602207.25316173 713016.38778609
#Sta/Elev= 30
       0  175.65   73.21  172.65  109.82  170.09  131.78  167.64  153.74  164.26
  183.03  163.87  190.35  163.02  204.99  159.77  219.63  155.06  231.78  149.78
  253.89  138.62  261.26  135.71  275.99  132.09  327.58  131.34  342.32  129.86
  357.06  129.77  379.16  128.11  386.53  128.29  401.27  130.09  430.75  129.59
  448.94  125.89  456.06  124.82  463.19  124.69  470.32   124.7  477.44  126.06
  484.57   129.5  498.82  139.14  534.46  156.51  562.96  168.27   586.3  176.14
#Mann= 3 , 0 , 0
       0      .1       0  430.75     .04       0  484.57      .1       0
Bank Sta=430.75,484.57
XS Rating Curve= 0 ,0
Exp/Cntr=0.3,0.1

Type RM Length L Ch R = 1 ,15128.60,163.41,156.25,142.78
XS GIS Cut Line= 5
1602853.00575139713030.7218402181602628.02497767712984.628268451
1602460.83171691 712931.861601041602353.34780256712898.468540266
1602181.16483301712886.989675641
#Sta/Elev= 30
       0  180.14   28.58  177.27  121.47  166.24  164.34   159.4  192.93  153.58
  207.22  149.95  221.51  145.57  251.68  133.57  259.02  131.33  266.36  130.23
  281.04  129.07  361.78  127.85  398.48   124.8  404.98  124.93  419.64  127.03
  455.81  125.73  463.62  125.45  478.28  123.01  485.61  122.47  492.94  122.88
  500.27  124.72   507.6  127.81  517.53  132.28  524.54  134.82  545.59  139.79
  559.62  142.24  580.67  146.81  622.76  156.74  643.81   162.2  690.09   176.5
#Mann= 3 , 0 , 0
       0      .1       0  455.81     .04       0   507.6      .1       0
Bank Sta=455.81,507.6
XS Rating Curve= 0 ,0
Exp/Cntr=0.5,0.3

Type RM Length L Ch R = 1 ,14972.35,210.47,216.37,212.26
BEGIN DESCRIPTION:
Channel bottom center lowered approx. 1 ft based on typical flow depths at other bridges on Stony Run.
END DESCRIPTION:
XS GIS Cut Line= 6
1602873.57387218712810.822859421 1602776.2388965712807.873314753
1602599.37869476712794.4930961281602431.07542656712777.079502374
 1602276.9323463712757.9951209871602144.55927326712739.084682003
#Sta/Elev= 30
       0  180.49  132.47  172.68   146.5  171.48  174.57  168.03  216.88  159.45
  223.91   157.5  244.98  149.97  259.03  145.82  274.75  143.57  295.89  138.86
  302.94  136.77  317.04  130.96  324.09   128.9  370.46  122.35  384.52  121.24
  391.55     118  405.61     118  412.64  120.27   426.7  122.39  443.96  125.89
  479.23  131.06  486.28  132.57  500.39  137.57   514.5  144.06  521.55  146.62
  542.71  152.66  563.87   157.2  606.35  164.29  662.92   170.2     733  178.43
#Mann= 3 , 0 , 0
       0      .1       0  370.46     .04       0   426.7      .1       0
#XS Ineff= 2 , 0
       0  340.44   175.3   472.3       0   177.5
Permanent Ineff=
       F       F
Bank Sta=370.46,426.7
XS Rating Curve= 0 ,0
Exp/Cntr=0.5,0.3

Type RM Length L Ch R = 2 ,14866.37,,,
BEGIN DESCRIPTION:
Railroad Bridge, MDE Bridge #: CE033108FS-10
No survey or photos made available.
Assume culverts same size as those under John F. Kennedy Memorial Highway upstream.
Top of road obtained from DEM.
END DESCRIPTION:
Bridge Culvert--1,0,-1,-1, 0
Deck Dist Width WeirC Skew NumUp NumDn MinLoCord MaxHiCord MaxSubmerge Is_Ogee
98,20,2.6,0, 106, 103, , , 0.95, 0, 2,2,,
       0       7   14.01   21.01   28.01   35.02   42.02   49.02   56.03   63.03
   70.03   77.04   84.04   91.04   95.38   102.4  109.41  116.43  123.45  130.47
  137.48   144.5  151.52  158.53  165.55  172.57  179.59   186.6  193.62  198.19
  205.21  212.24  219.26  226.29  233.31  240.34  247.36  254.38  261.41  267.76
  274.81  281.86  288.91  295.96  303.01  310.05   317.1  324.15   331.2  338.25
  341.94  348.97     356  363.03  370.06  377.09  384.12  391.15  398.18  405.21
  412.24  419.27   426.3  436.23  443.28  450.34  457.39  464.44   471.5  478.55
   485.6  492.66  499.71  506.76  513.82  520.87  527.93  534.98  542.03  549.09
  556.14  563.19  570.25   577.3  584.35  589.06  596.13   603.2  610.27  617.34
  624.41  631.48  638.56  645.63   652.7  659.77  666.84  673.91  680.98  688.05
  695.12  702.19  709.27  716.34  721.84     733
  175.37  175.32  175.48  175.37   175.4  175.64  175.55  175.76  175.69  175.64
  175.77  175.72  175.57  175.51  175.47  175.31  175.31  175.47  175.62  175.75
  175.73  175.99  176.27  176.05  175.88  175.95  175.94  175.88   175.7  175.59
   175.6  175.66  175.64   175.8  175.91  175.91  175.96  176.11  176.01  175.75
  175.73  175.98  176.34   176.5  176.33  176.36  176.48  176.33  176.22  176.26
   176.4  176.18  175.92  175.94  176.51  176.85  176.87  176.87  176.96  176.94
  176.87  176.86  177.01  177.09  177.29  177.14  176.95  177.26  177.43  177.41
  177.53  178.02  178.05  177.93  177.89  177.75  177.86  178.13  178.42  178.88
  178.84  178.46  178.74  179.08  178.85  178.76  178.73   178.9  179.11   179.1
  178.99  178.96  179.02  179.24  179.49  179.63  179.63  179.58  179.51  179.47
   179.7  179.88  179.97  179.96  180.11     180
                                                                                
                                                                                
                                                                                
                                                                                
                                                                                
                                                                                
                                                                                
                                                                                
                                                                                
                                                                                
                                                
       0       7   14.01   21.01   28.01   35.02   42.02   49.02   56.03   63.03
   70.03   77.04   84.04   91.04   95.38   102.4  109.41  116.43  123.45  130.47
  137.48   144.5  151.52  158.53  165.55  172.57  179.59   186.6  193.62  198.19
  205.21  212.24  219.26  226.29  233.31  240.34  247.36  254.38  261.41  267.76
  274.81  281.86  288.91  295.96  303.01  310.05   317.1  324.15   331.2  338.25
  341.94  348.97     356  363.03  370.06  377.09  384.12  391.15  398.18  405.21
  412.24  419.27   426.3  436.23  443.28  450.34  457.39  464.44   471.5  478.55
   485.6  492.66  499.71  506.76  513.82  520.87  527.93  534.98  542.03  549.09
  556.14  563.19  570.25   577.3  584.35  589.06  596.13   603.2  610.27  617.34
  624.41  631.48  638.56  645.63   652.7  659.77  666.84  673.91  680.98  688.05
  695.12  702.19  709.56
  175.37  175.32  175.48  175.37   175.4  175.64  175.55  175.76  175.69  175.64
  175.77  175.72  175.57  175.51  175.47  175.31  175.31  175.47  175.62  175.75
  175.73  175.99  176.27  176.05  175.88  175.95  175.94  175.88   175.7  175.59
   175.6  175.66  175.64   175.8  175.91  175.91  175.96  176.11  176.01  175.75
  175.73  175.98  176.34   176.5  176.33  176.36  176.48  176.33  176.22  176.26
   176.4  176.18  175.92  175.94  176.51  176.85  176.87  176.87  176.96  176.94
  176.87  176.86  177.01  177.09  177.29  177.14  176.95  177.26  177.43  177.41
  177.53  178.02  178.05  177.93  177.89  177.75  177.86  178.13  178.42  178.88
  178.84  178.46  178.74  179.08  178.85  178.76  178.73   178.9  179.11   179.1
  178.99  178.96  179.02  179.24  179.49  179.63  179.63  179.58  179.51  179.47
   179.7  179.88  179.97
                                                                                
                                                                                
                                                                                
                                                                                
                                                                                
                                                                                
                                                                                
                                                                                
                                                                                
                                                                                
                        
BR Coef=-1 , 1 , 0 ,, 0 ,,,0.8,0,0.5,0,
WSPro=,,,, 1 ,,,, 0 ,,,, 0 ,,,,-1 ,-1 ,-1 , 0 , 0 , 0 , 0 , 0
Multiple Barrel Culv=2,10,8,64,0.015,0.4,1,8,1,118,118, 2,Culvert #1  , 0 ,76.2
     394     351     403     360
Culvert Bottom n=0.015
BC Design=,, 0 ,, 0 ,,,,,,
BC Use User HTab Curves=0
BC User HTab FreeFlow(D)= 0

Type RM Length L Ch R = 1 ,14755.98,121.23,113.01,101.97
BEGIN DESCRIPTION:
Channel bottom center lowered approx. 1 ft based on typical flow depths at other bridges on Stony Run.
END DESCRIPTION:
XS GIS Cut Line= 6
1602879.93458873 712600.919211821602786.79957968712598.096938849
1602620.37285627712585.5147044511602453.63366427712568.269024417
1602304.68551248712549.8278246821602174.25775808712531.195288315
#Sta/Elev= 30
       0  168.43   63.03  159.69   100.2   153.2  193.08  134.15  242.25  130.19
  274.18  126.79  309.42  127.05  323.52  124.87   340.8  120.12  347.83     118
  361.89     118  368.92  119.18  397.04  119.68   411.1  120.99  427.72  124.86
  448.88   126.1  470.04  126.25  484.15  127.83  491.21  129.93  512.37  142.92
  519.42  146.43  526.47  148.88  561.74  156.62  568.79  157.47  606.09  158.86
  641.45  162.91  662.66  164.21  669.73  164.49  683.88  162.55  709.56  163.52
#Mann= 3 , 0 , 0
       0      .1       0   340.8     .04       0  397.04      .1       0
#XS Ineff= 2 , 0
       0  314.31   175.3  418.39       0   177.5
Permanent Ineff=
       F       F
Bank Sta=340.8,397.04
XS Rating Curve= 0 ,0
Exp/Cntr=0.5,0.3

Type RM Length L Ch R = 1 ,14642.98,163.15,163.55,157.33
XS GIS Cut Line= 2
1602772.95664078712445.4344562741602196.84983344712483.524162531
#Sta/Elev= 30
       0  133.88   14.03  132.26   35.08  130.64   98.21  129.27  112.24  128.67
  119.26  128.05  140.31  126.83  147.32  126.26  161.35  124.42  168.37  122.84
  175.38  120.54   182.4  119.07  189.41  118.79  210.46  119.64  223.56  119.02
  238.52  118.52  280.61  118.49  287.63  118.71  294.64  119.37  315.69  121.08
  329.72  121.25  364.79  122.78  392.86  125.46  420.92  127.75  441.96  130.28
  455.99  132.21  498.09  138.53  512.12  141.05  533.16  144.46  577.36  151.04
#Mann= 3 , 0 , 0
       0      .1       0  223.56     .04       0  294.64      .1       0
Bank Sta=223.56,294.64
XS Rating Curve= 0 ,0
Exp/Cntr=0.3,0.1

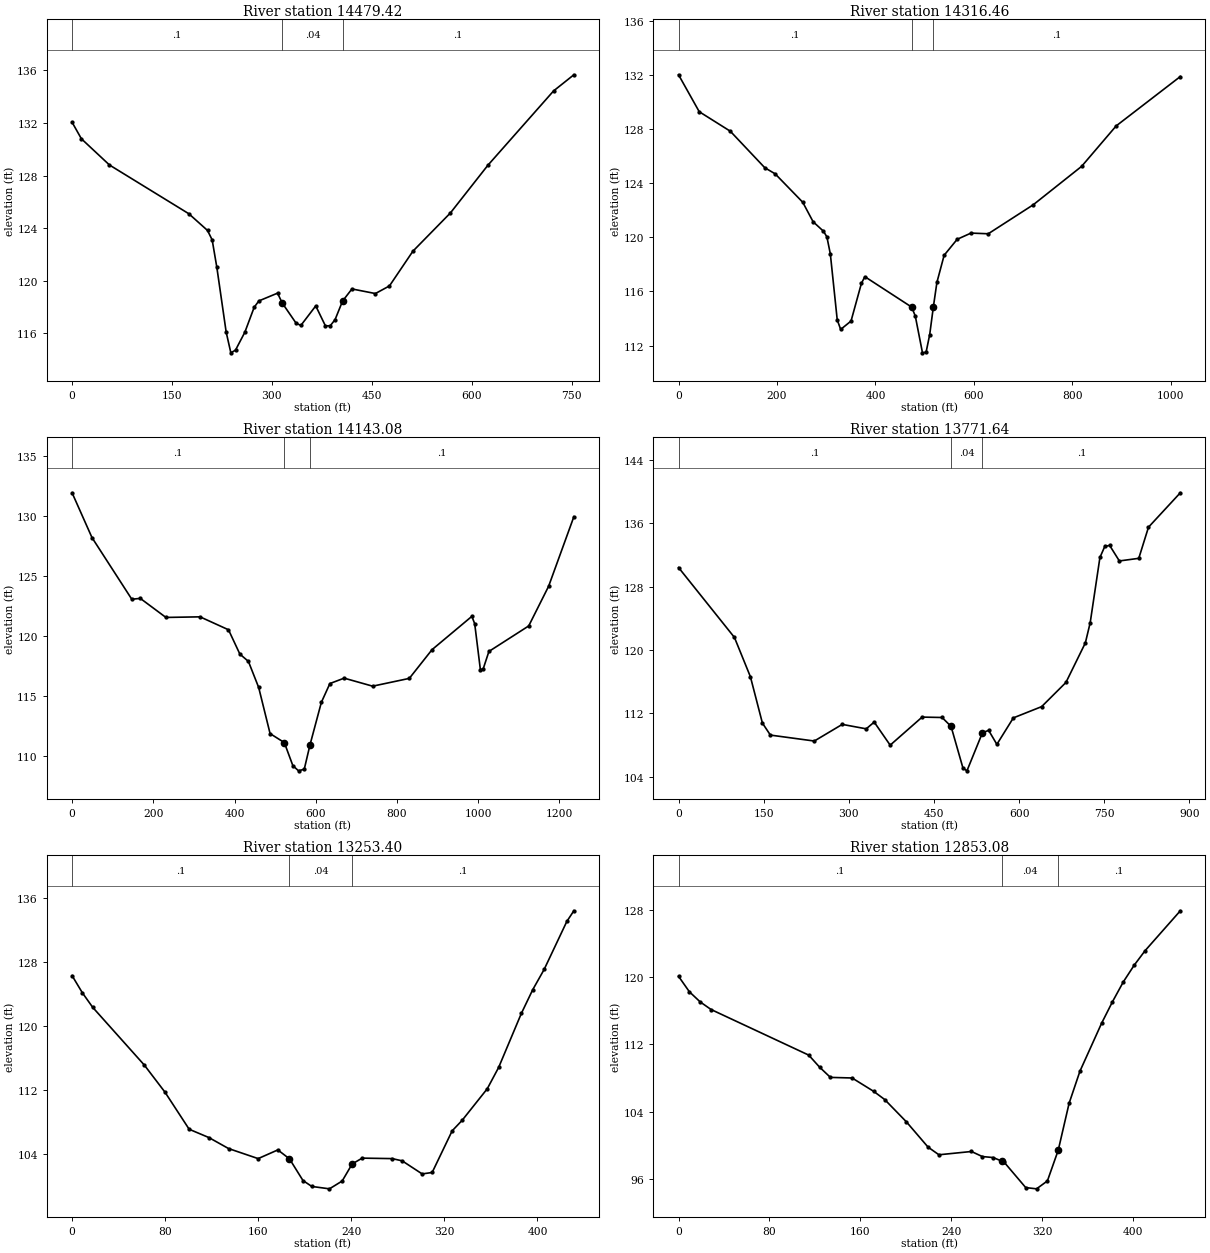
Type RM Length L Ch R = 1 ,14479.42,167.66,162.96,159.57
XS GIS Cut Line= 4
1602850.72312443712280.379062429 1602499.9804125 712299.42391555
1602453.95535077712312.1204843071602101.62556776712348.623119488
#Sta/Elev= 30
       0  132.06   14.02   130.8   56.08  128.81  175.26   125.1   203.3  123.83
  210.31  123.11  217.32  121.02  231.34  116.09  238.35  114.52  245.36  114.73
  259.38  116.09   273.4  117.99  280.41  118.47  308.45  119.06  315.46  118.31
   336.5  116.76  343.51  116.61  365.78  118.09  380.31  116.57  387.57  116.58
  394.83  117.05  406.04  118.46  420.12  119.38   455.3  119.03  476.42  119.61
   511.6  122.25   567.9  125.16   624.2  128.79  722.73  134.44  753.22  135.67
#Mann= 3 , 0 , 0
       0      .1       0  315.46     .04       0  406.04      .1       0
Bank Sta=315.46,406.04
XS Rating Curve= 0 ,0
Exp/Cntr=0.3,0.1

Type RM Length L Ch R = 1 ,14316.46,158.28,173.38,177.31
XS GIS Cut Line= 4
1602923.72839475712112.1495264021602487.28384376712132.781450629
1602384.12422259712164.5228725221601911.17703642712201.025507703
#Sta/Elev= 30
       0  132.01   42.05  129.28  105.12  127.84   175.2  125.14  196.22  124.69
  252.28  122.59   273.3  121.15  294.33  120.45  301.34  120.03  308.34  118.77
  322.36  113.89  329.37  113.19  350.39  113.81  371.41  116.59  378.42  117.09
  473.55  114.84  480.88  114.18  495.52  111.46  502.85  111.51  510.17  112.81
  517.49  114.83  524.82  116.67  539.47  118.67  565.93  119.85  594.01  120.31
  629.11  120.26  720.38   122.4  818.68  125.24  888.88  128.23 1019.22  131.88
#Mann= 3 , 0 , 0
       0      .1       0  473.55     .04       0  517.49      .1       0
Bank Sta=473.55,517.49
XS Rating Curve= 0 ,0
Exp/Cntr=0.3,0.1

Type RM Length L Ch R = 1 ,14143.08,388.11,371.44,382.32
XS GIS Cut Line= 4
1602988.79830964711961.3777724061602536.48304769711975.661412269
1602222.24297096711996.2933364961601754.05699804711991.532123193
#Sta/Elev= 30
       0  131.96   49.02  128.22  147.07  123.07  168.08  123.14  231.12  121.55
  315.16   121.6  385.19  120.52  413.21  118.49  434.22  117.88  459.56   115.7
  487.62  111.85  522.69   111.1  543.74  109.17  557.77  108.74   571.8  108.88
  585.83   110.9  613.89  114.46  634.93  116.03  670.01  116.48  740.16  115.81
  830.46  116.46  886.46  118.86  984.47  121.64  991.47  121.03 1005.47  117.19
 1012.47  117.26 1026.47  118.71 1124.48  120.84 1173.48  124.15 1235.67  129.96
#Mann= 3 , 0 , 0
       0      .1       0  522.69     .04       0  585.83      .1       0
Bank Sta=522.69,585.83
XS Rating Curve= 0 ,0
Exp/Cntr=0.3,0.1

Type RM Length L Ch R = 1 ,13771.64,386.81,518.24,511.13
XS GIS Cut Line= 5
1602887.22575961711667.7696198971602409.51736011711620.157487065
 1602365.0793695711620.1574870651602295.24824132711601.112633929
1602060.36171931711436.057240084
#Sta/Elev= 30
       0  130.41   98.49  121.59  126.62  116.63  147.73  110.79   161.8  109.27
  239.18  108.52  288.42  110.62  330.63  110.06   344.7  110.91  372.84     108
  429.12  111.54  464.29  111.49  480.07  110.37  501.07  105.11  508.07  104.76
  535.34  109.56  546.28  109.87  560.79   108.1  589.81  111.44  639.67  112.86
  682.45  115.91  716.67   120.9  725.23  123.46  742.34  131.68  750.89  133.07
  759.45   133.2  776.56  131.24  810.78  131.57  827.89   135.5  883.98  139.84
#Mann= 3 , 0 , 0
       0      .1       0  480.07     .04       0  535.34      .1       0
Bank Sta=480.07,535.34
XS Rating Curve= 0 ,0
Exp/Cntr=0.3,0.1

Type RM Length L Ch R = 1 ,13253.40,368.31,400.32,403.45
XS GIS Cut Line= 6
1602858.65847991711386.8580361461602779.30492519 711324.96226348
1602704.71258374711274.1759884361602666.62287743711258.305277482
1602572.98568287711191.6482915131602512.67698126711132.926661029
#Sta/Elev= 30
       0  126.33    8.88  124.17   17.76  122.35   62.14  115.11    79.9  111.71
  100.64  107.07  117.58  106.03  134.51  104.65  159.92  103.39  176.85  104.48
  186.86  103.36  198.46  100.64  206.04    99.9  221.21    99.6  232.14  100.58
  240.73  102.72  249.33  103.45   275.1  103.39   283.7  103.11  300.88  101.47
  309.47  101.65  326.66  106.87  335.25  108.19  356.85  112.15  366.62  114.82
  386.16   121.6  395.93  124.57   405.7   127.1  425.24  133.13  431.26  134.46
#Mann= 3 , 0 , 0
       0      .1       0  186.86     .04       0  240.73      .1       0
Bank Sta=186.86,240.73
XS Rating Curve= 0 ,0
Exp/Cntr=0.3,0.1

Type RM Length L Ch R = 1 ,12853.08,321.6,332.12,334.73
XS GIS Cut Line= 2
1603131.63470818711186.8870782411602831.67827128710863.124574929
#Sta/Elev= 30
       0  120.09    9.54  118.25   19.08  117.04   28.63  116.14  114.51  110.72
  124.05  109.29  133.59  108.07  152.68     108  171.76   106.4  181.31  105.44
  200.39  102.79  219.48   99.78  229.02   98.87  257.65   99.26  267.19   98.66
  276.73   98.54  284.32   98.12  286.27   98.01  305.36   94.97   314.9   94.82
  324.44   95.76  333.99   99.42  343.53  104.99  353.07  108.81  372.16  114.52
   381.7  117.07  391.24  119.43  400.78  121.41  410.33  123.13  441.36  127.88
#Mann= 3 , 0 , 0
       0      .1       0  284.32     .04       0  333.99      .1       0
Bank Sta=284.32,333.99
XS Rating Curve= 0 ,0
Exp/Cntr=0.3,0.1

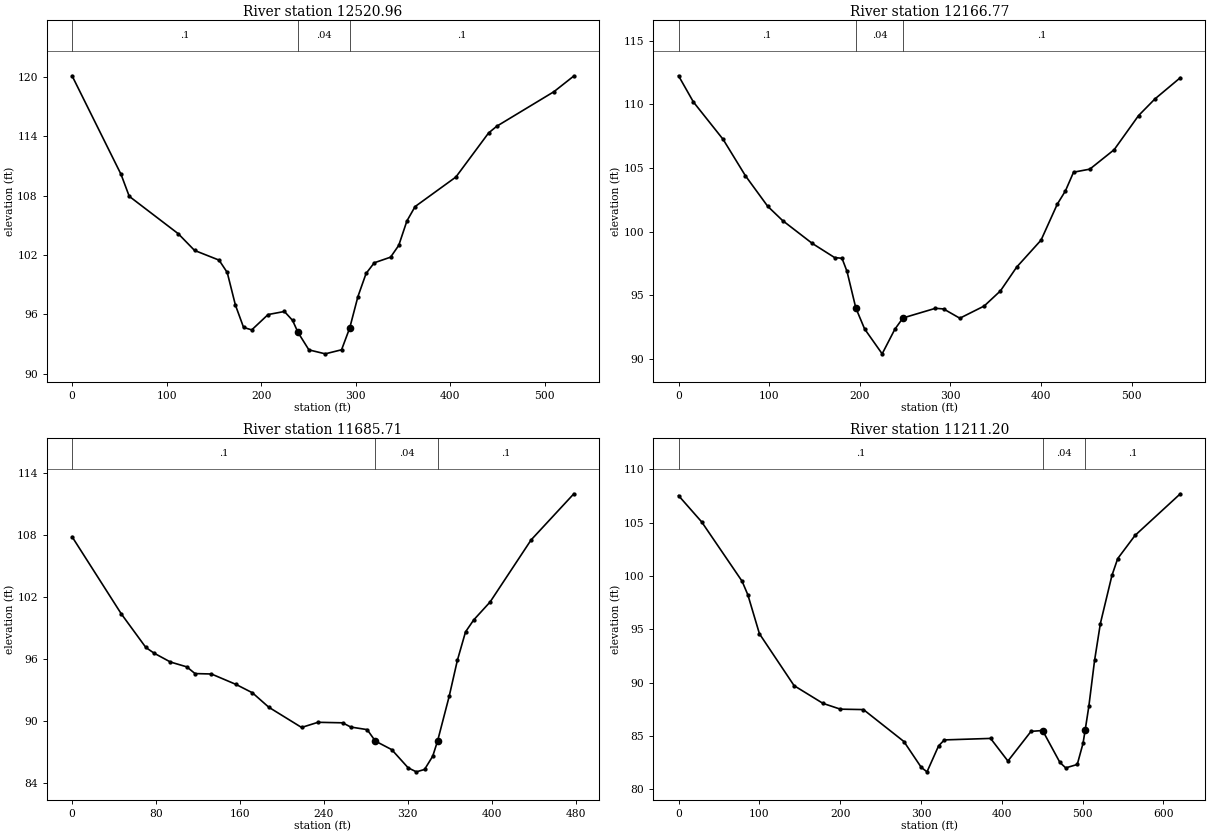
Type RM Length L Ch R = 1 ,12520.96,346.39,354.19,337.76
XS GIS Cut Line= 2
1603337.95395049710974.2195515481603026.88801596710544.123284906
#Sta/Elev= 30
       0  120.11   51.83  110.14   60.47  107.93  112.31  104.15  129.58  102.46
   155.5  101.48  164.14  100.23  172.78   96.94  181.42   94.68  190.06   94.43
  207.33   95.98  224.61   96.29  233.25   95.39  239.02   94.17  250.53   92.41
  267.81   92.01  285.08   92.42  293.72   94.63  302.36   97.79     311  100.13
  319.64  101.21  336.92  101.78  345.56  102.97   354.2  105.44  362.84  106.89
  406.03  109.88  440.59  114.33  449.22  115.01   509.7   118.5   530.8  120.09
#Mann= 3 , 0 , 0
       0      .1       0  239.02     .04       0  293.72      .1       0
Bank Sta=239.02,293.72
XS Rating Curve= 0 ,0
Exp/Cntr=0.3,0.1

Type RM Length L Ch R = 1 ,12166.77,399.69,481.06,446.53
XS GIS Cut Line= 4
1603607.75603656710780.5968780221603510.94469976710621.889768556
1603474.44206463710583.8000622691603277.64524888710337.804042622
#Sta/Elev= 30
       0  112.25    16.4  110.19    49.2  107.25    73.8  104.39   98.39  101.99
  114.79  100.87  147.59   99.07  172.19   97.96  180.39    97.9   185.9   96.87
   195.6      94   205.3   92.35  224.69   90.39  238.66   92.32  247.63   93.21
  283.48   93.97  292.45   93.92  310.38   93.19  337.27   94.15   355.2   95.34
  373.13   97.21  400.02   99.33  417.95  102.16  426.91   103.2  435.88  104.67
  453.81  104.91   480.7  106.44  507.59  109.12  525.52  110.42  553.69   112.1
#Mann= 3 , 0 , 0
       0      .1       0   195.6     .04       0  247.63      .1       0
Bank Sta=195.6,247.63
XS Rating Curve= 0 ,0
Exp/Cntr=0.3,0.1

Type RM Length L Ch R = 1 ,11685.71,377.45,474.51,481.85
XS GIS Cut Line= 2
 1603918.8219711 710577.451777891603706.15444446710148.942582369
#Sta/Elev= 30
       0  107.84   46.89  100.37   70.33   97.11   78.15   96.56   93.78    95.7
  109.41   95.23  117.22   94.58  132.85   94.54  156.29   93.53  171.92   92.72
  187.55   91.32  218.81   89.36  234.44   89.86  257.88   89.81   265.7    89.4
  281.33   89.15  289.14   88.04  304.77   87.21   320.4   85.45  328.22   85.06
  336.03   85.29  343.85   86.58  348.51   88.07  359.48   92.36  367.29   95.85
   375.1   98.62  382.92   99.78  398.55  101.52  437.62  107.53  478.38     112
#Mann= 3 , 0 , 0
       0      .1       0  289.14     .04       0  348.51      .1       0
Bank Sta=289.14,348.51
XS Rating Curve= 0 ,0
Exp/Cntr=0.3,0.1

Type RM Length L Ch R = 1 ,11211.20,204.27,306.32,322.18
XS GIS Cut Line= 2
1604106.09636027710585.3871333751604233.06204785709977.538904145
#Sta/Elev= 30
       0  107.52    28.6  105.06   78.66    99.5   85.81   98.22  100.12   94.58
  143.02   89.72  178.78   88.06  200.23   87.52  228.83   87.48  278.89   84.49
  300.35   82.07   307.5   81.65   321.8   84.08  328.95   84.64  386.16   84.78
  407.61   82.66  436.22   85.44  450.52   85.52  471.97   82.53  479.12   82.02
  493.42   82.34  500.57   84.32  503.15   85.53  507.73   87.77  514.84   92.08
  522.03   95.54  536.33  100.04  543.48  101.62  564.93  103.79  620.97  107.69
#Mann= 3 , 0 , 0
       0      .1       0  450.52     .04       0  503.15      .1       0
Bank Sta=450.52,503.15
XS Rating Curve= 0 ,0
Exp/Cntr=0.3,0.1