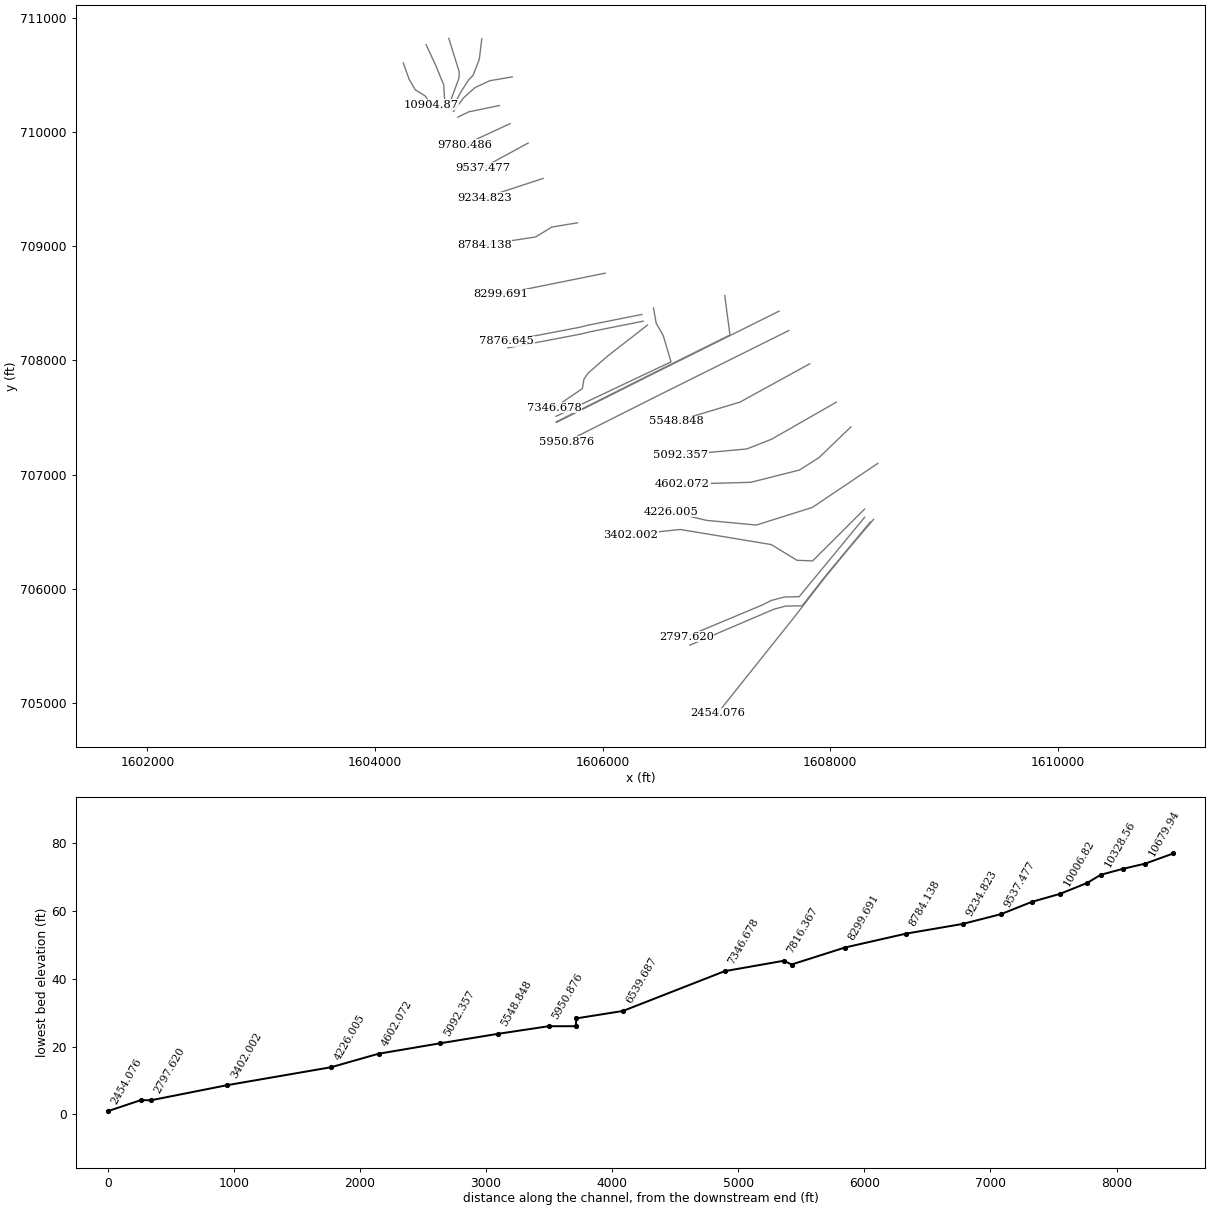
HEC-RAS study StonyRun.prj: StonyRun

--- StonyRun.g01 (geometry) --- (continued)

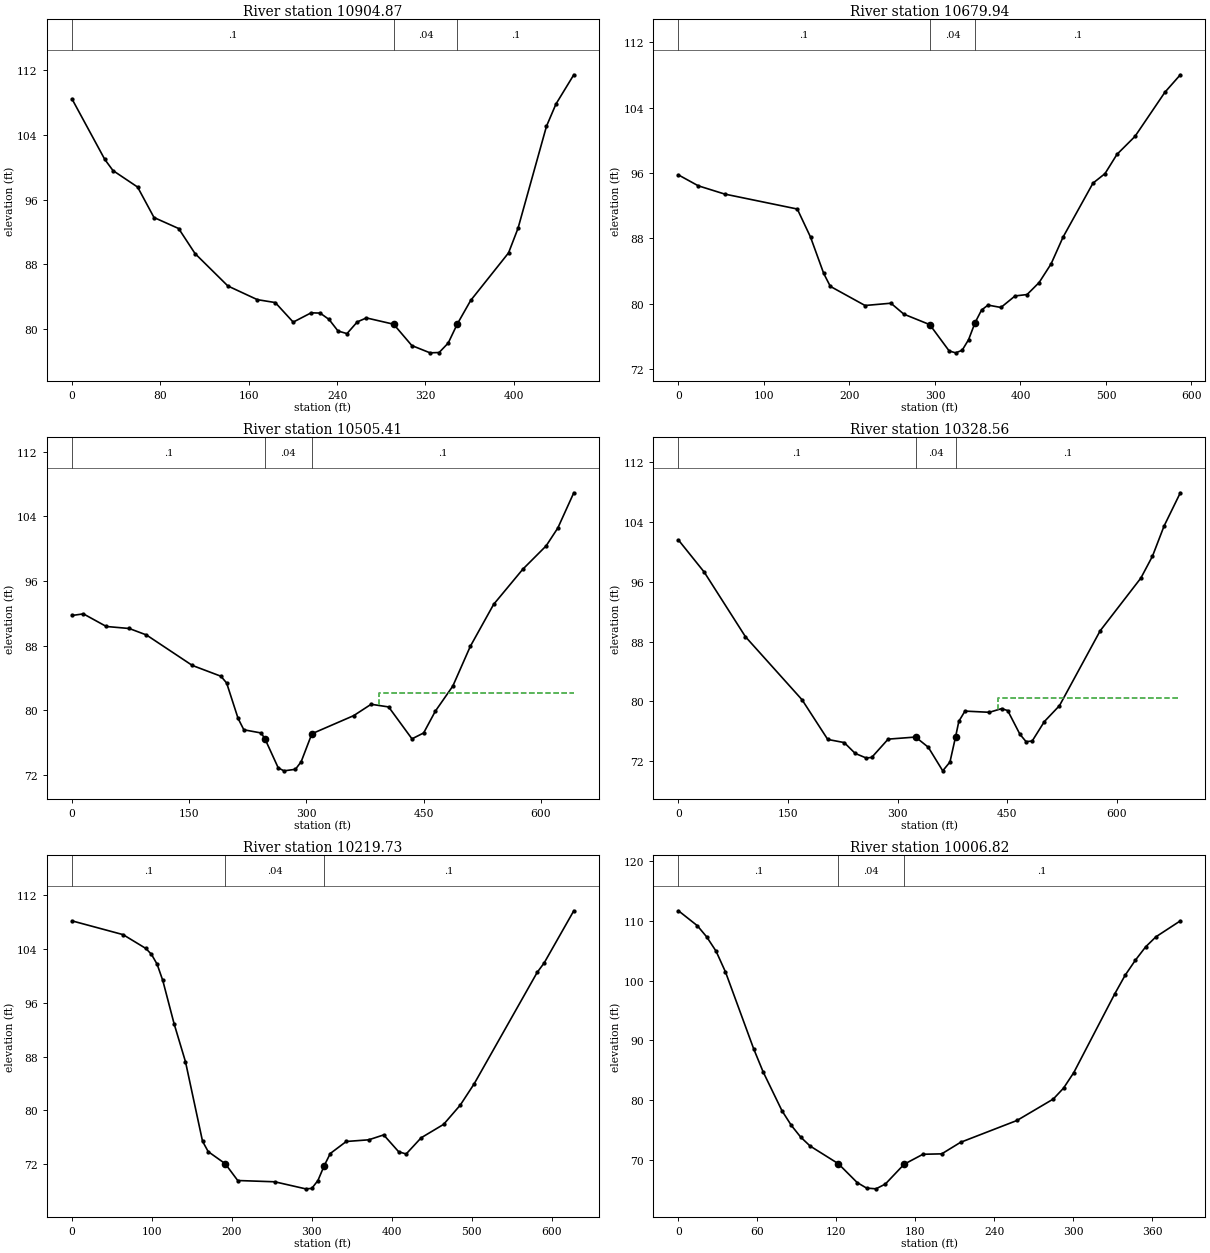
Type RM Length L Ch R = 1 ,10904.87,255.23,224.94,197.9
XS GIS Cut Line= 5
1604248.93275881710602.8449154051604299.71903382710460.008516908
1604353.67945103 710367.958393411604440.96836123710313.997976199
1604494.92877844 710237.81856364
#Sta/Elev= 30
       0  108.46   29.72  100.97   37.15   99.59   59.43   97.55   74.29   93.78
   96.58   92.42  111.44   89.32  141.16   85.31  167.82   83.62  184.05   83.26
  200.28   80.84  216.51   81.99  224.62   81.96  232.74   81.17  240.85   79.74
  248.97   79.42   258.3   80.87  266.53   81.36  291.21   80.58  307.67   77.94
  324.13   77.04  332.36   77.08  340.59   78.25  348.82   80.61  360.92   83.52
  395.23   89.41  403.81   92.46  429.54  105.07  438.12  107.82  454.27  111.44
#Mann= 3 , 0 , 0
       0      .1       0  291.21     .04       0  348.82      .1       0
Bank Sta=291.21,348.82
XS Rating Curve= 0 ,0
Exp/Cntr=0.3,0.1

Type RM Length L Ch R = 1 ,10679.94,177.02,174.53,166.63
XS GIS Cut Line= 4
1604448.90371671710763.1390959771604534.60555583710579.038848996
  1604604.436684710409.2222418641604615.54618163710209.251283944
#Sta/Elev= 30
       0   95.77   23.16   94.44   54.05   93.43  138.98    91.6  154.43   88.17
  169.87   83.72  177.59   82.14  218.21    79.8  248.48   80.08  263.62   78.74
   293.9   77.46   316.6   74.24  324.17   74.01  331.74   74.32  339.31   75.62
  346.88    77.7  354.45   79.24  362.01   79.85  377.15   79.56   393.7   80.97
  407.72   81.14  421.74    82.6  435.76   84.88  449.78   88.16  484.84   94.77
  498.86   95.93  512.88   98.29  533.91  100.48  568.97  105.89  586.96  108.02
#Mann= 3 , 0 , 0
       0      .1       0   293.9     .04       0  346.88      .1       0
Bank Sta=293.9,346.88
XS Rating Curve= 0 ,0
Exp/Cntr=0.3,0.1

Type RM Length L Ch R = 1 ,10505.41,187.88,176.85,113.57
XS GIS Cut Line= 4
1604648.37621266710818.223774821 1604739.9199526 710525.28380698
1604738.61218488710471.6653307231604640.52960636710207.496252581
#Sta/Elev= 30
       0   91.73   14.67   91.93      44   90.37   73.34   90.12   95.34   89.32
  154.01   85.55  190.68   84.21  198.01   83.37  212.68   78.98  220.02   77.58
  242.02   77.19  246.91   76.49  264.02   72.87  271.35    72.5  286.02   72.69
  293.35   73.62   307.1   77.09  360.54   79.33  382.95   80.74  405.35   80.41
  435.21   76.46  450.15   77.19  465.08   79.88  487.48   82.99  509.88   87.91
  539.75   93.11  577.09   97.46  606.95  100.35  621.89  102.56  642.33  106.92
#Mann= 3 , 0 , 0
       0      .1       0  246.91     .04       0   307.1      .1       0
#XS Ineff= 2 , 0
                          392.79           82.15
Permanent Ineff=
       F       F
Bank Sta=246.91,307.1
XS Rating Curve= 0 ,0
Exp/Cntr=0.3,0.1

Type RM Length L Ch R = 1 ,10328.56,204.3,108.83,96.88
XS GIS Cut Line= 6
1604938.70064503710814.3004716781604916.46859393710633.828527212
1604861.54234995710493.8973818721604824.92485398710457.279885873
1604758.22870061710355.2740042061604671.91603146710195.726343155
#Sta/Elev= 30
       0  101.59   35.26    97.3   91.69   88.66  169.27   80.22   204.4   74.92
  226.96    74.5     242   73.05  257.04   72.44  264.56   72.51  287.12   74.96
  324.72   75.24  342.06   73.88  361.86   70.72  371.76    71.9  379.36   75.23
  383.95   77.35  392.31   78.71  425.76   78.55  442.49   79.04  450.85   78.78
  467.58   75.61  475.94   74.63  484.31    74.7  501.04   77.31  521.74   79.44
  577.45   89.45  633.16    96.5  649.08   99.43  664.99  103.47  687.22  107.91
#Mann= 3 , 0 , 0
       0      .1       0  324.72     .04       0  379.36      .1       0
#XS Ineff= 2 , 0
                          437.29           80.47
Permanent Ineff=
       F       F
Bank Sta=324.72,379.36
XS Rating Curve= 0 ,0
Exp/Cntr=0.3,0.1

Type RM Length L Ch R = 1 ,10219.73,230.67,212.91,202.88
XS GIS Cut Line= 5
1605205.93662885 710480.64044112 1605009.1398131710447.311948136
1604878.99998336710387.003246561 1604779.0145044 710298.12726526
  1604688.551452 710177.50986205
#Sta/Elev= 30
       0   108.2    63.9  106.15    92.3   104.1    99.4  103.22   106.5  101.75
  113.59   99.32  127.79   92.86  141.99   87.22  163.29   75.39  170.39   73.84
  191.69   72.04  207.31   69.54   253.6   69.35  292.18    68.3   299.9   68.36
  307.61   69.54  315.33   71.71  323.04   73.56  343.03   75.35  371.13    75.6
  389.86   76.33  408.59   73.82  417.96   73.49  436.69    75.9  464.79    77.9
  485.56   80.76  503.06   83.95  581.81  100.53  590.56  101.94  627.58   109.7
#Mann= 3 , 0 , 0
       0      .1       0  191.69     .04       0  315.33      .1       0
Bank Sta=191.69,315.33
XS Rating Curve= 0 ,0
Exp/Cntr=0.3,0.1

Type RM Length L Ch R = 1 ,10006.82,211.19,226.34,231.96
XS GIS Cut Line= 3
1605093.25458114710229.8832081711604821.86542393710174.335719883
1604728.22822933710128.310658112
#Sta/Elev= 30
       0  111.68   14.29  109.19   21.44  107.31   28.58  104.91   35.73  101.43
   57.16   88.55   64.31   84.71    78.6   78.21   85.74   75.74   92.89   73.77
  100.03   72.28  121.47   69.32  135.76   66.17   142.9   65.24  150.05   65.11
  157.19   65.91  171.48   69.23  185.77    70.9  200.06   70.97  214.35    72.9
  257.22   76.56  284.82   80.15  292.62   81.98  300.42   84.59  331.61    97.8
  339.41  100.88  347.21  103.41  355.01  105.64  362.81  107.32  381.35  109.99
#Mann= 3 , 0 , 0
       0      .1       0  121.47     .04       0  171.48      .1       0
Bank Sta=121.47,171.48
XS Rating Curve= 0 ,0
Exp/Cntr=0.3,0.1

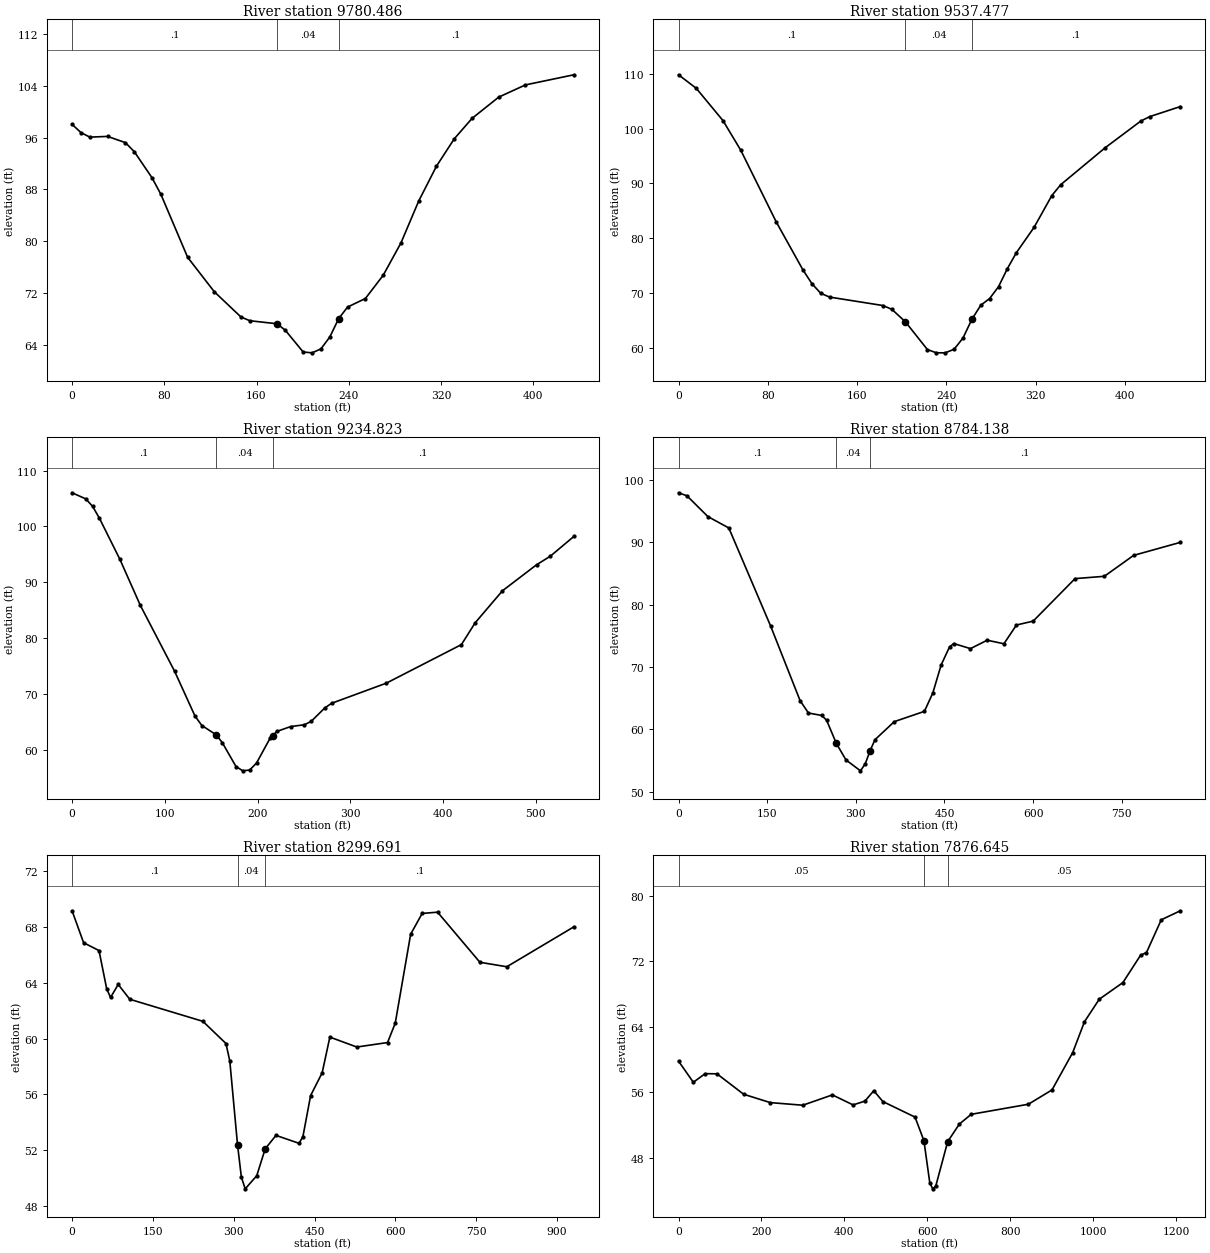
Type RM Length L Ch R = 1 ,9780.486,236.75,243.01,243.16
XS GIS Cut Line= 2
 1605186.8917757710071.1760987191604791.71107316709888.662922844
#Sta/Elev= 30
       0   98.08    7.71    96.8   15.42    96.1   30.84   96.21   46.26   95.25
   53.97   93.85   69.39    89.8   77.11   87.22  100.24    77.5  123.37   72.17
   146.5   68.26  154.21   67.68   177.9   67.21  185.05   66.19  200.47   62.84
  208.18   62.71  215.89   63.32   223.6   65.17  231.31   68.02  239.03    69.8
  254.45   71.12  269.87   74.71  285.29   79.72  300.71   86.21  316.13   91.61
  331.55   95.84  346.97      99   370.1  102.29  393.24  104.18  435.29  105.75
#Mann= 3 , 0 , 0
       0      .1       0   177.9     .04       0  231.31      .1       0
Bank Sta=177.9,231.31
XS Rating Curve= 0 ,0
Exp/Cntr=0.3,0.1

Type RM Length L Ch R = 1 ,9537.477,310.27,302.65,294.64
XS GIS Cut Line= 2
1605345.59888513709901.359491602 1604950.4181826709687.104893819
#Sta/Elev= 30
       0  109.83   15.93  107.35   39.81  101.47   55.74   96.07   87.59   82.96
  111.48   74.22  119.44   71.73   127.4   69.96  135.36   69.27  183.14   67.73
   191.1   67.04  203.19   64.77  222.95    59.7  230.92   59.11  238.88    59.1
  246.84   59.75   254.8   61.79  262.77   65.21  270.73   67.78  278.69   69.01
  286.65   71.16  294.62   74.48  302.58   77.35  318.51      82  334.43    87.8
  342.39   89.78  382.21   96.52  414.06  101.38  422.02  102.19  449.52  104.03
#Mann= 3 , 0 , 0
       0      .1       0  203.19     .04       0  262.77      .1       0
Bank Sta=203.19,262.77
XS Rating Curve= 0 ,0
Exp/Cntr=0.3,0.1

Type RM Length L Ch R = 1 ,9234.823,441.12,450.68,459.61
XS GIS Cut Line= 2
1605477.32578599709591.8806281391604963.11475135709423.651092112
#Sta/Elev= 30
       0  106.02   14.73  104.93    22.1   103.6   29.46  101.47   51.56    94.1
   73.65   85.84  110.48   74.08  132.57   66.02  139.94   64.34   155.6   62.65
  162.03   61.25  176.76   56.99  184.13   56.22  191.49   56.37  198.86   57.61
  213.59   62.09   216.3   62.53  220.95   63.29  235.68   64.15  250.41   64.47
  257.78   65.07  272.51   67.49  279.87   68.32  338.79   71.92  419.81   78.83
  434.54   82.72     464   88.46  500.83   93.13  515.56   94.65  541.03    98.2
#Mann= 3 , 0 , 0
       0      .1       0   155.6     .04       0   216.3      .1       0
Bank Sta=155.6,216.3
XS Rating Curve= 0 ,0
Exp/Cntr=0.3,0.1

Type RM Length L Ch R = 1 ,8784.138,491.52,484.45,461.06
XS GIS Cut Line= 4
1605778.23446558 709203.048209951605555.09226964709166.545574799
1605410.66880003709079.2566645891604961.52768028  709011.0126075
#Sta/Elev= 30
       0   97.98   14.19    97.5   49.65   94.16   85.12   92.33  156.05   76.54
   205.7   64.61  219.88   62.62  242.47   62.23  250.65   61.45     267   57.75
  283.36   55.09   307.9   53.34  316.08    54.5  324.26    56.6  332.44   58.34
  365.15   61.24   416.1   62.89  430.26   65.83  444.42   70.34  458.58   73.23
  465.66   73.78  493.99   72.96  522.31   74.31  550.63   73.74  571.87   76.75
  600.19   77.38  670.99    84.2  720.56   84.57  770.12   87.93  849.16   90.02
#Mann= 3 , 0 , 0
       0      .1       0     267     .04       0  324.26      .1       0
Bank Sta=267,324.26
XS Rating Curve= 0 ,0
Exp/Cntr=0.3,0.1

Type RM Length L Ch R = 1 ,8299.691,422.11,423.05,419.74
XS GIS Cut Line= 2
1606022.14965869708762.3362011021605109.19582857708578.835514322
#Sta/Elev= 30
       0   69.16   21.42   66.87   49.98   66.31   64.26   63.57    71.4   62.95
   85.68   63.88   107.1   62.82  242.76   61.24   285.6   59.65  292.74   58.39
  307.02   52.41  314.16   50.08   321.3   49.24  342.72   50.18  358.33    52.1
  378.42   53.07  421.26    52.5   428.4   52.98  442.68   55.92   464.1   57.55
  478.38   60.11  528.36    59.4  585.48   59.72  599.76   61.11  628.32   67.48
  649.74   68.97   678.3   69.06  756.84   65.47  806.82   65.15  931.21   68.01
#Mann= 3 , 0 , 0
       0      .1       0  307.02     .04       0  358.33      .1       0
Bank Sta=307.02,358.33
XS Rating Curve= 0 ,0
Exp/Cntr=0.5,0.3

Type RM Length L Ch R = 1 ,7876.645,60.92,60.28,60.35
BEGIN DESCRIPTION:
Channel bottom center lowered approx. 1 ft based on bridge survey info.
END DESCRIPTION:
XS GIS Cut Line= 5
1606344.97860031 708401.184310571605875.65605211708307.797949165
1605800.09769079708289.1415636541605566.44820215 708244.45958972
 1605157.2430709708167.422872916
#Sta/Elev= 30
       0    59.8   35.69   57.22   64.24   58.27   92.78   58.25  157.02   55.76
  221.25   54.74  299.76   54.42  371.14   55.68   421.1   54.46  449.65   54.92
  471.06   56.19  492.94   54.87   570.6   52.97  591.99    50.1  606.24   44.93
  613.37   44.22  620.49   44.54  649.38   49.98  677.51   52.12  706.01   53.31
  844.09   54.54  901.08   56.29  950.94   60.84  979.43   64.61 1015.05   67.35
 1072.03   69.38 1114.77   72.72 1129.01   73.05 1164.63   77.04 1210.63   78.14
#Mann= 3 , 0 , 0
       0     .05       0  591.99     .04       0  649.38     .05       0
Bank Sta=591.99,649.38
XS Rating Curve= 0 ,0
Exp/Cntr=0.5,0.3

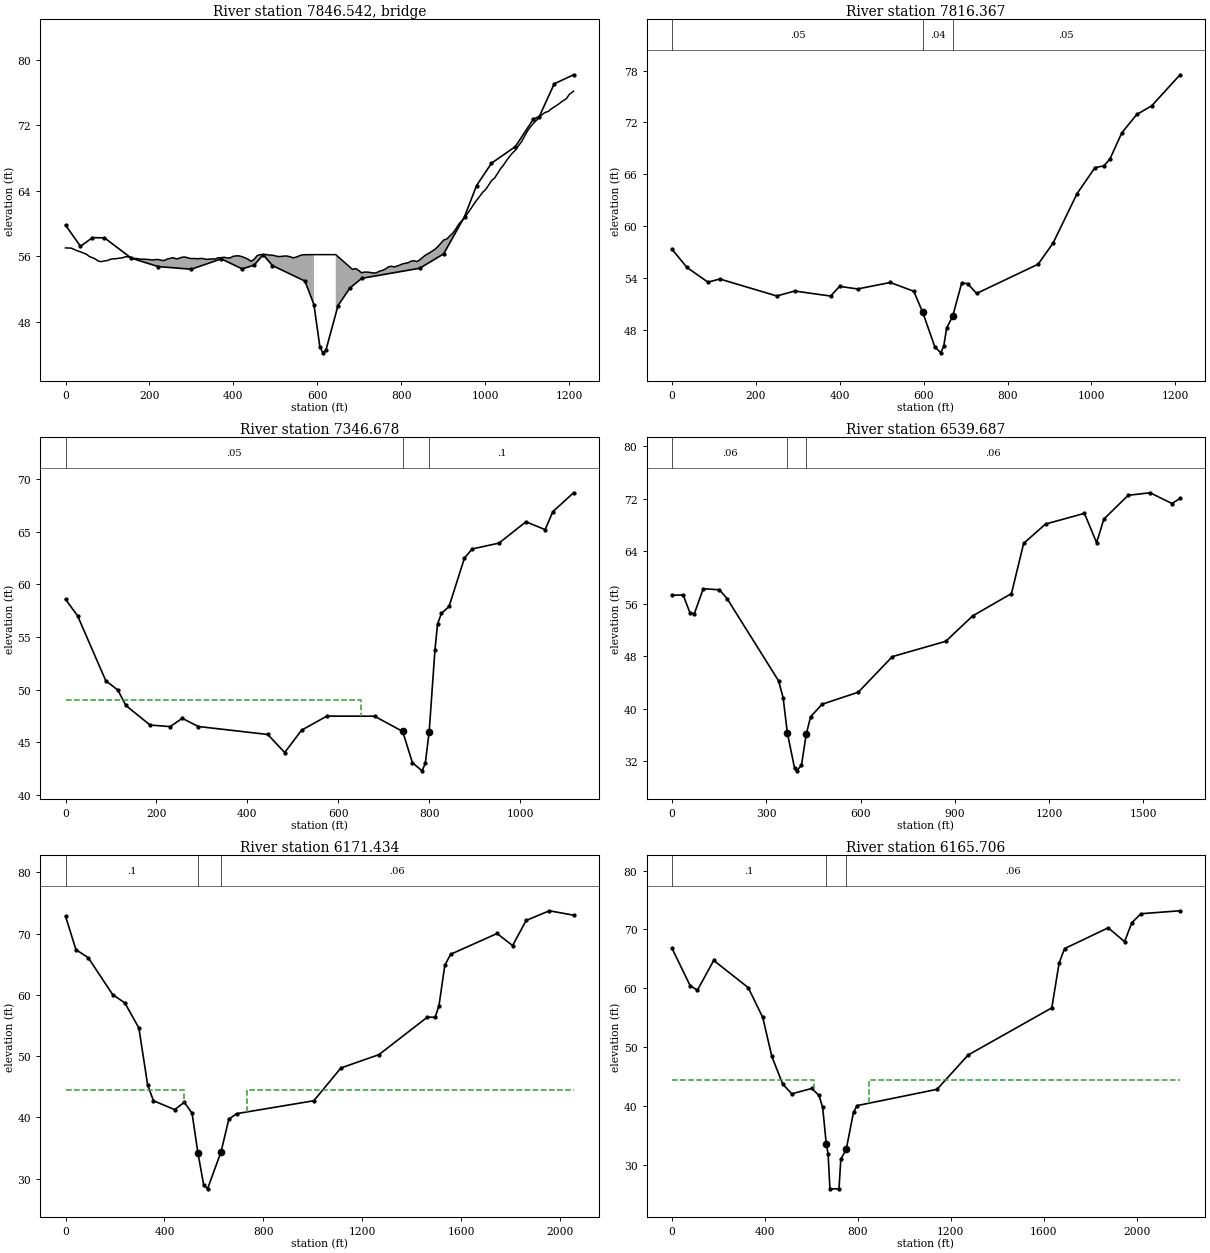
Type RM Length L Ch R = 3 ,7846.542,,,
BEGIN DESCRIPTION:
Razor Strap Road, MDE Bridge #: CE041007FS-5
Top of road obtained from DEM.
Openings from MDE2 bridge/culvert surveys.
END DESCRIPTION:
Bridge Culvert--1,0,-1,-1, 0
Deck Dist Width WeirC Skew NumUp NumDn MinLoCord MaxHiCord MaxSubmerge Is_Ogee
21,18,2.6,0, 159, 159, , , 0.95, 0, 2,2,,
       0    7.14   14.27   21.41   28.55   35.69   42.82   49.96    57.1   64.24
   71.37   78.51   85.65   92.78   99.92  107.06   114.2  121.33  128.47  135.61
  142.74  149.88  157.02  164.16  171.29  178.43  185.57  192.71  199.84  206.98
  214.12  221.25  228.39  235.53  242.67   249.8  256.94  264.08  271.21  278.35
  285.49  292.63  299.76   306.9  314.04  321.18  328.31  335.45  342.59  349.72
  356.86     364  371.14  378.27  385.41  392.55  399.69  406.82  413.96   421.1
  428.23  435.37  442.51  449.65  456.78  463.92  471.06  477.84  485.05  492.26
  499.47  506.68  513.89   521.1  528.31  535.52  542.73  549.94  555.78  562.91
  570.03     592     592     644     644  684.06  691.19  698.31  705.44  712.57
   719.7  726.82  733.95  741.08   748.2  755.33  762.46  769.58  776.71  783.84
   794.5  801.62  808.75  815.87  822.99  830.12  837.24  844.36  851.49  858.61
  865.73  872.85  879.98   887.1  894.22  901.35  908.47  915.59  922.71  929.84
  936.96  944.08  951.21  958.33  965.45  972.58   979.7  986.82  993.94 1001.07
 1008.19 1015.31 1022.44 1029.56 1036.68 1043.81 1050.93 1058.05 1065.17  1072.3
 1079.42 1086.54 1093.67 1100.79 1107.91 1115.03 1122.16 1129.28  1136.4 1143.53
 1150.65 1157.77  1164.9 1172.02 1179.14 1186.26 1193.39 1200.51 1210.63
   57.02   57.01   56.99   56.81   56.66   56.54    56.4   56.25   55.96   55.83
   55.65    55.4   55.35   55.43   55.48   55.64   55.69   55.71   55.77   55.81
   55.94   55.92   55.85   55.73   55.72   55.64   55.65   55.63    55.6   55.54
    55.6    55.6   55.51   55.48   55.67   55.75   55.83   55.67   55.77   55.89
    55.9   55.79   55.72   55.73   55.69   55.74   55.71   55.62   55.65   55.68
   55.66   55.82   55.83   55.88   55.79   55.81      56   56.05   56.05   55.94
    55.8   55.62   55.38   55.65   56.08   56.21   56.17   56.23   56.14   56.14
   56.06   55.97   55.98   56.03   56.03   55.93   55.81    55.9   56.03   56.16
   56.19    56.2    56.2    56.2    56.2   54.39   54.51   54.28   53.99   54.07
   54.07   54.02   53.95      54   54.18   54.28   54.45   54.71   54.78    54.7
   54.88   55.04   55.14    55.2   55.39   55.46   55.35   55.57   55.89   56.17
   56.36    56.6   56.84   57.17   57.59   57.99    58.1   58.47   58.81   59.31
   59.91    60.3    60.7   61.23   61.77   62.33   62.83    63.3    63.8   64.14
   64.67   65.24   65.54    66.1   66.69   67.13   67.68   68.16   68.61   68.94
   69.48   69.97   70.62   71.28   71.78   72.22   72.59   72.95   73.32   73.56
   73.67   73.99   74.23   74.46   74.73   74.99   75.22   75.74   76.14
                                                                                
                                                                                
                                                                                
                                                                                
                                                                                
                                                                                
                                                                                
                                                                                
                   56.19   56.19
                                                                                
                                                                                
                                                                                
                                                                                
                                                                                
                                                                                
                                                                        
       0    7.14   14.27   21.41   28.55   35.69   42.82   49.96    57.1   64.24
   71.37   78.51   85.65   92.78   99.92  107.06   114.2  121.33  128.47  135.61
  142.74  149.88  157.02  164.16  171.29  178.43  185.57  192.71  199.84  206.98
  214.12  221.25  228.39  235.53  242.67   249.8  256.94  264.08  271.21  278.35
  285.49  292.63  299.76   306.9  314.04  321.18  328.31  335.45  342.59  349.72
  356.86     364  371.14  378.27  385.41  392.55  399.69  406.82  413.96   421.1
  428.23  435.37  442.51  449.65  456.78  463.92  471.06  477.84  485.05  492.26
  499.47  506.68  513.89   521.1  528.31  535.52  542.73  549.94  555.78  562.91
  570.03     608     608     660     660  684.06  691.19  698.31  705.44  712.57
   719.7  726.82  733.95  741.08   748.2  755.33  762.46  769.58  776.71  783.84
   794.5  801.62  808.75  815.87  822.99  830.12  837.24  844.36  851.49  858.61
  865.73  872.85  879.98   887.1  894.22  901.35  908.47  915.59  922.71  929.84
  936.96  944.08  951.21  958.33  965.45  972.58   979.7  986.82  993.94 1001.07
 1008.19 1015.31 1022.44 1029.56 1036.68 1043.81 1050.93 1058.05 1065.17  1072.3
 1079.42 1086.54 1093.67 1100.79 1107.91 1115.03 1122.16 1129.28  1136.4 1143.53
 1150.65 1157.77  1164.9 1172.02 1179.14 1186.26 1193.39 1200.51 1211.25
   57.02   57.01   56.99   56.81   56.66   56.54    56.4   56.25   55.96   55.83
   55.65    55.4   55.35   55.43   55.48   55.64   55.69   55.71   55.77   55.81
   55.94   55.92   55.85   55.73   55.72   55.64   55.65   55.63    55.6   55.54
    55.6    55.6   55.51   55.48   55.67   55.75   55.83   55.67   55.77   55.89
    55.9   55.79   55.72   55.73   55.69   55.74   55.71   55.62   55.65   55.68
   55.66   55.82   55.83   55.88   55.79   55.81      56   56.05   56.05   55.94
    55.8   55.62   55.38   55.65   56.08   56.21   56.17   56.23   56.14   56.14
   56.06   55.97   55.98   56.03   56.03   55.93   55.81    55.9   56.03   56.16
   56.19    56.2    56.2    56.2    56.2   54.39   54.51   54.28   53.99   54.07
   54.07   54.02   53.95      54   54.18   54.28   54.45   54.71   54.78    54.7
   54.88   55.04   55.14    55.2   55.39   55.46   55.35   55.57   55.89   56.17
   56.36    56.6   56.84   57.17   57.59   57.99    58.1   58.47   58.81   59.31
   59.91    60.3    60.7   61.23   61.77   62.33   62.83    63.3    63.8   64.14
   64.67   65.24   65.54    66.1   66.69   67.13   67.68   68.16   68.61   68.94
   69.48   69.97   70.62   71.28   71.78   72.22   72.59   72.95   73.32   73.56
   73.67   73.99   74.23   74.46   74.73   74.99   75.22   75.74   76.14
                                                                                
                                                                                
                                                                                
                                                                                
                                                                                
                                                                                
                                                                                
                                                                                
                   56.19   56.19
                                                                                
                                                                                
                                                                                
                                                                                
                                                                                
                                                                                
                                                                        
BR Coef=-1 , 0 , 0 ,, 0 ,,,0.8,-1,,0,
WSPro=,,,, 1 ,,,, 0 ,,,, 0 ,,,,-1 ,-1 ,-1 , 0 , 0 , 0 , 0 , 0
BC Design=,, 0 ,, 0 ,,,,,,
BC Use User HTab Curves=0
BC User HTab FreeFlow(D)= 0

Type RM Length L Ch R = 1 ,7816.367,429.73,469.69,512.7
BEGIN DESCRIPTION:
Channel bottom center lowered approx. 1 ft based on bridge survey info.
END DESCRIPTION:
XS GIS Cut Line= 5
1606356.68791571708342.3379688261605888.70894362708249.218953818
1605812.93311512708230.5088727331605577.63344809708185.511326849
1605168.34363732708108.458668306
#Sta/Elev= 30
       0   57.33   35.69   55.22   85.65   53.52   114.2   53.88   249.8   51.92
  292.63   52.49  378.27   51.91  399.69   53.03  442.51   52.73  520.42   53.48
  576.59   52.46  597.97   50.01  626.47   46.06  640.73   45.34  647.85    46.1
  654.98   48.22  669.23   49.57  690.61    53.4  704.87   53.35  726.25   52.21
  873.12    55.6  908.74   58.05  965.72   63.75 1008.46   66.77 1029.83   66.97
 1044.07   67.76 1072.56    70.8 1108.18   72.92 1143.79   73.92 1211.25   77.51
#Mann= 3 , 0 , 0
       0     .05       0  597.97     .04       0  669.23     .05       0
#XS Ineff= 2 , 0
       0  520.41    52.6               0
Permanent Ineff=
       F       F
Bank Sta=597.97,669.23
XS Rating Curve= 0 ,0
Exp/Cntr=0.5,0.3

Type RM Length L Ch R = 1 ,7346.678,787.16,806.99,816.47
XS GIS Cut Line= 6
  1606394.325874708308.2094712411606042.57471937 708035.49296695
1605871.92340094707886.8611734961605836.14167286707834.564801723
1605822.37946981707751.9915831091605574.65981403707584.092705339
#Sta/Elev= 30
       0   58.59   26.57   57.02   88.57   50.84  115.15   49.95  132.86   48.48
  186.01   46.62  230.29   46.47  256.87   47.26   292.3   46.48  445.09   45.72
  482.22      44  519.35   46.13  575.05   47.47  679.87   47.46  741.85   46.01
  763.14   43.04  784.43   42.26  791.53   42.97  800.12   45.99  812.82   53.77
  818.47   56.22  826.93   57.24  843.84   57.91  877.66   62.51  894.58   63.38
  953.77   63.94 1012.97   65.97 1055.25   65.22 1072.16   66.93 1117.73   68.73
#Mann= 3 , 0 , 0
       0     .05       0  741.85     .04       0  800.12      .1       0
#XS Ineff= 2 , 0
       0  649.35      49               0
Permanent Ineff=
       F       F
Bank Sta=741.85,800.12
XS Rating Curve= 0 ,0
Exp/Cntr=0.3,0.1

Type RM Length L Ch R = 1 ,6539.687,414.03,368.25,300.4
XS GIS Cut Line= 5
1606446.98761946708457.3398472071606470.84662779708324.624113381
1606532.50914969708217.1540478471606601.32016517707985.949035808
1605591.17445774707509.776808575
#Sta/Elev= 30
       0    57.3   35.56   57.31    56.9   54.65   71.12   54.46   99.57   58.28
  150.98   58.11   175.2   56.78  339.08   44.24  353.69   41.66  367.32   36.25
  390.21   30.89  397.51    30.5  412.12   31.38   427.3   36.09  441.33   38.76
  477.85   40.66  592.84   42.49  701.18   47.92  871.44   50.26  956.56   54.12
 1080.38   57.54 1119.08   65.19 1188.72   68.14 1312.54   69.77 1351.24   65.31
 1374.46    68.9 1451.84   72.53 1521.49   72.91 1591.14   71.27 1616.73   72.04
#Mann= 3 , 0 , 0
       0     .06       0  367.32     .04       0   427.3     .06       0
Bank Sta=367.32,427.3
XS Rating Curve= 0 ,0
Exp/Cntr=0.3,0.1

Type RM Length L Ch R = 1 ,6171.434,5.2,5.73,5.77
XS GIS Cut Line= 4
1607073.28658813708566.1965727211607119.25037839708221.688972995
1606421.66281904707875.9547878651605592.34065004707460.548487693
#Sta/Elev= 30
       0   72.84   42.37   67.38   91.81   66.08  190.67   60.05  240.11   58.68
  296.61   54.59  331.92   45.32  355.37   42.71  441.31   41.26  480.37   42.46
  511.62   40.66  535.06   34.23   558.5   28.96  574.12   28.32  628.81   34.38
  660.06   39.68  691.31    40.6 1003.82   42.71 1113.19   48.06 1267.05   50.24
 1462.77   56.37 1494.09   56.34 1509.75   58.26 1533.24   64.82 1556.72   66.63
 1744.62   70.03 1807.26   68.05 1862.06   72.16 1956.01   73.74 2053.67   73.02
#Mann= 3 , 0 , 0
       0      .1       0  535.06     .04       0  628.81     .06       0
#XS Ineff= 2 , 0
       0     477   44.46  731.64       0   44.46
Permanent Ineff=
       F       F
Bank Sta=535.06,628.81
XS Rating Curve= 0 ,0
Exp/Cntr=0.5,0.3

Type RM Length L Ch R = 1 ,6165.706,215.47,214.83,219.36
BEGIN DESCRIPTION:
Channel bottom center lowered to elevation 26.0 based on bridge survey info and photos.
END DESCRIPTION:
XS GIS Cut Line= 3
1607551.70637794708430.439838797 1606423.8926371707871.479519859
1605594.57993117707456.077959746
#Sta/Elev= 30
       0   66.82   78.13   60.47  109.38    59.7  179.69   64.75  328.13   60.13
  390.63   55.08  429.69   48.47  476.57   43.76  515.63   42.12  601.57   43.03
  632.82   41.84  648.44   39.81  664.07   33.59  671.88   31.95  679.69      26
  718.76      26  726.57   31.02  750.01   32.72  781.26   39.01  796.88   40.12
 1140.63   42.88 1274.39    48.7 1634.53    56.7 1665.84   64.28 1689.33   66.75
 1877.23   70.28 1947.69   67.93 1979.01   71.15 2018.15   72.67 2186.27   73.17
#Mann= 3 , 0 , 0
       0      .1       0  664.07     .04       0  750.01     .06       0
#XS Ineff= 2 , 0
       0  613.03   44.46  846.52       0   44.46
Permanent Ineff=
       F       F
Bank Sta=664.07,750.01
XS Rating Curve= 0 ,0
Exp/Cntr=0.5,0.3

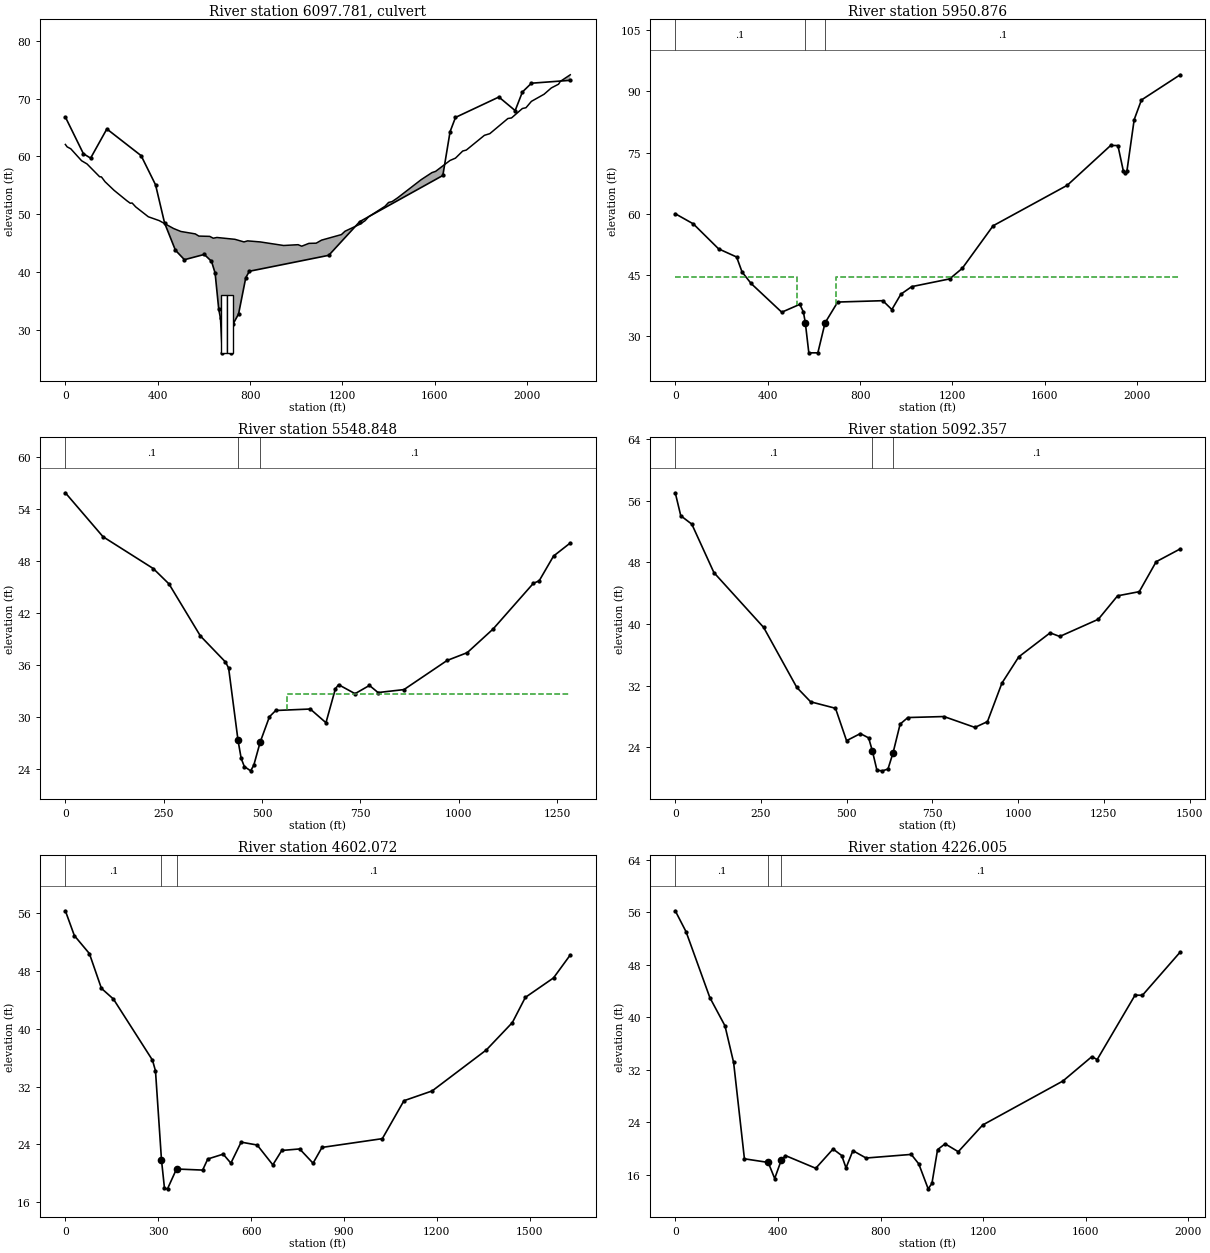
Type RM Length L Ch R = 2 ,6097.781,,,
BEGIN DESCRIPTION:
Pulaski Highway, MDE Bridge #: CE041007PF-5
Top of road obtained from DEM.
Openings from MDE2 bridge/culvert surveys.
END DESCRIPTION:
Bridge Culvert--1,0,-1,-1, 0
Deck Dist Width WeirC Skew NumUp NumDn MinLoCord MaxHiCord MaxSubmerge Is_Ogee
50,115,2.6,0, 60, 60, , , 0.95, 0, 2,2,,
       0    7.81   23.44   70.31   93.75  148.44  156.25  171.88  210.94  265.63
  281.25  289.06  304.69  359.38  406.25  468.75     500   562.5  578.13     625
  640.63  656.26  734.38  773.44  789.07  843.76  945.32 1007.82 1023.45  1054.7
 1085.95 1109.38 1195.32 1210.95 1274.26 1297.75 1313.41 1383.87 1399.53 1415.18
 1438.67 1540.45 1587.42 1603.08 1665.71  1689.2 1720.52 1736.18 1814.47 1837.96
 1916.25  1931.9 1978.88 1994.54 2018.02 2072.83 2104.14 2135.46 2143.29 2186.27
   62.07   61.65   61.32   59.25    58.7   56.48   56.45   55.62   54.13   52.35
   51.89   51.94   51.26   49.55   48.89   47.52   47.01   46.59   46.21   46.16
   45.84   45.97   45.65    45.2   45.38    45.2   44.58   44.72   44.46   44.95
   44.98   45.51   46.47   47.05   48.24   48.87   49.56   51.36   52.03   52.19
   52.83   55.97    57.2   57.41    59.3    59.7   60.93    61.1   63.65   63.94
   66.56   66.66   68.29   68.43   69.53   70.76   71.85    72.5   72.99   74.13
                                                                                
                                                                                
                                                                                
                                                                                
                                                                                
                                                                                
       0    7.81   23.44   70.31   93.75  148.44  156.25  171.88  210.94  265.63
  281.25  289.06  304.69  359.38  406.25  468.75     500   562.5  578.13     625
  640.63  656.26  734.38  773.44  789.07  843.76  945.32 1007.82 1023.45  1054.7
 1085.95 1109.38 1195.32 1210.95 1274.26 1297.75 1313.41 1383.87 1399.53 1415.18
 1438.67 1540.45 1587.42 1603.08 1665.71  1689.2 1720.52 1736.18 1814.47 1837.96
 1916.25  1931.9 1978.88 1994.54 2018.02 2072.83 2104.14 2135.46 2143.29 2185.46
   62.07   61.65   61.32   59.25    58.7   56.48   56.45   55.62   54.13   52.35
   51.89   51.94   51.26   49.55   48.89   47.52   47.01   46.59   46.21   46.16
   45.84   45.97   45.65    45.2   45.38    45.2   44.58   44.72   44.46   44.95
   44.98   45.51   46.47   47.05   48.24   48.87   49.56   51.36   52.03   52.19
   52.83   55.97    57.2   57.41    59.3    59.7   60.93    61.1   63.65   63.94
   66.56   66.66   68.29   68.43   69.53   70.76   71.85    72.5   72.99   74.13
                                                                                
                                                                                
                                                                                
                                                                                
                                                                                
                                                                                
BR Coef=-1 , 1 , 0 ,, 0 ,,,0.8,0,0.5,0,
WSPro=,,,, 1 ,,,, 0 ,,,, 0 ,,,,-1 ,-1 ,-1 , 0 , 0 , 0 , 0 , 0
Multiple Barrel Culv=2,10,24,150,0.015,0.4,1,8,1,26,26, 2,Culvert #1  , 0 ,32.4
     687     586     713     612
Culvert Bottom n=0.015
BC Design=,, 0 ,, 0 ,,,,,,
BC Use User HTab Curves=0
BC User HTab FreeFlow(D)= 0

Type RM Length L Ch R = 1 ,5950.876,397.62,402.03,402.7
BEGIN DESCRIPTION:
Channel bottom center lowered to elevation 26.0 based on bridge survey info and photos.
END DESCRIPTION:
XS GIS Cut Line= 3
1607636.07910715708260.2010577621606508.62572262707701.419336483
1605679.67261359707286.197897941
#Sta/Elev= 30
       0   60.04   78.13   57.56   187.5   51.45  265.63   49.45  289.06    45.8
  328.13   42.98  460.94   35.94  539.07   37.87  554.69      36  562.98   33.36
  578.13      26  617.19      26  648.44   33.34  703.13   38.43  898.44   38.76
  937.51   36.59  976.57   40.35 1023.45    42.2 1187.51   44.09  1242.2   46.67
 1375.76   57.09 1696.76      67 1884.65   76.75 1915.97   76.72 1939.46    70.5
 1947.29   69.91 1955.12   70.54 1986.43   83.07 2017.75   87.87 2185.46   94.04
#Mann= 3 , 0 , 0
       0      .1       0  562.98     .04       0  648.44      .1       0
#XS Ineff= 2 , 0
       0   527.6   44.46  696.34       0   44.46
Permanent Ineff=
       F       F
Bank Sta=562.98,648.44
XS Rating Curve= 0 ,0
Exp/Cntr=0.5,0.3

Type RM Length L Ch R = 1 ,5548.848,432.81,456.49,426.59
XS GIS Cut Line= 3
1607820.65135971707969.4343920651607206.85710153707633.636636466
1606648.11165574707465.737758681
#Sta/Elev= 30
       0   55.82   95.75   50.75  223.41   47.08  263.31   45.31   343.1   39.31
  406.93    36.3  414.91    35.6  438.85   27.25  446.83   25.18  454.81   24.25
  470.77   23.75  478.75   24.38  495.14   27.07  518.64   29.99   534.6   30.71
  622.37   30.88  662.26    29.3   686.2   33.21  694.18   33.69  736.19   32.65
  772.74    33.6  794.66   32.78  860.45   33.12  970.09   36.48 1021.25   37.38
 1087.03   40.11 1189.36   45.38 1203.98   45.66 1240.53   48.52 1283.07   50.03
#Mann= 3 , 0 , 0
       0      .1       0  438.85     .04       0  495.14      .1       0
#XS Ineff= 2 , 0
                          562.12           32.59
Permanent Ineff=
       F       F
Bank Sta=438.85,495.14
XS Rating Curve= 0 ,0
Exp/Cntr=0.3,0.1

Type RM Length L Ch R = 1 ,5092.357,422.05,490.29,396.67
XS GIS Cut Line= 4
1608054.60881242707633.6366364661607484.85360412707308.848643348
1607267.41079517707223.5229841321606686.64582442707171.226612344
#Sta/Elev= 30
       0   57.02   16.11   54.04   48.34   52.95   112.8   46.67  257.84   39.56
  354.53   31.78  394.82   29.92  467.33   29.08  499.56   24.88  539.85    25.8
  564.02   25.24  575.17    23.5   588.2   21.04  604.31   20.97  620.43   21.21
  635.25   23.32  655.83   27.03  678.39   27.88  783.66   28.01   873.9    26.6
   910.5   27.35  952.67   32.34 1001.86   35.75 1093.23   38.86 1121.35   38.39
  1233.8   40.62 1290.03   43.66 1353.28    44.2 1402.48   48.08 1472.53   49.74
#Mann= 3 , 0 , 0
       0      .1       0  575.17     .04       0  635.25      .1       0
#XS Ineff= 2 , 0
                          678.42           27.87
Permanent Ineff=
       F       F
Bank Sta=575.17,635.25
XS Rating Curve= 0 ,0
Exp/Cntr=0.3,0.1

Type RM Length L Ch R = 1 ,4602.072,370.18,376.07,473.52
XS GIS Cut Line= 5
1608181.22108088 707416.193827511607903.22457829707149.207087412
1607729.82081926707039.1094626041607303.19252324706931.764278427
1606703.16046812706915.249634713
#Sta/Elev= 30
       0   56.27   29.12   52.84   77.64   50.36  116.47   45.56  155.29   44.08
  281.46   35.64  291.16   34.16  310.57   21.85  320.28   17.92  329.99   17.87
   359.1   20.61  443.48   20.46  460.07   21.99  509.82   22.66  534.69   21.42
  567.86   24.32  619.72   23.92  670.24   21.18  699.12   23.17  756.86   23.38
  800.17   21.41  829.04   23.59 1023.93    24.8 1093.79   30.04 1184.83   31.39
  1359.9   37.05 1443.93   40.83 1485.94   44.31 1576.98      47 1631.03   50.17
#Mann= 3 , 0 , 0
       0      .1       0  310.57     .04       0   359.1      .1       0
Bank Sta=310.57,359.1
XS Rating Curve= 0 ,0
Exp/Cntr=0.3,0.1

Type RM Length L Ch R = 1 ,4226.005,829.42,824,454.84
XS GIS Cut Line= 5
1608417.93097422 707096.910715641607842.67088467706711.569028854
1607349.98401377706557.4323541521606912.34595524706598.718963459
1606601.32016517706673.034860194
#Sta/Elev= 30
       0   56.21   42.13   53.02  134.81      43  193.78    38.7  227.48   33.12
  269.61   18.46  362.29   17.91  387.57   15.46  412.84   18.21  429.69   18.95
  547.65   17.02  615.05   19.95  648.75   18.96   665.6   17.08   692.4    19.7
  743.74   18.58  919.77   19.13  949.11   17.69  985.78   13.89 1000.45   14.71
 1022.45   19.86 1051.79   20.74 1103.13   19.54 1198.48   23.61 1510.97    30.3
 1623.47      34 1644.56   33.57 1792.16   43.37 1820.95   43.35    1968   49.92
#Mann= 3 , 0 , 0
       0      .1       0  362.29     .04       0  412.84      .1       0
Bank Sta=362.29,412.84
XS Rating Curve= 0 ,0
Exp/Cntr=0.3,0.1

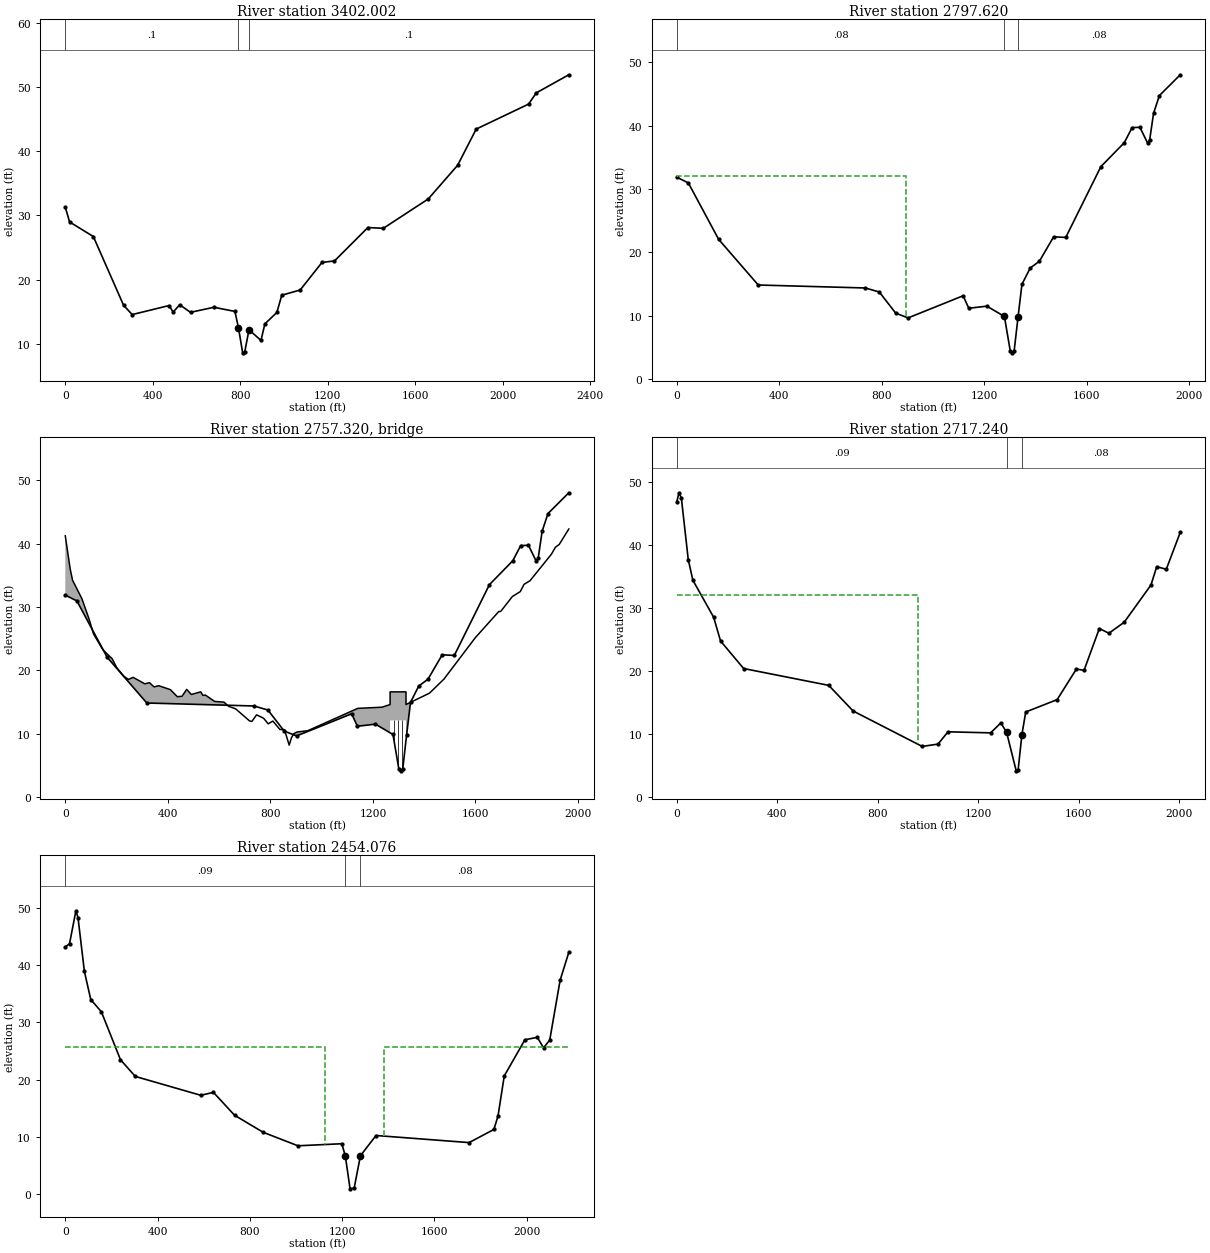
Type RM Length L Ch R = 1 ,3402.002,360.29,604.38,636.84
XS GIS Cut Line= 6
1608302.32846816706697.8068257571607845.42332532706243.654123515
 1607707.8012943706249.1590047481607482.10116348706386.781035721
1606681.14094315706518.8981854921606246.25532523706472.106694937
#Sta/Elev= 30
       0   31.29   19.74   28.98  128.31   26.71  266.48      16  305.96   14.55
  473.75   15.95  493.49   14.95   523.1   16.08  572.44    14.9  679.23   15.69
  775.46   15.04  791.64    12.5   810.9    8.59  820.53    8.76  839.78   12.19
   894.6   10.52  912.38    13.1  967.44   14.89  989.58   17.57  1073.8   18.38
 1173.64   22.68  1230.7   22.91  1383.3   28.11 1454.03   27.99 1659.14   32.56
 1793.52   37.81 1878.51   43.45 2117.88   47.34 2153.08   49.09 2301.82   51.91
#Mann= 3 , 0 , 0
       0      .1       0  791.64     .04       0  839.78      .1       0
Bank Sta=791.64,839.78
XS Rating Curve= 0 ,0
Exp/Cntr=0.5,0.3

Type RM Length L Ch R = 1 ,2797.620,80.77,80.38,82.07
BEGIN DESCRIPTION:
Channel bottom center lowered approx. 1 ft based on bridge survey info.
END DESCRIPTION:
XS GIS Cut Line= 6
1608302.54354461706625.7825558191607727.51311894 705930.55942452
1607598.38806528705927.6179343311607479.94202495705896.877998948
 1607403.5108633705857.6548786911606735.30506273705579.696516618
#Sta/Elev= 30
       0   31.87   45.42   30.95  163.51   22.05  317.95   14.84  735.82   14.37
  790.32   13.73  853.91   10.41  902.22    9.64 1117.12   13.14  1139.2   11.17
 1209.86    11.5 1278.14    9.87 1300.94    4.45 1308.54    4.13 1316.14    4.42
 1331.34    9.79 1346.54   14.94 1378.57   17.51 1414.73    18.6 1470.17   22.45
 1517.45   22.35 1654.45   33.53 1745.79   37.31 1776.24   39.69 1806.69   39.74
 1837.13   37.21 1844.74   37.74 1859.97   41.96  1882.8   44.75 1963.99   48.03
#Mann= 3 , 0 , 0
       0     .08       0 1278.14     .04       0 1331.34     .08       0
#XS Ineff= 2 , 0
       0  896.25      32               0
Permanent Ineff=
       F       F
Bank Sta=1278.14,1331.34
XS Rating Curve= 0 ,0
Exp/Cntr=0.5,0.3

Type RM Length L Ch R = 3 ,2757.320,,,
BEGIN DESCRIPTION:
West Old Philadelphia Road
MDE Bridge #: CE041007PF-4
Top of road obtained from DEM.
Openings from MDE2 bridge/culvert surveys.
END DESCRIPTION:
Bridge Culvert--1,0,-1,-1, 0
Deck Dist Width WeirC Skew NumUp NumDn MinLoCord MaxHiCord MaxSubmerge Is_Ogee
28,24,2.6,0, 60, 60, , , 0.95, 0, 2,2,,
       0   19.34   28.42   64.76   92.01  110.18  146.51  182.85  201.02  228.27
  246.44  264.61  310.03   328.2  346.37  364.53  409.96  437.21  455.38  473.54
  491.71  528.05  537.13  546.22  582.55  618.89  637.06  664.31  718.82   727.9
  746.07  773.32  791.49  809.66  836.91  855.08  873.25  882.33  891.42  904.04
  946.04 1140.49 1235.56    1267    1267    1329    1329 1420.47 1476.65 1599.45
 1690.78  1698.4 1744.07 1774.51 1789.73 1812.57  1896.3 1911.52 1926.74 1963.99
   41.24   35.96   34.22   31.32   28.19   25.74   23.25   21.83    20.4   19.06
   18.56   18.89   17.87   18.05   17.38   17.57   16.95   15.83   15.91   16.99
   16.19    16.6   16.04    16.1   15.09   14.98   14.32   13.92   12.01   11.93
   12.97   12.44   11.55   11.99   10.67   10.63    8.19    9.36      10   10.26
   10.47   13.99   14.18    14.6    16.6    16.6    14.6   16.39    18.6   25.16
   29.28    29.3   31.66   32.42   33.59   34.14   38.34   39.42   39.88   42.31
                                                                                
                                                                                
                                                                                
                                                                                
                                    12.1    12.1
                                                                                
       0   34.08   52.25   61.34   70.42  106.76  152.18  188.51  224.85  243.02
  270.27  288.44  306.61  352.03   370.2  388.37  406.53  451.96  479.21  497.38
  515.54  533.71  570.05  579.13  588.22  624.55  660.89  706.31  760.82   769.9
  788.07  815.32  833.49  851.66  878.91  897.08  915.25  924.33  933.42  946.04
  988.04 1182.49 1277.56    1308    1308    1370    1370 1462.47 1485.03 1540.88
 1641.45 1732.78  1740.4 1786.07 1816.51 1831.73 1854.57 1953.52 1968.74 2003.95
   44.85   43.84   38.36   35.96   34.22   31.32   25.74   23.25   21.83    20.4
   19.06   18.56   18.89   17.87   18.05   17.38   17.57   16.95   15.83   15.91
   16.99   16.19    16.6   16.04    16.1   15.09   14.98   13.92   12.01   11.93
   12.97   12.44   11.55   11.99   10.67   10.63    8.19    9.36      10   10.26
   10.47   13.99   14.18    14.6    16.6    16.6    14.6   16.39   17.14   19.66
   25.16   29.28    29.3   31.66   32.42   33.59   34.14   39.42   39.88   41.97
                                                                                
                                                                                
                                                                                
                                                                                
                                    12.1    12.1
                                                                                
Pier Skew, UpSta & Num, DnSta & Num=  ,1282.5, 2 ,1323.5, 2 , 0 , 0 , 0 ,,
       2       2
       2      13
       2       2
       2      13
Pier Skew, UpSta & Num, DnSta & Num=  ,1298, 2 ,1339, 2 , 0 , 0 , 0 ,,
       2       2
       2      13
       2       2
       2      13
Pier Skew, UpSta & Num, DnSta & Num=  ,1313.5, 2 ,1354.5, 2 , 0 , 0 , 0 ,,
       2       2
       2      13
       2       2
       2      13
BR Coef=-1 , 1 , 0 ,, 0 ,,,0.8,0,0.5,0,
WSPro=,,,, 1 ,,,, 0 ,,,, 0 ,,,,-1 ,-1 ,-1 , 0 , 0 , 0 , 0 , 0
BC Design=,, 0 ,, 0 ,,,,,,
BC Use User HTab Curves=0
BC User HTab FreeFlow(D)= 0

Type RM Length L Ch R = 1 ,2717.240,155.37,263.16,283.87
BEGIN DESCRIPTION:
Channel bottom center lowered approx. 1 ft based on bridge survey info.
END DESCRIPTION:
XS GIS Cut Line= 6
1608353.08562814706585.2752907131607949.19332533706100.369706213
1607753.11770159705850.2852279991607608.76340547705848.147331789
1607507.71254568705821.782382593 1606766.7225744705506.123831734
#Sta/Elev= 30
       0   46.78    9.18   48.25   18.37   47.46   45.92   37.66   64.29   34.39
  146.94   28.52  174.49   24.75  266.33   20.39  604.94   17.72  702.27   13.65
  976.89    8.04 1039.89    8.41 1079.73   10.36  1249.3   10.19 1290.24   11.77
 1313.04   10.25 1351.04    4.17 1358.64    4.28 1373.84    9.92 1389.03    13.5
 1514.11   15.46 1590.64   20.31 1621.09    20.1 1681.98   26.73 1720.04   25.98
 1780.93   27.73 1887.49   33.63 1910.33   36.54 1948.39   36.12 2003.95   41.97
#Mann= 3 , 0 , 0
       0     .09       0 1313.04     .04       0 1373.84     .08       0
#XS Ineff= 2 , 0
       0  959.69      32               0
Permanent Ineff=
       F       F
Bank Sta=1313.04,1373.84
XS Rating Curve= 0 ,0
Exp/Cntr=0.5,0.3

Type RM Length L Ch R = 1 ,2454.076,160.1,172.6,165.13
BEGIN DESCRIPTION:
Channel bottom center lowered approx. 2 ft based on bridge survey info.
END DESCRIPTION:
XS GIS Cut Line= 6
1608380.84426206706607.1586400871608164.25345743706353.519408271
1607954.40288177706099.4168403741607691.98497182705761.273372382
1607548.66635428705582.4212133291607009.49516582704908.932268441
#Sta/Elev= 30
       0   43.21   18.41   43.77   46.02   49.53   55.23   48.32   82.84   38.92
  110.46   34.01  156.48   31.86  239.33   23.47  303.76   20.55  587.73   17.25
   642.2   17.77  733.97   13.76  858.02   10.78 1008.65    8.42 1198.75    8.78
 1214.04    6.67 1234.63     .89 1252.57    1.03 1279.49    6.67  1347.2   10.22
 1750.71    8.98 1858.31   11.28 1876.24   13.66 1903.14   20.64 1992.81   26.97
 2046.61   27.39 2073.51   25.56 2100.41   26.93 2145.25   37.36 2183.02   42.26
#Mann= 3 , 0 , 0
       0     .09       0 1214.04     .04       0 1279.49     .08       0
#XS Ineff= 2 , 0
       0 1124.93   25.71 1380.31       0   25.71
Permanent Ineff=
       F       F
Bank Sta=1214.04,1279.49
XS Rating Curve= 0 ,0
Exp/Cntr=0.5,0.3