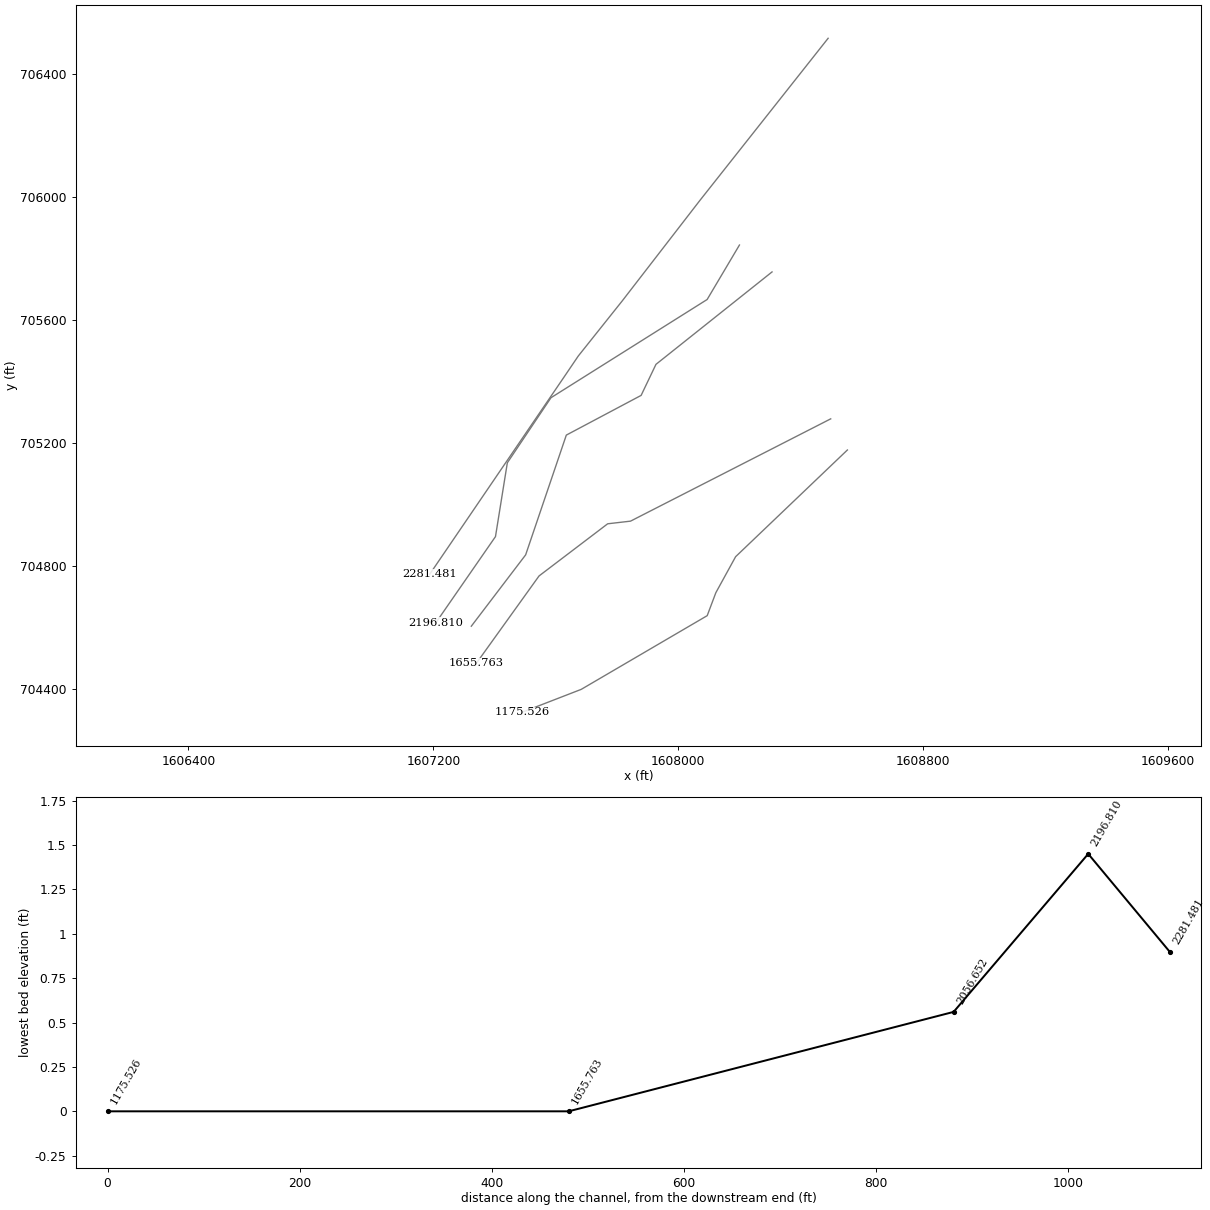
HEC-RAS study StonyRun.prj: StonyRun

--- StonyRun.g01 (geometry) --- (continued)

Type RM Length L Ch R = 3 ,2361.921,,,
BEGIN DESCRIPTION:
Railroad, MDE Bridge #: CE041007FS-3
Top of road obtained from DEM.
Openings approximated from MDE2 bridge/culvert surveys.
END DESCRIPTION:
Bridge Culvert--1,0,-1,-1, 0
Deck Dist Width WeirC Skew NumUp NumDn MinLoCord MaxHiCord MaxSubmerge Is_Ogee
51,70,2.6,0, 60, 60, , , 0.95, 0, 2,2,,
       0   36.82   55.23   82.84  101.25  119.66  128.87  156.48  174.89  202.51
  248.53  294.56  303.76  351.03  441.82  469.05  487.21  514.44   532.6  541.68
  587.07  605.23  614.31  678.28  713.72  722.58  873.21  882.07  899.79  917.51
   944.1 1068.15 1096.96 1132.84 1168.72 1186.66    1226    1226    1260    1260
 1362.62 1380.55 1398.49 1425.39 1434.35 1461.25 1479.19 1524.02 1658.52 1712.32
 1819.93 1855.79 1882.69 1900.63  2044.1 2062.03 2088.93 2106.86 2169.63 2183.02
   35.32   35.14   35.34    34.7   34.91   34.48   34.95   34.65   34.86   34.46
   34.78   34.06   34.35   33.91   33.72   33.25    33.5   32.79   33.17   32.89
   32.97   32.39   32.57      32   32.21   31.82   30.91   30.75   29.75   30.23
   30.53   30.06   29.49   29.72   29.33   29.54    29.1    29.1    29.1    29.1
   28.55   28.72   28.25   28.21    27.9   27.83    28.3   27.72   27.59   26.98
      27   26.65   26.83   26.41   26.21   25.86   26.11   25.71   25.47   25.54
                                                                                
                                                                                
                                                                                
                                                            22.1    22.1
                                                                                
                                                                                
       0   36.82   55.23   82.84  101.25  119.66  128.87  156.48  174.89  202.51
  248.53  294.56  303.76  351.03  441.82  469.05  487.21  514.44   532.6  541.68
  587.07  605.23  614.31  678.28  713.72  722.58  873.21  882.07  899.79  917.51
   944.1 1068.15 1096.96 1132.84 1168.72 1186.66    1245    1245    1279    1279
 1362.62 1380.55 1398.49 1425.39 1434.35 1461.25 1479.19 1524.02 1658.52 1712.32
 1819.93 1855.79 1882.69 1900.63  2044.1 2062.03 2088.93 2106.86 2169.63 2177.05
   35.32   35.14   35.34    34.7   34.91   34.48   34.95   34.65   34.86   34.46
   34.78   34.06   34.35   33.91   33.72   33.25    33.5   32.79   33.17   32.89
   32.97   32.39   32.57      32   32.21   31.82   30.91   30.75   29.75   30.23
   30.53   30.06   29.49   29.72   29.33   29.54    29.1    29.1    29.1    29.1
   28.55   28.72   28.25   28.21    27.9   27.83    28.3   27.72   27.59   26.98
      27   26.65   26.83   26.41   26.21   25.86   26.11   25.71   25.47   25.54
                                                                                
                                                                                
                                                                                
                                                            22.1    22.1
                                                                                
                                                                                
BR Coef=-1 , 0 , 0 ,, 0 ,,,0.8,-1,,0,
WSPro=,,,, 1 ,,,, 0 ,,,, 0 ,,,,-1 ,-1 ,-1 , 0 , 0 , 0 , 0 , 0
BC Design=,, 0 ,, 0 ,,,,,,
BC Use User HTab Curves=0
BC User HTab FreeFlow(D)= 0

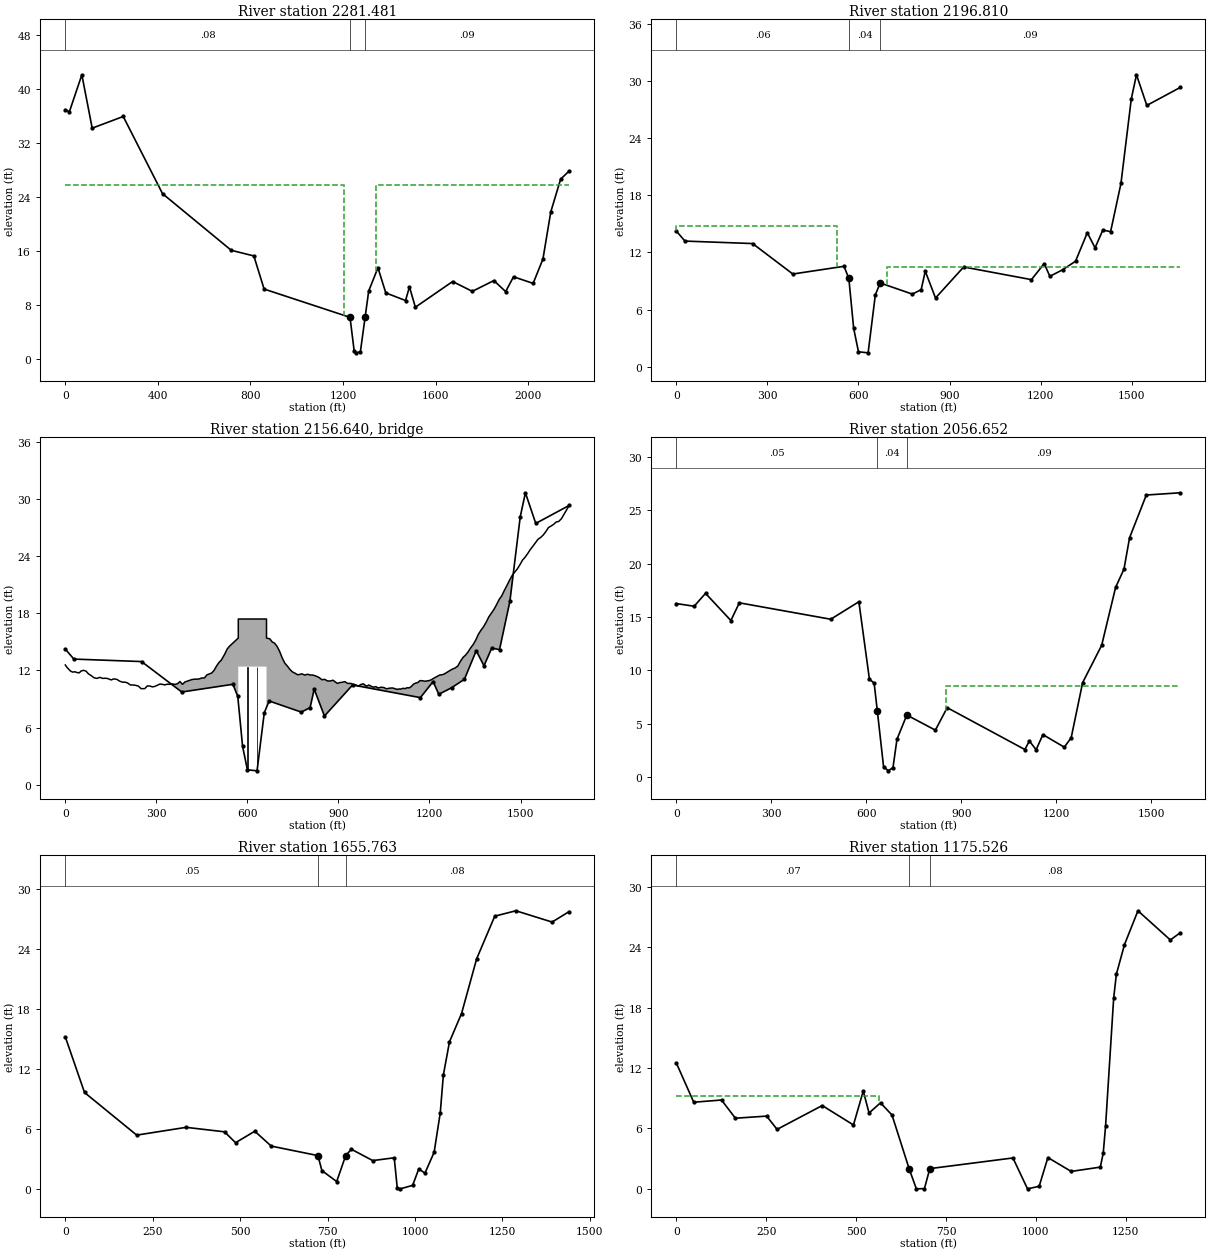
Type RM Length L Ch R = 1 ,2281.481,121.49,84.67,61.78
BEGIN DESCRIPTION:
Channel bottom center lowered approx. 2 ft based on bridge survey info.
END DESCRIPTION:
XS GIS Cut Line= 6
1608490.03345095706515.815133661   1608071.42545705989.008873463
1607817.61421148705662.1834430251607673.54782066705482.398112327
1607625.64048477705411.9672936651607188.05856402704772.561874762
#Sta/Elev= 30
       0   36.91   17.88   36.64   71.53    42.1  116.23   34.19  250.34   35.92
  420.22   24.48  717.19   16.09  814.68   15.26     859   10.35  1230.2    6.16
 1248.14    1.19 1257.11      .9 1275.05    1.06 1295.29    6.14 1310.93   10.06
 1350.93   13.51 1384.79    9.78 1470.11    8.65 1487.07   10.67 1512.52    7.66
 1673.68   11.47  1758.5   10.01 1851.81   11.61  1902.7    9.97 1936.63   12.17
 2021.45   11.19 2063.87   14.81 2097.79    21.8 2140.21   26.63 2177.05   27.84
#Mann= 3 , 0 , 0
       0     .08       0  1230.2     .04       0 1295.29     .09       0
#XS Ineff= 2 , 0
       0 1206.23   25.71 1343.38       0   25.71
Permanent Ineff=
       F       F
Bank Sta=1230.2,1295.29
XS Rating Curve= 0 ,0
Exp/Cntr=0.5,0.3

Type RM Length L Ch R = 1 ,2196.810,146.35,140.16,136.38
BEGIN DESCRIPTION:
Channel bottom center lowered 1 feet based on bridge survey info
END DESCRIPTION:
XS GIS Cut Line= 6
1608200.27294067 705843.489405991608094.74985392705666.347743601
1607584.47421376705346.9123388981607441.87328207705135.332351938
1607403.11697015704895.2317239051607208.80381568704615.906564429
#Sta/Elev= 30
       0   14.24   28.16   13.19   251.2   12.93  383.77    9.73  552.44   10.54
  568.31    9.26  584.18    4.02  600.05    1.56  631.79    1.45   655.6    7.54
  671.47    8.79  777.62    7.62  806.68    8.09   820.1   10.03  853.86    7.21
  946.72   10.47 1169.97    9.14 1212.06   10.83 1230.61    9.49  1272.9   10.18
 1315.18   11.07 1354.03   14.07 1379.61   12.48 1405.19   14.35 1430.77   14.18
 1464.88   19.24 1498.99   28.13 1516.05   30.66 1550.16   27.44 1660.19   29.33
#Mann= 3 , 0 , 0
       0     .06       0  568.31     .04       0  671.47     .09       0
#XS Ineff= 2 , 0
       0     530   14.79  692.64       0    10.5
Permanent Ineff=
       F       F
Bank Sta=568.31,671.47
XS Rating Curve= 0 ,0
Exp/Cntr=0.5,0.3

Type RM Length L Ch R = 3 ,2156.640,,,
BEGIN DESCRIPTION:
NE Isles Drive, MDE Bridge #: CE041007FS-4
Top of road obtained from DEM.
Openings from MDE2 bridge/culvert surveys.
END DESCRIPTION:
Bridge Culvert--1,0,-1,-1, 0
Deck Dist Width WeirC Skew NumUp NumDn MinLoCord MaxHiCord MaxSubmerge Is_Ogee
53.5,33,2.6,0, 190, 185, , , 0.95, 0, 2,2,,
       0    6.33   16.47   23.98   31.49      39   46.51   50.96   59.51   68.05
    76.6   85.14   94.57  104.21  113.85  123.49  133.14  141.31  150.79  160.27
  169.75  179.23  188.71  196.94  205.72  214.51   223.3  232.08  240.87  249.66
  261.95  270.28  278.61  286.94  295.27   303.6  311.93  320.26  327.84  336.17
  344.51  352.84  361.17  369.51  377.84  386.17  394.51  402.84  411.17  417.43
  425.73  434.02  442.32  450.62   458.5  466.47  474.44  482.41  490.38  498.35
  506.33   514.3  525.45  533.39  541.32     570     570     663     663  673.83
  681.75  689.67   697.6  705.52  715.22  723.54  731.86  740.18  748.49  756.81
  765.13  769.92   779.5  789.07  798.65  806.57  816.17  825.76  835.36  845.74
  854.85  863.97  873.08  882.19  887.59  896.06  904.52  912.99  921.45  929.92
  941.59  949.61  957.63  965.66  973.68   981.7  992.76 1000.36 1007.96 1015.56
 1023.17 1030.77 1038.37 1043.18 1050.43 1057.67 1064.92 1072.16 1079.41 1086.65
  1093.9 1098.64 1105.66 1112.67 1119.69  1126.7 1133.72 1140.74 1147.75 1154.77
 1161.79  1168.8 1177.41 1184.46  1191.5 1198.55  1205.6 1212.65  1219.7 1226.74
 1233.79 1240.84 1247.89 1254.94 1261.98 1269.03 1276.08 1284.77 1293.29 1301.82
 1310.35 1318.87  1327.4 1335.93 1344.46 1352.98 1361.51 1370.04 1378.56 1387.09
 1395.62 1404.15 1412.67  1421.2 1429.73 1438.26 1446.78 1455.31 1463.84 1472.36
 1480.89 1489.42 1497.95 1506.47    1515 1523.53 1532.05 1540.58 1549.11 1557.64
 1566.16 1574.69 1583.22 1591.75 1600.27  1608.8 1617.33 1625.85 1635.06 1660.19
   12.57   12.29   11.95   11.82   11.86   11.77   11.75   11.92   12.01   11.93
   11.63   11.46   11.23   11.16   11.27   11.16   11.18   11.13      11   11.11
   11.06   10.87   10.76   10.77   10.67   10.47   10.47   10.43   10.35   10.08
   10.09   10.37   10.36   10.27   10.32   10.45   10.57   10.53   10.48   10.55
   10.54   10.58   10.53    10.6   10.83   10.54   10.79   10.88   10.96   11.04
   11.08   11.08   11.12   11.21   11.21   11.53   11.63   11.73   12.01   12.46
   12.83   13.09   13.72   14.25   14.55    15.4    17.4    17.4    15.4   15.32
   14.99   14.86   14.53   14.05   13.28   12.75   12.45    12.1   11.84   11.71
   11.55   11.56   11.64   11.51    11.6   11.52   11.51   11.41   11.27   11.02
   11.06   10.89   10.89   10.97   10.84   10.64   10.72   10.76   10.82   10.64
   10.63   10.51   10.47   10.35   10.52   10.59   10.34   10.47   10.33   10.24
    10.3   10.15   10.22   10.23   10.19   10.07   10.11   10.15   10.15   10.07
      10   10.05   10.04   10.12   10.09   10.18   10.17   10.33   10.57   10.67
   10.73   10.93   10.91   10.86   10.89   10.93   11.01   11.15   11.27    11.4
   11.52   11.54   11.61   11.75    11.9   12.02   12.15   12.26   12.46   12.95
   13.36   13.61   13.96   14.38   14.74   15.22   15.82   16.24   16.61   17.08
   17.63   18.02   18.42   18.92   19.46   19.84   20.41   20.93   21.48   21.97
   22.33   22.66    23.1   23.58   23.89   24.27   24.69   25.04   25.41   25.78
   25.96   26.22   26.57      27   27.17   27.33   27.59   27.65   27.95   29.33
                                                                                
                                                                                
                                                                                
                                                                                
                                                                                
                                                                                
                                                    12.4    12.4
                                                                                
                                                                                
                                                                                
                                                                                
                                                                                
                                                                                
                                                                                
                                                                                
                                                                                
                                                                                
                                                                                
                                                                                
       0   12.04   19.08   26.12   33.16    40.2   47.24   54.29   61.33   71.47
   78.98   86.49      94  101.51  105.96  114.51  123.05   131.6  140.14  149.57
  159.21  168.85  178.49  188.14  196.31  205.79  215.27  224.75  234.23  243.71
  251.94  260.72  269.51   278.3  287.08  295.87  304.66  316.95  325.28  333.61
  341.94  350.27   358.6  366.93  375.26  382.84  391.17  399.51  407.84  416.17
  424.51  432.84  441.17  449.51  457.84  466.17  472.43  480.73  489.02  497.32
  505.62   513.5  521.47  529.44  537.41  545.38  553.35  561.33   569.3  580.45
  588.39  596.32  604.26     630     630     723     723  736.75  744.67   752.6
  760.52  770.22  778.54  786.86  795.18  803.49  811.81  820.13  824.92   834.5
  844.07  853.65  861.57  871.17  880.76  890.36  900.74  909.85  918.97  928.08
  937.19  942.59  951.06  959.52  967.99  976.45  984.92  996.59 1004.61 1012.63
 1020.66 1028.68  1036.7 1047.76 1055.36 1062.96 1070.56 1078.17 1085.77 1093.37
 1098.18 1105.43 1112.67 1119.92 1127.16 1134.41 1141.65  1148.9 1153.64 1160.66
 1167.67 1174.69  1181.7 1188.72 1195.74 1202.75 1209.77 1216.79  1223.8 1232.41
 1239.46  1246.5 1253.55  1260.6 1267.65  1274.7 1281.74 1288.79 1295.84 1302.89
 1309.94 1316.98 1324.03 1331.08 1339.77 1348.29 1356.82 1365.35 1373.87  1382.4
 1390.93 1399.46 1407.98 1416.51 1425.04 1433.56 1442.09 1450.62 1459.15 1467.67
  1476.2 1484.73 1493.26 1501.78 1510.31 1518.84 1527.36 1535.89 1544.42 1552.95
 1561.47    1570 1578.53 1587.05 1591.22
   13.71   13.53   13.21   13.08   12.97   12.78   12.68   12.57   12.29   11.95
   11.82   11.86   11.77   11.75   11.92   12.01   11.93   11.63   11.46   11.23
   11.16   11.27   11.16   11.18   11.13      11   11.11   11.06   10.87   10.76
   10.77   10.67   10.47   10.47   10.43   10.35   10.08   10.09   10.37   10.36
   10.27   10.32   10.45   10.57   10.53   10.48   10.55   10.54   10.58   10.53
    10.6   10.83   10.54   10.79   10.88   10.96   11.04   11.08   11.08   11.12
   11.21   11.21   11.53   11.63   11.73   12.01   12.46   12.83   13.09   13.72
   14.25   14.55    14.7    15.4    17.4    17.4    15.4   14.99   14.86   14.53
   14.05   13.28   12.75   12.45    12.1   11.84   11.71   11.55   11.56   11.64
   11.51    11.6   11.52   11.51   11.41   11.27   11.02   11.06   10.89   10.89
   10.97   10.84   10.64   10.72   10.76   10.82   10.64   10.63   10.51   10.47
   10.35   10.52   10.59   10.34   10.47   10.33   10.24    10.3   10.15   10.22
   10.23   10.19   10.07   10.11   10.15   10.15   10.07      10   10.05   10.04
   10.12   10.09   10.18   10.17   10.33   10.57   10.67   10.73   10.93   10.91
   10.86   10.89   10.93   11.01   11.15   11.27    11.4   11.52   11.54   11.61
   11.75    11.9   12.02   12.15   12.26   12.46   12.95   13.36   13.61   13.96
   14.38   14.74   15.22   15.82   16.24   16.61   17.08   17.63   18.02   18.42
   18.92   19.46   19.84   20.41   20.93   21.48   21.97   22.33   22.66    23.1
   23.58   23.89   24.27   24.69   25.04
                                                                                
                                                                                
                                                                                
                                                                                
                                                                                
                                                                                
                                                                                
                                    12.4    12.4
                                                                                
                                                                                
                                                                                
                                                                                
                                                                                
                                                                                
                                                                                
                                                                                
                                                                                
                                                                                
                                        
Pier Skew, UpSta & Num, DnSta & Num=  ,601, 2 ,661, 2 , 0 , 0 , 0 ,,
     1.5     1.5
       0      13
     1.5     1.5
       0      13
Pier Skew, UpSta & Num, DnSta & Num=  ,632, 2 ,692, 2 , 0 , 0 , 0 ,,
     1.5     1.5
       0      13
     1.5     1.5
       0      13
BR Coef= 1 , 1 , 0 ,, 0 ,,,0.8,0,0.5,0,
WSPro=,,,, 1 ,,,, 0 ,,,, 0 ,,,,-1 ,-1 ,-1 , 0 , 0 , 0 , 0 , 0
BC Design=,, 0 ,, 0 ,,,,,,
BC Use User HTab Curves=0
BC User HTab FreeFlow(D)= 0

Type RM Length L Ch R = 1 ,2056.652,352.98,400.89,436.31
BEGIN DESCRIPTION:
Channel bottom center lowered 1 feet based on bridge survey info
END DESCRIPTION:
XS GIS Cut Line= 6
1608306.78638662 705756.010315911607927.44914503705455.365374401
1607879.02311416705354.4778101591607634.57072808705225.325209111
1607501.70362382704835.9157298651607324.14151075704603.874332055
#Sta/Elev= 30
       0   16.26   56.19   16.01   92.08   17.22   172.1   14.67  198.88   16.33
  487.49   14.79  576.37   16.43  609.66    9.16  624.56     8.8  634.58     6.2
  654.35     .95  669.25     .56  684.15     .87  696.68    3.52  727.74     5.8
  817.94    4.38  855.31    6.49 1100.58    2.56 1114.82    3.36 1136.19    2.54
 1157.56    3.96 1225.17    2.78 1246.87    3.67 1283.03    8.84 1343.11   12.34
 1387.18   17.78 1413.62    19.5 1431.25   22.44 1484.14   26.45 1591.22   26.66
#Mann= 3 , 0 , 0
       0     .05       0  634.58     .04       0  727.74     .09       0
#XS Ineff= 2 , 0
       0                     850       0     8.5
Permanent Ineff=
       F       F
Bank Sta=634.58,727.74
XS Rating Curve= 0 ,0
Exp/Cntr=0.5,0.3

Type RM Length L Ch R = 1 ,1655.763,302.74,480.24,413.86
XS GIS Cut Line= 5
1608498.47275876705278.2068115621607844.38444343704945.526244178
1607769.66937144704936.9052743171607545.52415556  704767.3595341
1607340.28352103704482.809254959
#Sta/Elev= 30
       0   15.22   54.97    9.65  204.19    5.38  345.55    6.16   455.5    5.71
  486.91    4.62  541.88    5.77     589    4.28  722.51    3.33  733.83    1.83
  776.11     .73  801.59     3.3  817.82    3.97  879.26    2.83   940.7    3.11
  949.47     .04  958.25       0  993.36     .35 1010.91       2 1028.47    1.57
  1054.8    3.66 1072.35    7.62 1081.13   11.38 1098.72   14.73 1133.24   17.56
  1176.4   23.04 1228.18   27.31  1288.6   27.85 1392.17   26.72 1440.93   27.77
#Mann= 3 , 0 , 0
       0     .05       0  722.51     .04       0  801.59     .08       0
Bank Sta=722.51,801.59
XS Rating Curve= 0 ,0
Exp/Cntr=0.3,0.1

Type RM Length L Ch R = 1 ,1175.526,1372.28,1175.53,707.38
XS GIS Cut Line= 6
1608552.95204343705176.915697053 1608187.7390608704829.862476006
1608123.17101966704712.8329014631608094.92250167704638.176103905
1607683.30123952704398.4672512111607489.59711614704323.810453683
#Sta/Elev= 30
       0    12.5   48.28    8.61  125.53    8.83  164.16    7.02  251.07    7.23
  280.04    5.91  405.57    8.28  492.48    6.35   519.8    9.73  535.79    7.54
  567.77    8.55  599.75    7.33  647.36    1.99  667.41       0  689.86     .02
  704.83    2.01  936.01    3.07  976.51       0 1008.91     .25 1033.21    3.11
 1098.02    1.73 1179.02    2.16 1187.12    3.55 1193.63    6.25 1216.13   18.96
 1223.63   21.33 1246.14   24.27 1283.65   27.64 1373.67   24.74 1401.22   25.45
#Mann= 3 , 0 , 0
       0     .07       0  647.36     .04       0  704.83     .08       0
#XS Ineff= 2 , 0
          563.33    9.27
Permanent Ineff=
       F       F
Bank Sta=647.36,704.83
XS Rating Curve= 0 ,0
Exp/Cntr=0.3,0.1

Chan Stop Cuts=-1
Use User Specified Reach Order=0
User Specified Reach Order=StonyRun        ,Reach1