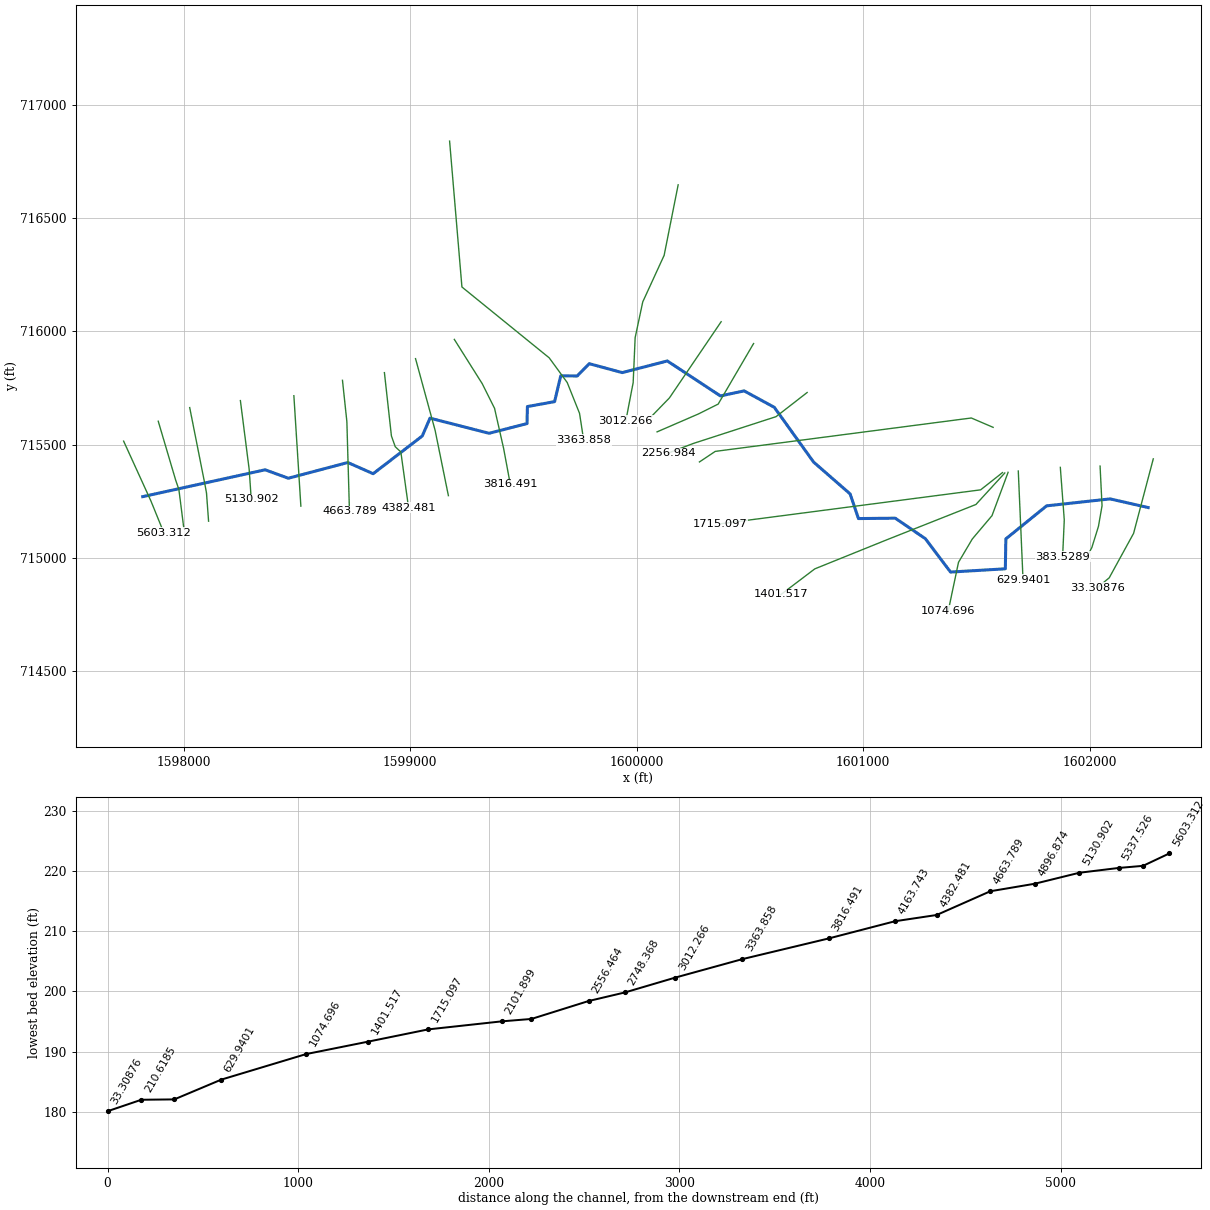
--- StonyRunTrib.prj (project) ---

Proj Title=StonyRunTrib
Current Plan=p01
Default Exp/Contr=0.3,0.1
English Units
Geom File=g01
Flow File=f01
Plan File=p01
Y Axis Title=Elevation
X Axis Title(PF)=Main Channel Distance
X Axis Title(XS)=Station
BEGIN DESCRIPTION:
Stony Run Trib - Georeferenced HEC-RAS model.  This was formerly an approximate method stream.  Projection:  MD Stateplane.  Horizontal datum:  NAD83.  Vertrial datum: NAVD88.  Units:Feet.  Created by: Aaron W. Buesing, USACE- St Paul District as part of FEMA Map Modernization study for Cecil County, MD.
END DESCRIPTION:
DSS Export Rating Curves= 0
DSS Export Rating Curve Sorted= 0
DSS Export Volume Flow Curves= 0
DXF OffsetX= 0
DXF OffsetY= 0
DXF ScaleX= 1
DXF ScaleY= 10

--- StonyRunTrib.p01 (plan) ---

Plan Title=StonyRunTrib_100yr
Program Version=4.00
Short Identifier=StonyRunTrib100
Geom File=g01
Flow File=f01
Subcritical Flow
K Sum by GR= 0
Std Step Tol= 0.01
Critical Tol= 0.01
Num of Std Step Trials= 20
Max Error Tol= 0.3
Flow Tol Ratio= 0.001
Split Flow NTrial= 30
Split Flow Tol= 0.02
Split Flow Ratio= 0.02
Log Output Level= 0
Friction Slope Method= 1
Unsteady Friction Slope Method= 2
Unsteady Bridges Friction Slope Method= 1
Parabolic Critical Depth
Global Vel Dist= 0 , 0 , 0
Global Log Level= 0
CheckData=True
Encroach Param=-1 ,0,0, 0
Computation Interval=1HOUR
Output Interval=1HOUR
Run HTab= 0
Run UNet= 0
Run PostProcess= 0
Run WQNet= 0
UNET Theta= 1
UNET Theta Warmup= 1
UNET ZTol= 0.02
UNET ZSATol= 0.05
UNET MxIter= 20
UNET MaxInSteps= 0
UNET DtIC= 0
UNET DtMin= 0
UNET MaxCRTS= 20
UNET WFStab= 2
UNET SFStab= 1
UNET WFX= 1
UNET SFX= 1
UNET DSS MLevel= 4
UNET DZMax Abort= 100
UNET Convert EG Bridges= 0
UNET Use Existing IB Tables=-1
UNET Froude Reduction=False
UNET Froude Limit= 1
UNET Froude Power= 10
UNET Time Slicing=0,0, 5
Instantaneous Interval=1HOUR
Write IC File= 0
Echo Input=False
Echo Output=False
Write Detailed= 0
Detailed Automatic Start=False, 10
WQ ULTIMATE=-1
WQ Max Comp Step=1HOUR
WQ Output Interval=15MIN
WQ Output Selected Increments= 0
WQ Output face flow=0
WQ Output face velocity=0
WQ Output face area=0
WQ Output face dispersion=0
WQ Output cell volume=0
WQ Output cell surface area=0
WQ Output cell continuity=0
WQ Output face conc=0
WQ Output face dconc_dx=0
WQ Output face courant=0
WQ Output face peclet=0
WQ Output face adv mass=0
WQ Output face disp mass=0
WQ Output cell mass=0
WQ Output cell source sink temp=0
WQ Output cell source sink nsm=0
WQ Output MaxMinRange=-1
WQ Create Restart=0
WQ Fixed Restart=0
Sorting and Armoring Iterations= 10
XS Update Threshold= 0.02
Hydraulics Update Threshold= 0.02
Energy Slope Method= 1
Volume Change Method= 0
XS Weighting Method= 0
Number of US Weighted Cross Sections= 1
Number of DS Weighted Cross Sections= 1
Upstream XS Weight=0.25
Main XS Weight=0.5
Downstream XS Weight=0.25
Number of DS XS's Weighted with US Boundary= 1
Upstream Boundary Weight= 1
Weight of XSs Associated with US Boundary= 0
Number of US XS's Weighted with DS Boundary= 1
Downstream Boundary Weight= 0.5
Weight of XSs Associated with DS Boundary= 0.5
Sediment Output Level= 4
Mass or Volume Output= 0
Output Increment Type= 1
Profile and TS Output Increment= 10
XS Output Flag= 0
XS Output Increment= 10
Disregard all LS=0
Disregard all Conn=0
Disregard all Breaches=0
Disregard all Pumps=0

--- StonyRunTrib.f01 (steady flow) ---

Flow Title=StonyRunTrib_100yr
Program Version=4.00
Number of Profiles= 2
Profile Names=100CUR,100ULT
River Rch & RM=StonyRunTrib,Reach1          ,5603.312
    1630    1630
River Rch & RM=StonyRunTrib,Reach1          ,3012.266
    2530    2560
River Rch & RM=StonyRunTrib,Reach1          ,210.6185
    2590    2640
Boundary for River Rch & Prof#=StonyRunTrib,Reach1          , 1
Up Type= 0
Dn Type= 3
Dn Slope=0.005
Boundary for River Rch & Prof#=StonyRunTrib,Reach1          , 2
Up Type= 0
Dn Type= 3
Dn Slope=0.005
DSS Import GetInterval= 0
DSS Import GetPeak= 0
DSS Import FillOption= 0

--- StonyRunTrib.g01 (geometry) ---

Geom Title=StonyRunTrib
Program Version=4.00

River Reach=StonyRunTrib    ,Reach1
Reach XY= 30
1597818.32251385715270.5851113651598358.80774793715389.176186696
 1598461.3593016715351.9032496661598723.92584603715421.240382269
1598835.99955796715371.9221946751599052.77613372715538.365423054
1599087.09432516715617.2972633241599347.91257997715550.376790047
1599515.49974805715593.2745293381599517.25610444 715668.44498691
1599637.23825561715690.1658935991599664.49789582715804.045421645
1599737.13806766715803.4734517781599790.33126438715857.810588196
1599936.15930478715818.4226759371600135.22908817715869.821955219
1600369.73672955715715.3900938031600474.40721335715737.696918234
1600607.67619006715665.0567463931600781.20600766 715423.30904007
1600942.56131443715282.6403110471600979.45659713715173.734639198
1601141.89603654715175.4505487831601274.58088802715085.083493114
1601386.12716547714937.5110882521601628.07041498714951.810334682
1601630.39002608715084.0491642361601810.36325292715229.889537692
1602090.79402931715260.6740574691602258.95316727715222.352077052

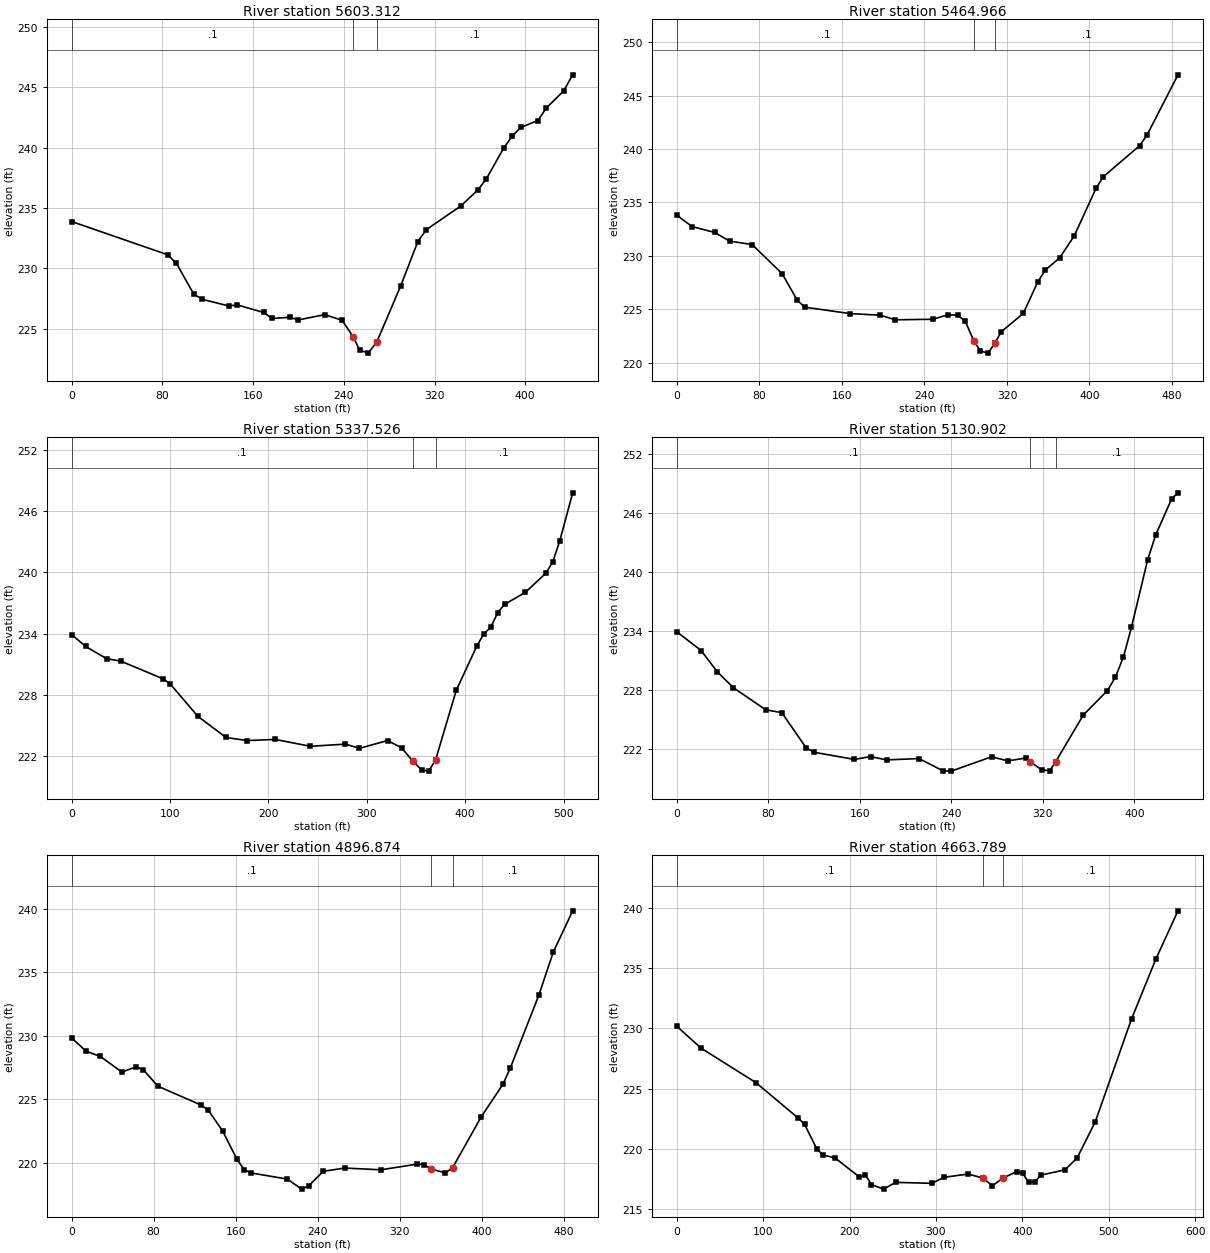
Type RM Length L Ch R = 1 ,5603.312,143.77,138.35,131.26
XS GIS Cut Line= 3
1597733.93560563715515.708344162 1597854.3640676715251.692100555
1597911.49038933715111.192228213
#Sta/Elev= 30
       0  233.87   84.63  231.12   92.33  230.42  107.71  227.86  115.41  227.42
  138.49  226.88  146.18  226.96  169.26  226.34  176.96  225.84  192.35  225.94
  200.04  225.72  223.12  226.16  238.51  225.69   248.5  224.29   253.9  223.23
  261.59  222.97  269.28  223.93  290.19  228.54   305.3  232.21  312.85   233.2
  343.08  235.15  358.19  236.48  365.75  237.41  380.86  239.93  388.42  240.93
  395.98  241.66  411.09  242.23  418.65  243.28  433.76  244.67  441.85  246.02
#Mann= 3 , 0 , 0
       0      .1       0   248.5     .04       0  269.28      .1       0
Bank Sta=248.5,269.28
XS Rating Curve= 0 ,0
Exp/Cntr=0.3,0.1

Type RM Length L Ch R = 1 ,5464.966,127.01,127.44,118.61
XS GIS Cut Line= 4
 1597886.7871151715603.7137587071597963.98484716715342.785424367
1597977.88043892 715302.642603711597999.49580388715132.807593197
#Sta/Elev= 30
       0  233.81    14.6  232.75    36.5   232.2    51.1  231.39      73  231.06
   102.2  228.32   116.8  225.83   124.1   225.2   167.9   224.6   197.1  224.45
   211.7  224.02   248.2  224.07   262.8  224.49  272.11  224.45  279.52  223.89
  287.98  222.03  294.33   221.1  301.74   220.9  308.28  221.84  314.59  222.91
  335.76  224.61  349.87  227.56  356.93  228.66  371.04  229.81  385.15  231.86
  406.32  236.32  413.38  237.41  448.66  240.32  455.72   241.3  485.79  246.95
#Mann= 3 , 0 , 0
       0      .1       0  287.98     .04       0  308.28      .1       0
Bank Sta=287.98,308.28
XS Rating Curve= 0 ,0
Exp/Cntr=0.3,0.1

Type RM Length L Ch R = 1 ,5337.526,209.56,206.62,204.63
XS GIS Cut Line= 4
1598025.74303278715663.9279896921598092.13308233715328.889832601
1598099.85285556715287.2030573041598109.11658338715162.142731369
#Sta/Elev= 30
       0  233.91   14.27  232.74   35.68  231.55   49.95  231.31   92.77  229.59
   99.91  229.11  128.45   225.9  156.99  223.84   178.4  223.54  206.95  223.65
  242.63  222.98  278.31  223.19  292.58  222.78  321.12  223.54   335.4  222.83
  346.66  221.55  355.79  220.67  362.91  220.55  370.03  221.66  390.97  228.45
  412.02  232.81  419.04  233.98  426.06  234.62  433.08  236.05   440.1  236.86
  461.16  238.03  482.22  239.92  489.24  241.05  496.25  243.09  509.35  247.77
#Mann= 3 , 0 , 0
       0      .1       0  346.66     .04       0  370.03      .1       0
Bank Sta=346.66,370.03
XS Rating Curve= 0 ,0
Exp/Cntr=0.3,0.1

Type RM Length L Ch R = 1 ,5130.902,222.23,234.03,220.29
XS GIS Cut Line= 4
1598249.61645575715694.8070825041598288.21532175715392.191972867
1598291.30323103715348.9612429291598297.47904961715259.411873743
#Sta/Elev= 30
       0  233.92   21.17  232.02   35.28  229.86    49.4  228.24   77.62  225.99
   91.74   225.7  112.91  222.14  119.96  221.67  155.25  220.94  169.36  221.23
  183.47  220.89   211.7  221.03  232.87  219.77  239.93  219.75  275.21  221.21
  289.33  220.79  305.07  221.08  309.02   220.7   319.1  219.87  326.12   219.8
  331.15  220.69  355.42  225.46  376.47  227.94  383.49  229.31  390.51  231.38
  397.52  234.39  411.56   241.2  418.57  243.74  432.61  247.44  438.17  248.06
#Mann= 3 , 0 , 0
       0      .1       0  309.02     .04       0  331.15      .1       0
Bank Sta=309.02,331.15
XS Rating Curve= 0 ,0
Exp/Cntr=0.3,0.1

Type RM Length L Ch R = 1 ,4896.874,222.75,233.09,217.94
XS GIS Cut Line= 2
1598485.84151579715716.4224474881598516.72060861 715228.53278093
#Sta/Elev= 30
       0  229.82   14.03  228.78   28.06  228.36    49.1  227.13   63.13  227.55
   70.14   227.3   84.17  226.02  126.25  224.54  133.27  224.14  147.29   222.5
  161.32  220.27  168.34  219.45  175.35  219.19  210.42  218.71  224.45  217.92
  231.46  218.19  245.49  219.32  266.53  219.58   301.6  219.44  336.67  219.88
  343.69  219.85   350.7   219.5  364.73   219.2  371.74  219.61   399.8  223.63
  420.84  226.18  427.85  227.42  455.91   233.2  469.94  236.58  488.87  239.82
#Mann= 3 , 0 , 0
       0      .1       0   350.7     .04       0  371.74      .1       0
Bank Sta=350.7,371.74
XS Rating Curve= 0 ,0
Exp/Cntr=0.3,0.1

Type RM Length L Ch R = 1 ,4663.789,202.06,281.31,261.44
XS GIS Cut Line= 3
1598700.45121089715784.3564516751598719.87478136715602.151100025
 1598731.3303037715205.373461306
#Sta/Elev= 30
       0  230.16   28.16  228.35   91.52   225.5  140.79  222.54  147.83  222.04
  161.91  220.02  168.95  219.51  183.24  219.25  211.25  217.68  218.25  217.85
  225.26  217.05  239.26  216.67  253.27  217.23  295.28  217.15  309.29  217.65
   337.3  217.92  354.14  217.59  365.31  216.95  377.43  217.58  393.33  218.12
  400.33  217.98  407.33  217.23  414.33  217.26  421.34  217.83  449.35  218.27
  463.35  219.25  484.36  222.24  526.38  230.77  554.39  235.71  580.18  239.74
#Mann= 3 , 0 , 0
       0      .1       0  354.14     .04       0  377.43      .1       0
Bank Sta=354.14,377.43
XS Rating Curve= 0 ,0
Exp/Cntr=0.3,0.1

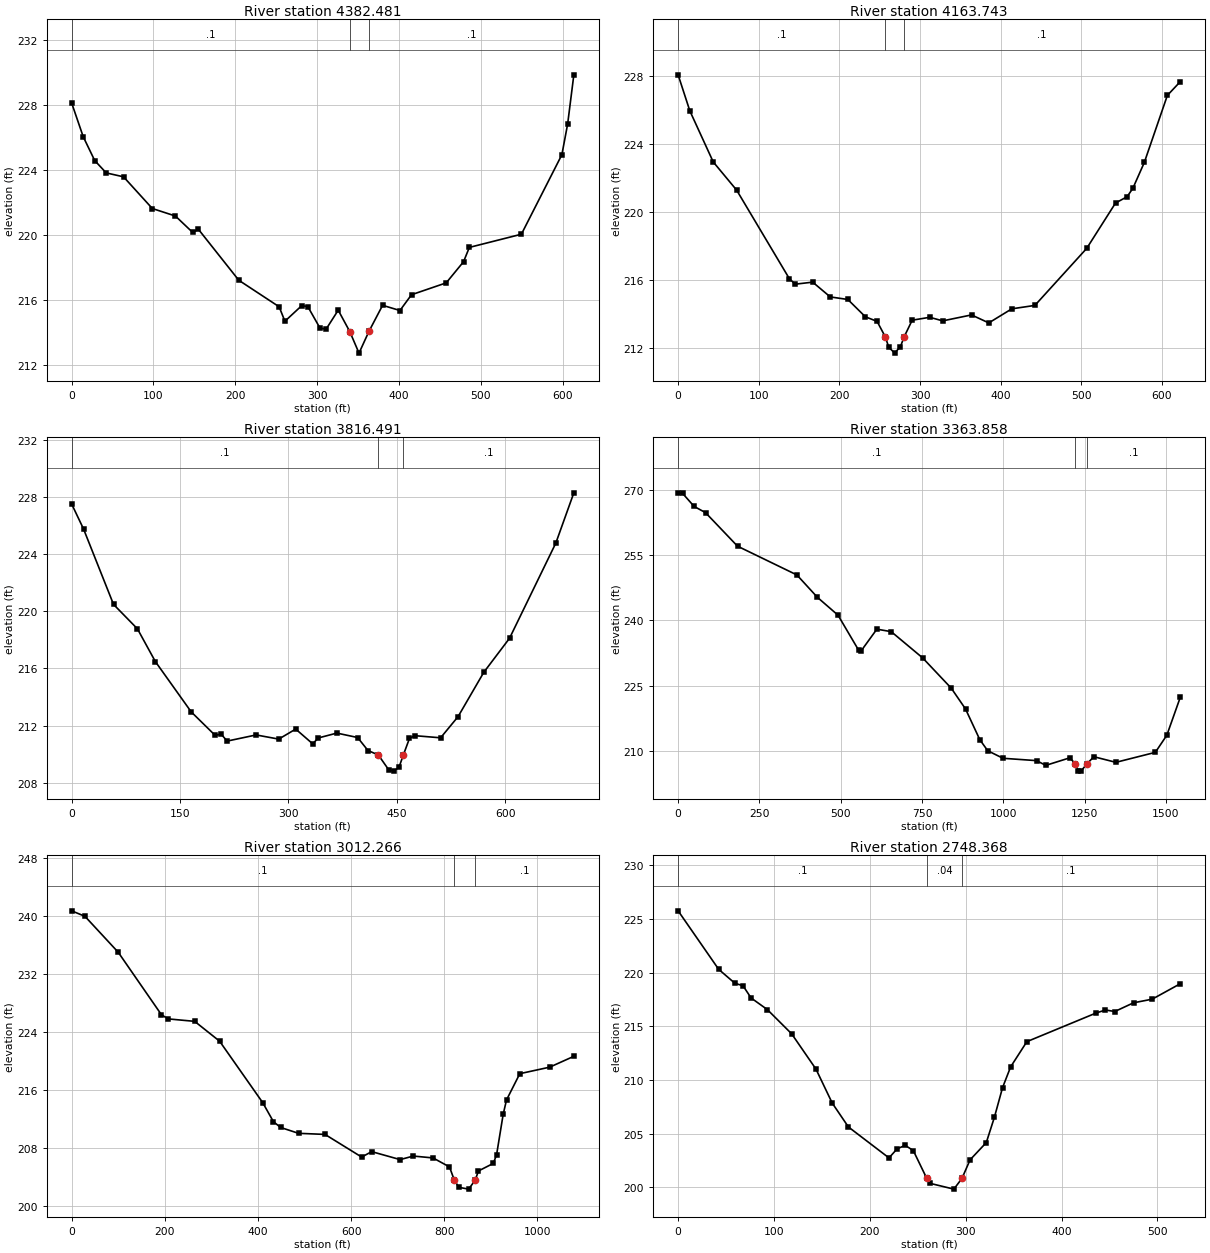
Type RM Length L Ch R = 1 ,4382.481,208.31,218.74,174.21
XS GIS Cut Line= 5
1598885.72576778715818.3234537991598916.60486065715538.867663786
 1598933.5883617715491.0050698971598958.29163595715467.845750272
1598992.25863804715222.356962383
#Sta/Elev= 30
       0   228.1   14.09  226.03   28.17  224.56   42.26   223.8   63.38  223.56
    98.6  221.61  126.77  221.15  147.89  220.14  154.94  220.33  204.24   217.2
  253.53  215.57  260.58  214.68  281.16  215.64  288.58  215.58  303.44  214.26
  310.87  214.19  325.72  215.36  339.89  214.04  351.13  212.72   363.2  214.05
  379.94  215.66  401.14  215.34  415.27  216.31  457.67  217.04  478.87  218.34
  485.94  219.22  549.54  220.03  599.01  224.92  606.07  226.81  613.63  229.83
#Mann= 3 , 0 , 0
       0      .1       0  339.89     .04       0   363.2      .1       0
Bank Sta=339.89,363.2
XS Rating Curve= 0 ,0
Exp/Cntr=0.3,0.1

Type RM Length L Ch R = 1 ,4163.743,282.86,347.25,281
XS GIS Cut Line= 3
1599023.13773087715880.0816394541599109.59919073715563.570938036
1599168.26946713715274.851420179
#Sta/Elev= 30
       0  228.07   14.51  225.95   43.54  222.94   72.56  221.28  137.87  216.07
  145.13  215.74   166.9  215.86  188.67  214.99  210.44  214.84  232.21  213.82
  246.72  213.55  256.78  212.65  261.23  212.03  268.49  211.68  275.75  212.07
  280.29  212.64  290.26  213.62  312.03  213.79  328.11  213.58  363.82  213.93
  385.25  213.46  413.82  214.29   442.4  214.49  506.68  217.85   542.4  220.52
  556.69  220.89  563.83  221.38  578.11  222.91  606.69  226.86  622.73  227.67
#Mann= 3 , 0 , 0
       0      .1       0  256.78     .04       0  280.29      .1       0
Bank Sta=256.78,280.29
XS Rating Curve= 0 ,0
Exp/Cntr=0.3,0.1

Type RM Length L Ch R = 1 ,3816.491,325.54,452.63,379.7
XS GIS Cut Line= 5
1599194.51669599715964.999144688 1599318.0330673715768.916905269
1599372.07147969 715660.840080411599412.21430036715483.285296708
1599441.54943857715325.801923305
#Sta/Elev= 30
       0   227.5   16.55  225.74   57.91  220.48      91  218.77  115.82  216.48
  165.46  212.96  198.55  211.32  206.83  211.41   215.1  210.92  255.22  211.35
  286.53  211.06     310  211.76  333.48  210.73  341.31  211.14  366.93  211.48
  395.64  211.17  409.99  210.26  424.34  209.95   438.7  208.91  445.87  208.82
  453.05  209.11  458.93  209.95   467.4  211.11  474.58   211.3  510.46  211.15
  534.61  212.63  570.21  215.73  605.82  218.11   669.9  224.77   694.8  228.28
#Mann= 3 , 0 , 0
       0      .1       0  424.34     .04       0  458.93      .1       0
Bank Sta=424.34,458.93
XS Rating Curve= 0 ,0
Exp/Cntr=0.3,0.1

Type RM Length L Ch R = 1 ,3363.858,390.02,351.59,280.85
XS GIS Cut Line= 6
1599173.61293024 716840.757818461599228.05673859716196.506086379
1599613.70038104715883.454188406 1599693.0976015715774.566571727
1599747.54140989 715638.45705083  1599765.689346715520.495466098
#Sta/Elev= 30
       0  269.29   14.05  269.14   49.17  266.17    84.3  264.74  182.65  257.04
   365.3  250.43  428.52  245.28  491.75  241.19  554.97  233.17     562  232.91
  611.17  237.98  655.34  237.41  752.04  231.38  839.94  224.43  883.89  219.65
  927.85  212.59  952.21  210.06  999.15  208.33 1102.43  207.79  1130.6   206.7
 1204.28  208.43 1221.61  207.08 1230.27   205.5 1238.94  205.38 1256.26  206.96
  1278.4  208.69 1346.25   207.4 1467.49  209.69  1502.9  213.62 1544.35  222.35
#Mann= 3 , 0 , 0
       0      .1       0 1221.61     .04       0 1256.26      .1       0
Bank Sta=1221.61,1256.26
XS Rating Curve= 0 ,0
Exp/Cntr=0.3,0.1

Type RM Length L Ch R = 1 ,3012.266,278.96,263.9,220.38
XS GIS Cut Line= 6
1600183.09187667716647.9359972331600121.16933186716336.419897676
1600026.73638763716130.8190571671599993.13557781715973.041341349
1599984.37014912 715774.358291821599951.70569119715604.429670617
#Sta/Elev= 30
       0  240.76   28.55     240   99.92  235.04   192.7  226.41  206.97  225.83
  264.07  225.49  317.61  222.75  410.05  214.27  433.16  211.63  448.56  210.83
  487.08  210.02  543.86  209.87  622.59  206.74  644.06  207.49  705.18  206.39
  733.42  206.88  775.78  206.62  811.08  205.38  821.37  203.57   831.2  202.56
  852.24  202.31  866.27  203.55  873.29  204.82  905.01  205.86  912.14  207.03
   926.4  212.66  933.53  214.63  962.04  218.26 1026.19  219.16 1078.05  220.66
#Mann= 3 , 0 , 0
       0      .1       0  821.37     .04       0  866.27      .1       0
Bank Sta=821.37,866.27
XS Rating Curve= 0 ,0
Exp/Cntr=0.3,0.1

Type RM Length L Ch R = 1 ,2748.368,194.37,191.9,184.6
XS GIS Cut Line= 3
1600372.97081959716043.1647706031600144.43584357715706.595078751
1600062.86179988715622.577606723
#Sta/Elev= 30
       0  225.77   42.31  220.32   59.23  219.02   67.69  218.79   76.15  217.65
   93.07  216.57  118.46  214.31  143.84  211.02  160.76  207.86  177.69  205.63
  219.99  202.75  228.45  203.59  236.91  203.92  245.37  203.43  259.35  200.85
   262.3  200.39  287.68  199.84  296.14  200.84   304.6  202.57  321.53  204.18
  329.99  206.54  338.45  209.29  346.91  211.23  363.83  213.58   436.1  216.25
  445.85  216.53  455.61  216.39  475.12   217.2  494.64  217.54  523.93  218.98
#Mann= 3 , 0 , 0
       0      .1       0  259.35     .04       0  296.14      .1       0
Bank Sta=259.35,296.14
XS Rating Curve= 0 ,0
Exp/Cntr=0.3,0.1

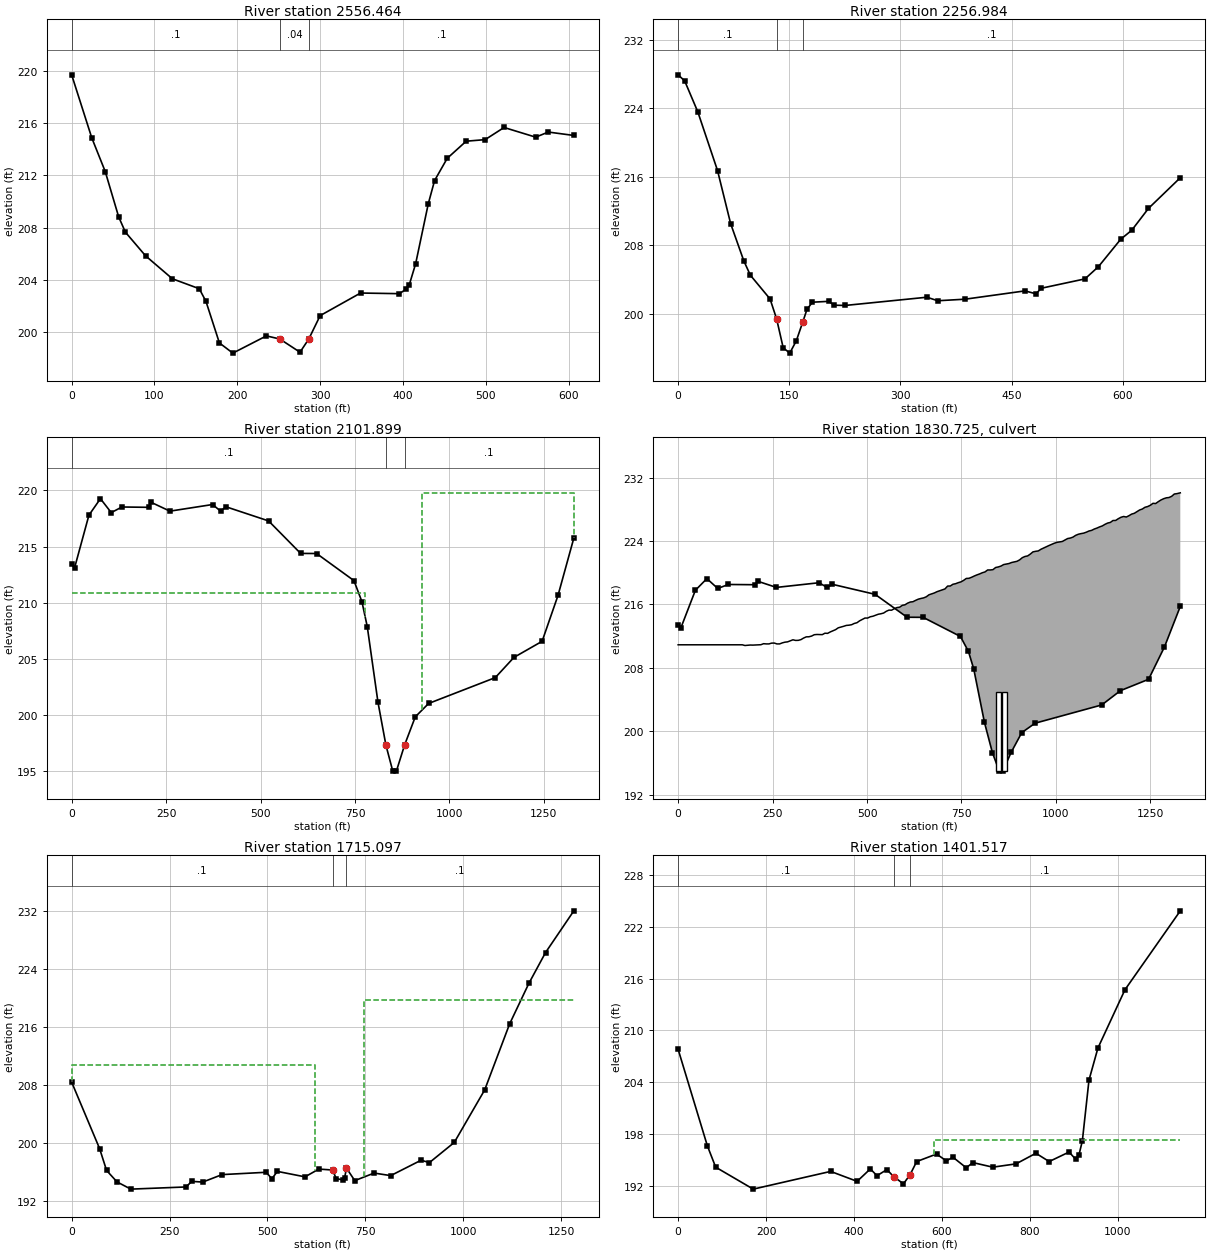
Type RM Length L Ch R = 1 ,2556.464,281.61,299.48,195.14
XS GIS Cut Line= 4
1600516.13948764715946.745055392 1600359.8226766715679.399481371
1600272.16839001715635.5723380741600089.88854076715556.639725581
#Sta/Elev= 30
       0   219.7   24.33  214.87   40.54   212.3   56.76  208.83   64.87  207.66
    89.2  205.85  121.63  204.09  154.07  203.33  162.17  202.36  178.39  199.18
  194.61   198.4  235.15  199.72  251.37  199.48   275.7  198.47  286.31  199.48
  300.02  201.27  348.82     203  395.78  202.95  403.61  203.29  407.69  203.64
  415.32  205.24  430.58  209.83   438.2  211.61  453.46  213.31  476.34  214.62
  499.23  214.74  522.11  215.67  560.25  214.93  575.51  215.32  606.33  215.06
#Mann= 3 , 0 , 0
       0      .1       0  251.37     .04       0  286.31      .1       0
Bank Sta=251.37,286.31
XS Rating Curve= 0 ,0
Exp/Cntr=0.3,0.1

Type RM Length L Ch R = 1 ,2256.984,175.15,155.09,166.18
XS GIS Cut Line= 4
1600752.80606139715730.531148538 1600615.4810124715623.885099873
1600248.30119769715504.903487459 1600138.1873823715462.629480526
#Sta/Elev= 30
       0  227.88    8.86  227.17   26.59  223.56   53.18  216.72    70.9  210.52
   88.63  206.19   97.49  204.51  124.08  201.74  132.94  199.41  141.81  196.05
  150.67  195.42  159.53  196.86   168.4  199.09  173.87  200.51  181.23  201.36
  203.31  201.46  210.66  201.01  225.38  200.98  335.76  201.94  350.47  201.53
  387.26  201.71  468.21  202.68  482.92  202.34  490.28  202.99  549.15  204.08
  567.35  205.51  597.34   208.7  612.34  209.76  634.83   212.3   677.8  215.88
#Mann= 3 , 0 , 0
       0      .1       0  132.94     .04       0   168.4      .1       0
Bank Sta=132.94,168.4
XS Rating Curve= 0 ,0
Exp/Cntr=0.5,0.3

Type RM Length L Ch R = 1 ,2101.899,410.93,386.8,350.83
BEGIN DESCRIPTION:
Channel bottom center lowered 1.5 ft based on bridge survey info
END DESCRIPTION:
XS GIS Cut Line= 4
1601574.09742197715576.676922858 1601477.7554222 715617.96942766
1600346.89766531715470.4662420151600277.04655159715423.817911446
#Sta/Elev= 30
       0  213.46    7.62  213.09    45.7  217.79   76.16  219.26  104.82  218.02
  133.06  218.52  203.65  218.49  210.71  218.93  260.12  218.15  373.07  218.74
  394.25  218.15  408.37  218.54  521.32  217.28  606.03  214.39  648.38  214.38
  747.21  211.97  768.39  210.09  782.51  207.87  810.75  201.16  831.92  197.32
  849.98  195.02  859.54  195.02  881.34  197.35  909.58  199.85  944.87  201.04
 1121.35  203.34 1170.77  205.14 1245.25  206.57 1287.34  210.65 1329.25  215.76
#Mann= 3 , 0 , 0
       0      .1       0  831.92     .04       0  881.34      .1       0
#XS Ineff= 2 , 0
       0  776.93  210.83  926.33       0  219.78
Permanent Ineff=
       F       F
Bank Sta=831.92,881.34
XS Rating Curve= 0 ,0
Exp/Cntr=0.5,0.3

Type RM Length L Ch R = 2 ,1830.725,,,
BEGIN DESCRIPTION:
John F. Kennedy Memorial Highway
MDE Bridge #: CE041307FS-3
Top of road obtained from DEM.
Openings from MDE2 bridge/culvert surveys.
END DESCRIPTION:
Bridge Culvert--1,0,-1,-1, 0
Deck Dist Width WeirC Skew NumUp NumDn MinLoCord MaxHiCord MaxSubmerge Is_Ogee
72,242,2.6,0, 166, 166, , , 0.95, 0, 2,2,,
       0  169.79  176.85  183.91  190.97  198.03  205.09  212.15  219.21  226.26
  233.32  240.38  247.44   254.5  261.56  268.62  275.68  282.74   289.8  296.86
  303.92  310.98  318.04  325.09  332.15  339.21  346.27  353.33  360.39  367.45
  374.51  381.57  388.63  395.69  402.75  409.81  416.87  423.92  430.98  438.04
   445.1  452.16  459.22  466.28  473.34   480.4  487.46  494.52  501.58  508.64
   515.7  522.75  529.81  536.87  543.93  550.99  558.05  565.11  572.17  579.23
  586.29  593.35  600.41  607.47  614.53  621.58  628.64   635.7  642.76  649.82
  656.88  663.94     671  678.06  685.12  692.18  699.24   706.3  713.36  720.41
  727.47  734.53  741.59  748.65  755.71  762.77  769.83  776.89  783.95  791.01
  798.07  805.13  812.19  819.24   826.3  833.36  840.42  847.48  854.54   861.6
  868.66  875.72  882.78  889.84   896.9  903.96  911.02  918.07  925.13  932.19
  939.25  946.31  953.37  960.43  967.49  974.55  981.61  988.67  995.73 1002.79
 1009.84  1016.9 1023.96 1031.02 1038.08 1045.14  1052.2 1059.26 1066.32 1073.38
 1080.44  1087.5 1094.56 1101.62 1108.67 1115.73 1122.79 1129.85 1136.91 1143.97
 1151.03 1158.09 1165.15 1172.21 1179.27 1186.33 1193.39 1200.44  1207.5 1214.56
 1221.62 1228.68 1235.74  1242.8 1249.86 1256.92 1263.98 1271.04  1278.1 1285.16
 1292.22 1299.28 1306.33 1313.39 1320.45 1329.25
  210.92  210.92  210.83  210.86  210.89  210.88   210.9  210.92  210.93  211.06
  211.03  211.03  211.13  211.14  211.03  211.03  211.16  211.25  211.29  211.42
  211.55  211.47  211.48  211.57  211.77  211.92  211.93  212.02  212.19  212.22
  212.21   212.2  212.38  212.36  212.54  212.68  212.83  213.06  213.15  213.25
  213.36  213.39  213.45  213.61   213.7  213.94  214.12  214.29  214.29  214.45
  214.52  214.65  214.77  214.83  214.92  215.14  215.29  215.28  215.47  215.61
  215.66  215.89  215.96  216.17  216.31  216.35  216.52  216.67  216.76  216.83
  216.97  217.22  217.33  217.45  217.61  217.73  217.85  217.96  218.32  218.33
  218.55  218.62  218.75  218.85  219.04  219.28   219.3  219.43  219.59  219.73
  219.85     220   220.1  220.35  220.35  220.39  220.66  220.73  220.84  221.03
   221.1  221.16  221.29  221.37  221.44  221.62   221.9  222.05  222.12  222.35
  222.63   222.7  222.75  222.96  223.12  223.27  223.43  223.58  223.72  223.83
  223.89  223.94  224.13  224.31  224.37  224.49  224.71  224.85  224.93  224.99
  225.11  225.26  225.34  225.51  225.63  225.78   225.9   226.1  226.26  226.34
  226.58  226.59  226.81  226.99  227.09  227.02  227.19  227.39  227.49   227.7
  227.91  228.03  228.25  228.34   228.5  228.75  228.72  228.96  229.17  229.33
  229.44  229.48  229.63  229.92  229.97  230.07
                                                                                
                                                                                
                                                                                
                                                                                
                                                                                
                                                                                
                                                                                
                                                                                
                                                                                
                                                                                
                                                                                
                                                                                
                                                                                
                                                                                
                                                                                
                                                                                
                                                
       0  122.94     130  137.06  144.12  151.18  158.24   165.3  172.36  179.41
  186.47  193.53  200.59  207.65  214.71  221.77  228.83  235.89  242.95  250.01
  257.07  264.13  271.19  278.24   285.3  292.36  299.42  306.48  313.54   320.6
  327.66  334.72  341.78  348.84   355.9  362.96  370.02  377.07  384.13  391.19
  398.25  405.31  412.37  419.43  426.49  433.55  440.61  447.67  454.73  461.79
  468.85   475.9  482.96  490.02  497.08  504.14   511.2  518.26  525.32  532.38
  539.44   546.5  553.56  560.62  567.68  574.73  581.79  588.85  595.91  602.97
  610.03  617.09  624.15  631.21  638.27  645.33  652.39  659.45  666.51  673.56
  680.62  687.68  694.74   701.8  708.86  715.92  722.98  730.04   737.1  744.16
  751.22  758.28  765.34  772.39  779.45  786.51  793.57  800.63  807.69  814.75
  821.81  828.87  835.93  842.99  850.05  857.11  864.17  871.22  878.28  885.34
   892.4  899.46  906.52  913.58  920.64   927.7  934.76  941.82  948.88  955.94
  962.99  970.05  977.11  984.17  991.23  998.29 1005.35 1012.41 1019.47 1026.53
 1033.59 1040.65 1047.71 1054.77 1061.82 1068.88 1075.94    1083 1090.06 1097.12
 1104.18 1111.24  1118.3 1125.36 1132.42 1139.48 1146.54 1153.59 1160.65 1167.71
 1174.77 1181.83 1188.89 1195.95 1203.01 1210.07 1217.13 1224.19 1231.25 1238.31
 1245.37 1252.43 1259.48 1266.54  1273.6  1282.4
  210.92  210.92  210.83  210.86  210.89  210.88   210.9  210.92  210.93  211.06
  211.03  211.03  211.13  211.14  211.03  211.03  211.16  211.25  211.29  211.42
  211.55  211.47  211.48  211.57  211.77  211.92  211.93  212.02  212.19  212.22
  212.21   212.2  212.38  212.36  212.54  212.68  212.83  213.06  213.15  213.25
  213.36  213.39  213.45  213.61   213.7  213.94  214.12  214.29  214.29  214.45
  214.52  214.65  214.77  214.83  214.92  215.14  215.29  215.28  215.47  215.61
  215.66  215.89  215.96  216.17  216.31  216.35  216.52  216.67  216.76  216.83
  216.97  217.22  217.33  217.45  217.61  217.73  217.85  217.96  218.32  218.33
  218.55  218.62  218.75  218.85  219.04  219.28   219.3  219.43  219.59  219.73
  219.85     220   220.1  220.35  220.35  220.39  220.66  220.73  220.84  221.03
   221.1  221.16  221.29  221.37  221.44  221.62   221.9  222.05  222.12  222.35
  222.63   222.7  222.75  222.96  223.12  223.27  223.43  223.58  223.72  223.83
  223.89  223.94  224.13  224.31  224.37  224.49  224.71  224.85  224.93  224.99
  225.11  225.26  225.34  225.51  225.63  225.78   225.9   226.1  226.26  226.34
  226.58  226.59  226.81  226.99  227.09  227.02  227.19  227.39  227.49   227.7
  227.91  228.03  228.25  228.34   228.5  228.75  228.72  228.96  229.17  229.33
  229.44  229.48  229.63  229.92  229.97  230.07
                                                                                
                                                                                
                                                                                
                                                                                
                                                                                
                                                                                
                                                                                
                                                                                
                                                                                
                                                                                
                                                                                
                                                                                
                                                                                
                                                                                
                                                                                
                                                                                
                                                
BR Coef=-1 , 0 , 0 ,, 0 ,,,0.8,-1,,0,
WSPro=,,,, 1 ,,,, 0 ,,,, 0 ,,,,-1 ,-1 ,-1 , 0 , 0 , 0 , 0 , 0
Multiple Barrel Culv=2,10,14,320,0.015,0.4,1,8,1,195,195, 2,Culvert #1  , 0 ,33.4
     848     678     863     693
Culvert Bottom n=0.015
BC Design=,, 0 ,, 0 ,,,,,,
BC Use User HTab Curves=0
BC User HTab FreeFlow(D)= 0

Type RM Length L Ch R = 1 ,1715.097,263.33,313.58,255.92
BEGIN DESCRIPTION:
Channel bottom center lowered 1.5 ft based on bridge survey info
END DESCRIPTION:
XS GIS Cut Line= 3
1601615.61951439715376.851852834 1601519.1439611715300.657296091
1600369.42081739715150.693407804
#Sta/Elev= 30
       0  208.41   71.36  199.26    89.2  196.25  115.96  194.67  151.17  193.68
  292.36  193.98  306.48  194.75  334.71  194.65  384.13  195.68  497.08     196
   511.2   195.1  525.32  196.12  595.91  195.37   631.2  196.44   666.5  196.31
  675.46  195.13  691.91  194.96  696.99  195.21   701.8  196.57  722.97  194.85
  772.39  195.89  814.75  195.54   892.4  197.66  913.57  197.33  977.11  200.11
 1054.76  207.34 1118.29  216.41 1167.71  222.02 1210.07  226.24  1282.4  231.99
#Mann= 3 , 0 , 0
       0      .1       0   666.5     .04       0   701.8      .1       0
#XS Ineff= 2 , 0
       0  621.79  210.83  746.73       0  219.78
Permanent Ineff=
       F       F
Bank Sta=666.5,701.8
XS Rating Curve= 0 ,0
Exp/Cntr=0.5,0.3

Type RM Length L Ch R = 1 ,1401.517,213.95,326.82,394.35
XS GIS Cut Line= 5
1601625.80661161715375.191613898 1601498.1455199715235.924968347
1601106.45807931715080.7006863211600786.58000278714951.588900357
1600637.15849769 714838.43475084
#Sta/Elev= 30
       0  207.82   66.47  196.67   85.46  194.19  170.93  191.65  347.05   193.7
  407.28  192.55   437.4  193.99  452.46   193.2  475.05  193.91  490.11  193.11
   512.7  192.26  527.76  193.32  542.82  194.84     588  195.71  610.25  194.92
  625.35  195.34  655.54  194.12  670.64  194.72  715.93  194.19  768.77  194.57
  814.06   195.8  844.26  194.84  889.55  195.94  904.65   195.1   912.2  195.64
  919.75  197.23  934.84  204.26   955.2  207.97 1016.67  214.71 1142.63  223.84
#Mann= 3 , 0 , 0
       0      .1       0  490.11     .04       0  527.76      .1       0
#XS Ineff= 2 , 0
                          581.64          197.33
Permanent Ineff=
       F       F
Bank Sta=490.11,527.76
XS Rating Curve= 0 ,0
Exp/Cntr=0.3,0.1

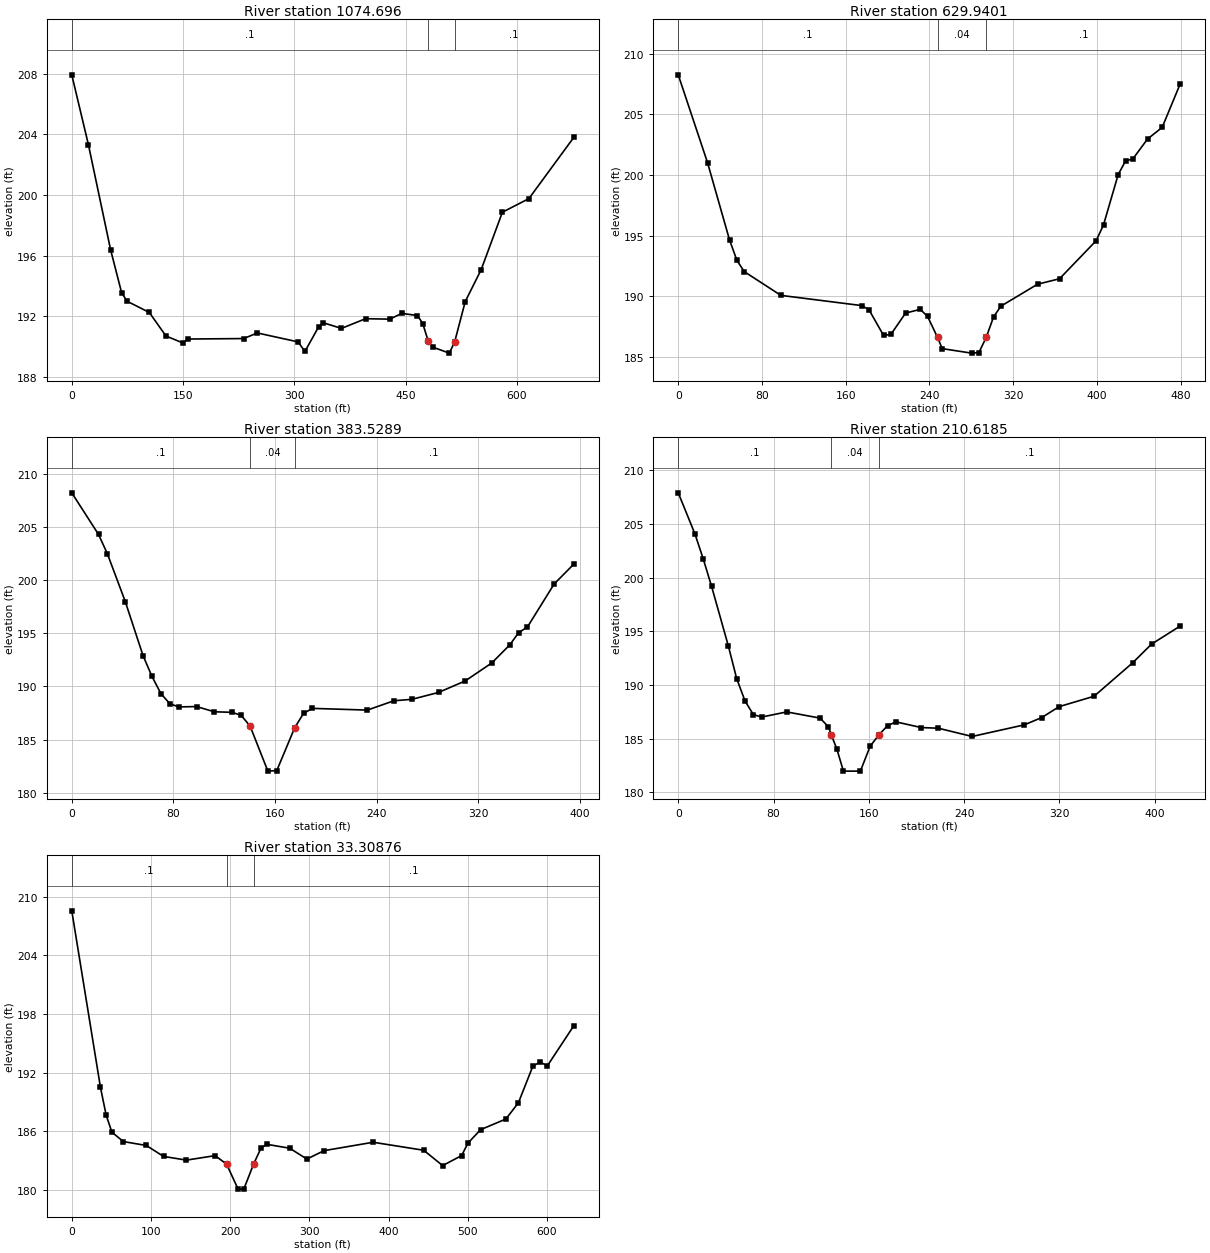
Type RM Length L Ch R = 1 ,1074.696,213.05,444.76,370.07
XS GIS Cut Line= 5
 1601640.3135539715378.0930023491601569.22953691715186.601364717
1601482.18788342715083.6020747721601421.25872602714980.602784842
1601376.28720503714767.350733846
#Sta/Elev= 30
       0  207.92    22.4  203.32   52.27   196.4    67.2  193.55   74.67  192.99
  104.53  192.25  126.93   190.7  149.33  190.25   156.8   190.5  231.75  190.53
  250.08   190.9  305.07  190.31  314.24  189.68  332.57  191.29  339.11  191.57
  363.51   191.2  396.04  191.84  428.58  191.81  444.84  192.19  465.94  192.05
  473.09  191.52  480.24  190.39   487.4  189.95  508.86  189.57  516.01   190.3
  530.32  192.97  551.78  195.07   580.4  198.86  616.17  199.76  676.72   203.8
#Mann= 3 , 0 , 0
       0      .1       0  480.24     .04       0  516.01      .1       0
Bank Sta=480.24,516.01
XS Rating Curve= 0 ,0
Exp/Cntr=0.3,0.1

Type RM Length L Ch R = 1 ,629.9401,208.38,246.41,221.55
XS GIS Cut Line= 2
1601685.28507483715383.8957792371601706.17477241714904.605365306
#Sta/Elev= 30
       0  208.26   28.03  201.01   49.05  194.64   56.05  192.97   63.06  192.04
   98.09  190.08  175.17  189.24  182.17  188.91  196.19  186.78  203.19  186.86
  217.21  188.62  231.22  188.93  238.23  188.35  247.74  186.62  252.24  185.69
  280.27  185.32  287.27  185.36  294.28  186.62  301.29   188.3  308.29  189.19
  343.33     191  364.35  191.45  399.38  194.59  406.39   195.9   420.4  200.04
  427.41  201.16  434.41  201.33  448.43  202.97  462.44  203.93  479.75  207.54
#Mann= 3 , 0 , 0
       0      .1       0  247.74     .04       0  294.28      .1       0
Bank Sta=247.74,294.28
XS Rating Curve= 0 ,0
Exp/Cntr=0.3,0.1

Type RM Length L Ch R = 1 ,383.5289,173.13,172.91,156.9
XS GIS Cut Line= 3
1601870.97393557715399.8534157131601888.38226624 715167.74233982
1601881.12879516715005.264586657
#Sta/Elev= 30
       0   208.2   21.06  204.29   28.08  202.46   42.12  197.98   56.16  192.88
   63.18  190.93    70.2  189.32   77.22  188.37   84.24  188.07   98.28   188.1
  112.31  187.61  126.35  187.56  133.37  187.27  140.39  186.28  154.43  182.03
  161.45  182.08  175.49  186.09  182.51  187.46  189.53  187.93  232.76  187.77
  253.78  188.65   267.8  188.78  288.82  189.43  309.84  190.51  330.86  192.21
  344.87  193.89  351.88  195.04  358.89  195.59  379.91  199.63   395.4   201.5
#Mann= 3 , 0 , 0
       0      .1       0  140.39     .04       0  175.49      .1       0
Bank Sta=140.39,175.49
XS Rating Curve= 0 ,0
Exp/Cntr=0.3,0.1

Type RM Length L Ch R = 1 ,210.6185,198.66,177.31,160.67
XS GIS Cut Line= 5
1602046.50793672715405.6561926161602055.21210206715230.122191459
1602039.25446564 715138.728455321602010.24058113715045.884024948
1601984.12808511714996.560421318
#Sta/Elev= 30
       0  207.91   14.02  204.08   21.03  201.74   28.03  199.18   42.05  193.65
   49.06   190.6   56.07  188.51   63.08  187.24   70.09  187.01   91.11  187.49
  119.15  186.91  126.15  186.09  128.65  185.31  133.16  184.04  138.71  181.97
  152.95  181.97   161.2   184.3  168.21  185.31  175.75  186.21  182.86  186.56
  204.17  186.03  218.39  185.97  246.81   185.2  290.53  186.28   305.2  186.96
  319.86  187.98   349.2  188.95  381.64  192.07  397.48  193.81  421.61   195.5
#Mann= 3 , 0 , 0
       0      .1       0  128.65     .04       0  168.21      .1       0
Bank Sta=128.65,168.21
XS Rating Curve= 0 ,0
Exp/Cntr=0.3,0.1

Type RM Length L Ch R = 1 ,33.30876,20.75,33.31,23.78
XS GIS Cut Line= 4
1602281.52040109715437.5714655371602194.47874761715108.263876587
1602087.12737501714912.4201562851602033.45168874714867.448635325
#Sta/Elev= 30
       0  208.56    36.2  190.49   43.44  187.63   50.68  185.89   65.16  184.93
   94.13  184.53  115.85  183.41  144.81  183.03  181.01  183.49  195.49  182.62
  209.97  180.07  217.21  180.06  229.58  182.62  238.93  184.26  246.17  184.65
  275.14  184.25  296.86  183.14  318.58     184  380.53  184.86  444.39  184.04
  468.34  182.47  492.29   183.5  500.27  184.77  516.24  186.15  548.17  187.24
  563.95   188.9  582.22  192.65  591.35  193.08  600.48  192.68  633.98   196.8
#Mann= 3 , 0 , 0
       0      .1       0  195.49     .04       0  229.58      .1       0
Bank Sta=195.49,229.58
XS Rating Curve= 0 ,0
Exp/Cntr=0.3,0.1

Chan Stop Cuts=-1
Use User Specified Reach Order=0
User Specified Reach Order=StonyRunTrib    ,Reach1