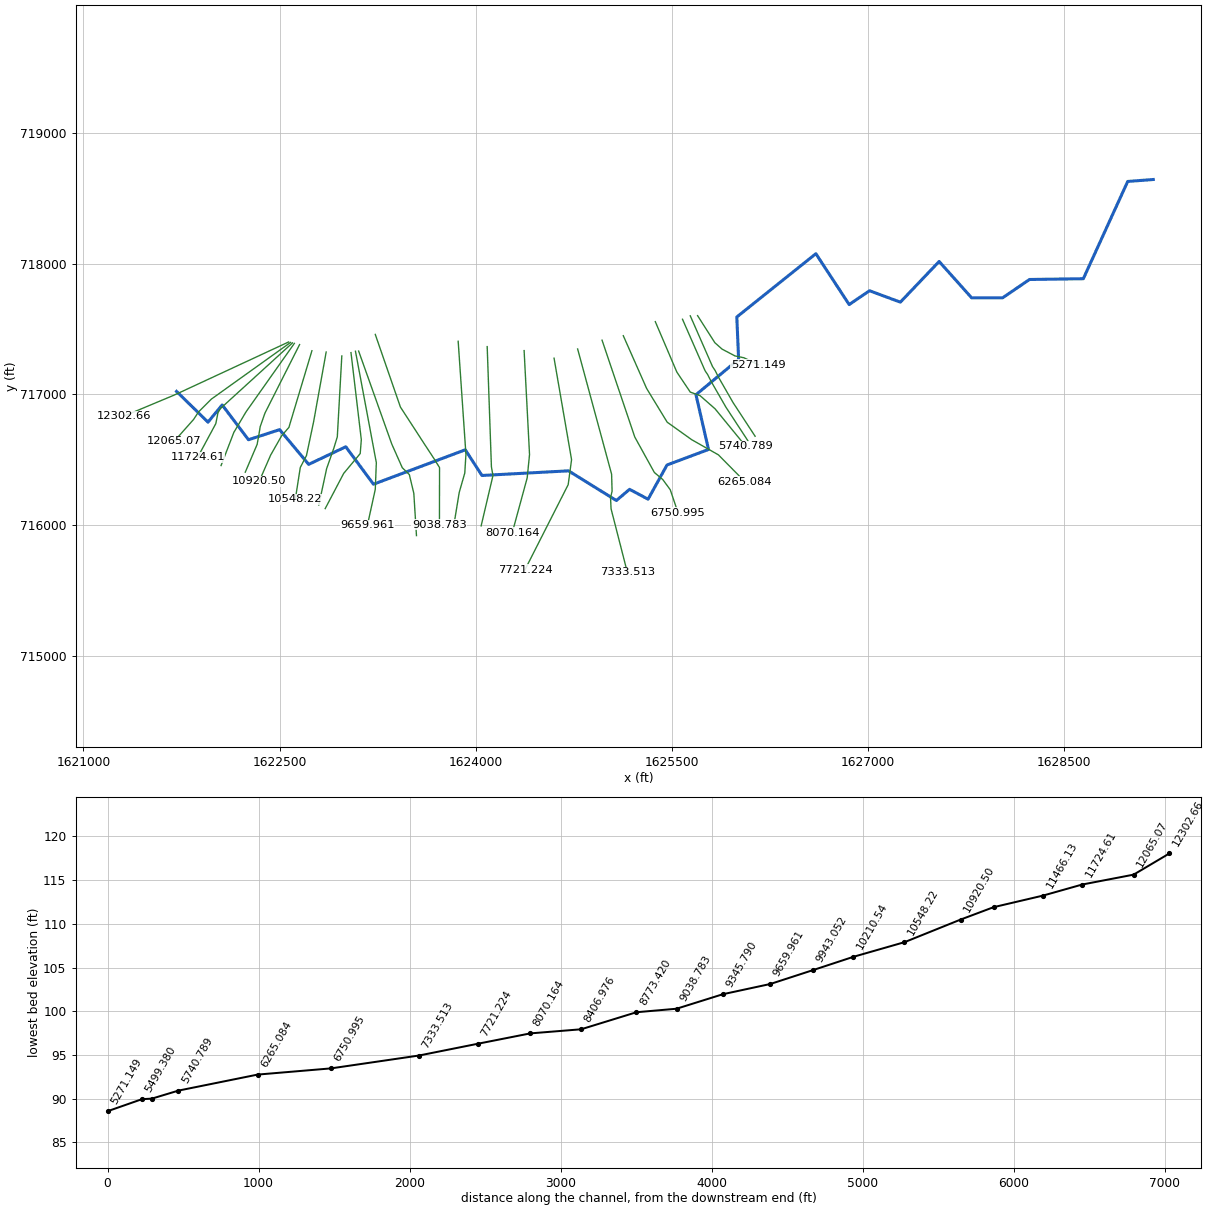
--- WestBranchLaurelRun.prj (project) ---

Proj Title=West Br Laurel Run
Current Plan=p01
Default Exp/Contr=0.3,0.1
English Units
Geom File=g01
Geom File=g02
Flow File=f01
Flow File=f02
Plan File=p01
Plan File=p02
Y Axis Title=Elevation
X Axis Title(PF)=Main Channel Distance
X Axis Title(XS)=Station
BEGIN DESCRIPTION:
West Branch Laurel Run - Georeferenced HEC-RAS model.  This was formerly an approximate method stream.  Projection:  MD Stateplane.  Horizontal datum:  NAD83.  Vertrial datum: NAVD88.  Units:Feet.  Created by: Aaron W. Buesing, USACE- St Paul District as part of FEMA Map Modernization study for Cecil County, MD.
LOMR 06-03-B926P changed a portion of this stream to a detailed stream - station 2765 to station 512 is now detailed
END DESCRIPTION:
DSS Export Rating Curves= 0
DSS Export Rating Curve Sorted= 0
DSS Export Volume Flow Curves= 0
DXF OffsetX= 0
DXF OffsetY= 0
DXF ScaleX= 1
DXF ScaleY= 10

--- WestBranchLaurelRun.p01 (plan) ---

Plan Title=West Br Laurel Run Frequency Profiles
Program Version=4.00
Short Identifier=frequency
Geom File=g01
Flow File=f01
Subcritical Flow
K Sum by GR= 0
Std Step Tol= 0.01
Critical Tol= 0.01
Num of Std Step Trials= 20
Max Error Tol= 0.3
Flow Tol Ratio= 0.001
Split Flow NTrial= 30
Split Flow Tol= 0.02
Split Flow Ratio= 0.02
Log Output Level= 0
Friction Slope Method= 1
Unsteady Friction Slope Method= 2
Unsteady Bridges Friction Slope Method= 1
Secant Critical Depth
Global Vel Dist= 0 , 0 , 0
Global Log Level= 0
CheckData=True
Encroach Param=-1 ,0,0, 0
Computation Interval=1HOUR
Output Interval=1HOUR
Run HTab= 0
Run UNet= 0
Run PostProcess= 0
Run WQNet= 0
UNET Theta= 1
UNET Theta Warmup= 1
UNET ZTol= 0.02
UNET ZSATol= 0.05
UNET MxIter= 20
UNET MaxInSteps= 0
UNET DtIC= 0
UNET DtMin= 0
UNET MaxCRTS= 20
UNET WFStab= 2
UNET SFStab= 1
UNET WFX= 1
UNET SFX= 1
UNET DSS MLevel= 4
UNET DZMax Abort= 100
UNET Convert EG Bridges= 0
UNET Use Existing IB Tables=-1
UNET Froude Reduction=False
UNET Froude Limit= 1
UNET Froude Power= 10
UNET Time Slicing=0,0, 5
Instantaneous Interval=1HOUR
Write IC File= 0
Echo Input=False
Echo Output=False
Write Detailed= 0
Detailed Automatic Start=False, 10
WQ ULTIMATE=-1
WQ Max Comp Step=1HOUR
WQ Output Interval=15MIN
WQ Output Selected Increments= 0
WQ Output face flow=0
WQ Output face velocity=0
WQ Output face area=0
WQ Output face dispersion=0
WQ Output cell volume=0
WQ Output cell surface area=0
WQ Output cell continuity=0
WQ Output face conc=0
WQ Output face dconc_dx=0
WQ Output face courant=0
WQ Output face peclet=0
WQ Output face adv mass=0
WQ Output face disp mass=0
WQ Output cell mass=0
WQ Output cell source sink temp=0
WQ Output cell source sink nsm=0
WQ Output MaxMinRange=-1
WQ Daily Max Min Mean=-1
WQ Daily Range=0
WQ Daily Time=0
WQ Create Restart=0
WQ Fixed Restart=0
WQ System Summary=False
Sorting and Armoring Iterations= 10
XS Update Threshold= 0.02
Hydraulics Update Threshold= 0.02
Energy Slope Method= 1
Volume Change Method= 0
XS Weighting Method= 0
Number of US Weighted Cross Sections= 1
Number of DS Weighted Cross Sections= 1
Upstream XS Weight=0.25
Main XS Weight=0.5
Downstream XS Weight=0.25
Number of DS XS's Weighted with US Boundary= 1
Upstream Boundary Weight= 1
Weight of XSs Associated with US Boundary= 0
Number of US XS's Weighted with DS Boundary= 1
Downstream Boundary Weight= 0.5
Weight of XSs Associated with DS Boundary= 0.5
Sediment Output Level= 4
Mass or Volume Output= 0
Output Increment Type= 1
Profile and TS Output Increment= 10
XS Output Flag= 0
XS Output Increment= 10
Disregard all LS=0
Disregard all Conn=0
Disregard all Breaches=0
Disregard all Pumps=0

--- WestBranchLaurelRun.p02 (plan) ---

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Plan Title=West Br Laurel Run Floodway
Short Identifier=floodway
Geom File=g01
Flow File=f02
Encroach Param=-1 ,0,0, 2
Encroach River=WestBrLaurelRun
Encroach Reach=Reach1
Encroach Node=2794.238
       1   384.5  637.34
Encroach Node=2764.050
       1     470     510
Encroach Node=2616.788
       1     332     373
Encroach Node=2316.886
       1     372     410
Encroach Node=2211.533
       1     478     520
Encroach Node=2072.533
       1     465     505
Encroach Node=1939.923
       1     400     440
Encroach Node=1820.804
       1  480.19  515.31
Encroach Node=1613.981
       1  349.76  385.45
Encroach Node=1294.259
       1  450.89   493.2
Encroach Node=996.0160
       1  480.09  517.96
Encroach Node=729.2011
       1  409.43  451.54
Encroach Node=512.9815
       1     405     445
BEGIN DESCRIPTION:
Detailed Reach runs from station 2764 to 512.  There is an encroachemnt set for station 2794 to get the encroachement profile to run correctly, but there is no floodway upstream of the bridge.
END DESCRIPTION:

--- WestBranchLaurelRun.f01 (steady flow) ---

Flow Title=West Br Laurel Run Frequency Flows
Program Version=4.00
Number of Profiles= 5
Profile Names=10yr,50yr,100yr-current,500yr,100yr-ultimate
River Rch & RM=WestBrLaurelRun,Reach1          ,12302.66
     124     306     428     893     429
River Rch & RM=WestBrLaurelRun,Reach1          ,8773.420
     177     429     597    1223     599
River Rch & RM=WestBrLaurelRun,Reach1          ,8406.976
     184     444     616    1252     618
River Rch & RM=WestBrLaurelRun,Reach1          ,7333.513
     214     507     700    1402     702
River Rch & RM=WestBrLaurelRun,Reach1          ,4613.885
     256     622     861    1742     862
River Rch & RM=WestBrLaurelRun,Reach1          ,4007.238
     265     634     874    1742     875
River Rch & RM=WestBrLaurelRun,Reach1          ,29.87088
     316     772    1071    2151    1072
Boundary for River Rch & Prof#=WestBrLaurelRun,Reach1          , 1
Up Type= 0
Dn Type= 3
Dn Slope=0.004
Boundary for River Rch & Prof#=WestBrLaurelRun,Reach1          , 2
Up Type= 0
Dn Type= 3
Dn Slope=0.004
Boundary for River Rch & Prof#=WestBrLaurelRun,Reach1          , 3
Up Type= 0
Dn Type= 3
Dn Slope=0.004
Boundary for River Rch & Prof#=WestBrLaurelRun,Reach1          , 4
Up Type= 0
Dn Type= 3
Dn Slope=0.004
Boundary for River Rch & Prof#=WestBrLaurelRun,Reach1          , 5
Up Type= 0
Dn Type= 3
Dn Slope=0.004
DSS Import GetInterval= 0
DSS Import GetPeak= 0
DSS Import FillOption= 0

--- WestBranchLaurelRun.f02 (steady flow) ---

Flow Title=West Br Laurel Run Encroached Flows
Program Version=4.00
Number of Profiles= 2
Profile Names=100yr,100yr-enc
River Rch & RM=WestBrLaurelRun,Reach1          ,12302.66
     428     428
River Rch & RM=WestBrLaurelRun,Reach1          ,8773.420
     597     597
River Rch & RM=WestBrLaurelRun,Reach1          ,8406.976
     616     616
River Rch & RM=WestBrLaurelRun,Reach1          ,7333.513
     700     700
River Rch & RM=WestBrLaurelRun,Reach1          ,4613.885
     861     861
River Rch & RM=WestBrLaurelRun,Reach1          ,4007.238
     874     874
River Rch & RM=WestBrLaurelRun,Reach1          ,29.87088
    1071    1071
Boundary for River Rch & Prof#=WestBrLaurelRun,Reach1          , 1
Up Type= 0
Dn Type= 3
Dn Slope=0.004
Boundary for River Rch & Prof#=WestBrLaurelRun,Reach1          , 2
Up Type= 0
Dn Type= 3
Dn Slope=0.004
Set Internal Change=WestBrLaurelRun ,Reach1          ,512.9815, 2 , 3 ,64.93
DSS Import GetInterval= 0
DSS Import GetPeak= 0
DSS Import FillOption= 0

--- WestBranchLaurelRun.g01 (geometry) ---

Geom Title=West Br Laurel Run Geometry
Program Version=4.00
BEGIN GEOM DESCRIPTION:
Detailed Reach between 2762 and 512, LOMR used to lay out sections, XS cut from DEM, LOMR HEC-RAS used to cut channel in when necessary
END GEOM DESCRIPTION:

River Reach=WestBrLaurelRun ,Reach1
Reach XY= 30
1621712.12721598 717021.373671071621952.35915267716786.472838625
1622061.17851074716917.8287501191622262.39773794716651.575468704
 1622500.6413029 716728.84365195 1622722.7873297716463.234272063
1623006.74790312716597.809691221 1623218.5915055716311.273511708
1623921.08807147716574.6292362361624048.64496392716378.239270508
1624710.89768445716413.6538544891625076.95570253716186.678566217
 1625178.0482423716272.3174693291625319.67050922716196.762990877
1625464.47124745716458.433360428 1625782.0038307716577.140564606
1625686.08252953716996.1071675421626012.43546236717266.965401217
1625998.46990891717590.7457320841626603.39888127718075.129927412
1626858.08647406717685.9320041541627013.91264921717791.776198596
1627249.85699931717704.3077323441627546.44125241 718015.59256804
1627795.24861225717737.3840431121628031.92799148717737.384043112
1628238.10366185717877.7746065711628649.71997355717883.654839575
1628989.30343065 718627.871831671629185.03283845 718642.81786111

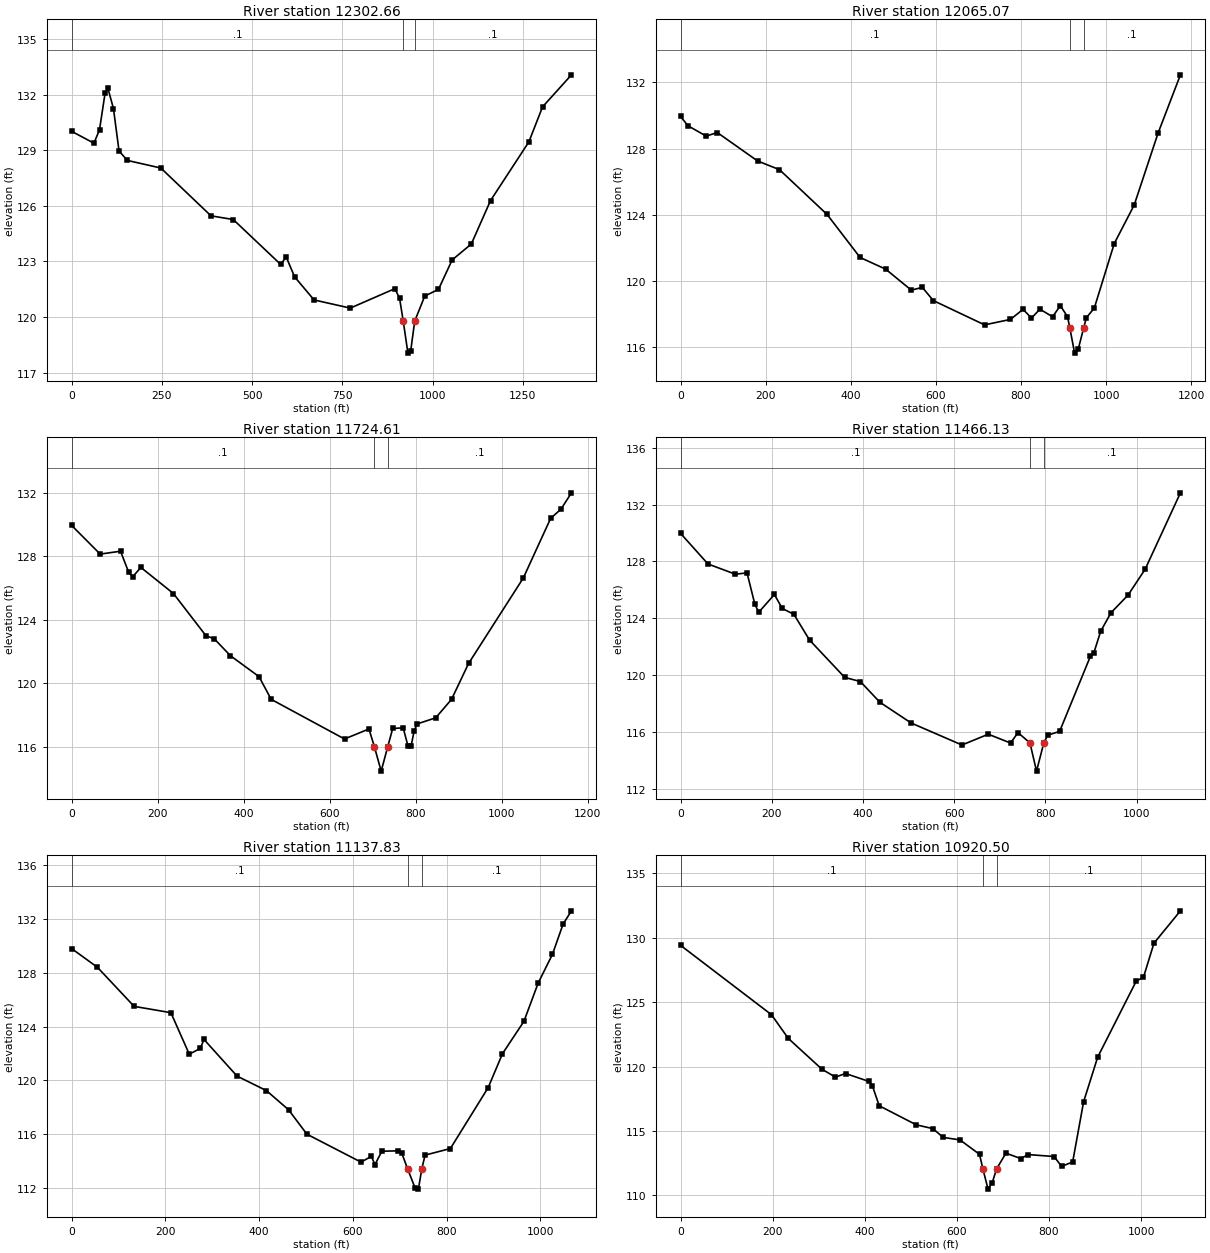
Type RM Length L Ch R = 1 ,12302.66,260.75,237.6,245.68
XS GIS Cut Line= 4
1622569.79427211 717399.795119331621752.96124493717020.421557799
1621689.42978725716991.3786057231621307.51496744  716831.6423693
#Sta/Elev= 30
       0  130.02   61.75  129.38   77.18  130.11   92.62  132.09  100.34  132.35
  115.77  131.25  131.21  128.96  154.36  128.45  246.98  128.04  385.91  125.46
  447.65  125.26  578.86  122.84   594.3  123.24  617.45  122.17  671.48  120.92
  771.81  120.48   895.3  121.53  908.33  121.01  918.43  119.78  931.42  118.05
  939.12  118.17   950.3  119.78  978.08  121.13 1016.01  121.49 1053.95  123.08
 1107.07  123.94 1160.18  126.28 1266.41  129.45 1304.34  131.34 1384.46  133.07
#Mann= 3 , 0 , 0
       0      .1       0  918.43    .045       0   950.3      .1       0
#XS Ineff= 2 , 0
          895.29  121.52
Permanent Ineff=
       F       F
Bank Sta=918.43,950.3
XS Rating Curve= 0 ,0
Exp/Cntr=0.3,0.1

Type RM Length L Ch R = 1 ,12065.07,137.89,340.45,218.76
XS GIS Cut Line= 5
1622584.31574811717396.1647502931621978.04412353716962.335653648
1621880.02416024716864.3156904131621841.90528564716806.229786247
1621694.87534079716641.047996312
#Sta/Elev= 30
       0  129.94   17.22  129.38   60.25  128.75   86.08  128.97  180.76  127.25
   232.4  126.72   344.3  124.01  421.77  121.41  482.02   120.7  542.28  119.43
   568.1   119.6  593.92   118.8  714.43  117.33   775.2  117.66   804.9  118.27
   824.7  117.74   844.5  118.28  874.19  117.82   892.5  118.49  909.24  117.83
  914.66  117.17  925.99  115.62  934.36  115.84  947.57  117.17   953.6  117.76
  972.34  118.35  1019.2  122.25 1066.06  124.58 1122.28  128.94 1174.74  132.46
#Mann= 3 , 0 , 0
       0      .1       0  914.66    .045       0  947.57      .1       0
Bank Sta=914.66,947.57
XS Rating Curve= 0 ,0
Exp/Cntr=0.3,0.1

Type RM Length L Ch R = 1 ,11724.61,157.79,258.49,199.52
XS GIS Cut Line= 5
1622598.83722417  717392.53438131622047.02113469716889.728273466
1622028.86928965716858.8701368721622012.53262915716775.371649653
1621872.76342227716515.800265491
#Sta/Elev= 30
       0  129.93   66.29  128.13  113.64  128.31  132.58  126.99  142.05  126.71
  160.99  127.29  236.75  125.65  312.51  122.99  331.45  122.81  369.33  121.74
  435.62  120.43  464.03     119   634.5  116.51  691.32  117.14  704.08  116.01
  719.73  114.49  734.76     116  746.54  117.17   770.9  117.21  782.34  116.04
  789.47  116.09   796.6  117.04  803.73  117.46  846.53  117.84  883.32     119
  923.07  121.26 1050.28  126.63 1113.88  130.38 1137.73  130.95 1162.23  131.98
#Mann= 3 , 0 , 0
       0      .1       0  704.08    .045       0  734.76      .1       0
Bank Sta=704.08,734.76
XS Rating Curve= 0 ,0
Exp/Cntr=0.3,0.1

Type RM Length L Ch R = 1 ,11466.13,149.21,328.29,205.26
XS GIS Cut Line= 4
1622613.35870019717388.9040122931622243.06106122716864.315690413
1622150.48665147716708.2098229831622052.46668823716454.083992302
#Sta/Elev= 30
       0  129.97   59.98  127.82  119.96   127.1  145.66  127.19   162.8  124.98
  171.37  124.42  205.64  125.67  222.77  124.69  248.48  124.27  282.75  122.46
  359.87  119.83  394.14  119.54  436.98  118.08  505.53  116.62  616.92  115.07
  674.67  115.83   723.5  115.21  739.78  115.94  765.98  115.22  780.47  113.23
  796.23   115.2  804.88  115.76  831.11  116.03  898.63  121.32  906.14  121.56
  921.14  123.08  943.65  124.38  981.16  125.63 1018.68  127.45 1095.98  132.83
#Mann= 3 , 0 , 0
       0      .1       0  765.98    .045       0  796.23      .1       0
Bank Sta=765.98,796.23
XS Rating Curve= 0 ,0
Exp/Cntr=0.3,0.1

Type RM Length L Ch R = 1 ,11137.83,205.2,217.33,159.01
XS GIS Cut Line= 6
1622653.29275933717379.8280897591622388.27582158716855.239767864
1622351.97213148716751.7742510891622341.08102447716684.612424418
1622328.37473294716615.6354132291622237.61550769716403.258826166
#Sta/Elev= 30
       0   129.8    54.9  128.41  133.32   125.5  211.75  125.03  250.96  121.94
  274.49  122.37  282.33  123.04  352.92  120.31  415.66  119.23  462.71  117.81
  501.92  115.99   617.4  113.91  639.66  114.34  647.08  113.72  661.91  114.72
  697.38  114.75  704.47  114.57  717.06  113.39  732.84  111.98  739.93   111.9
  747.02  113.39  754.11  114.43  808.13  114.92  888.84  119.46  919.29  121.98
  964.97  124.38  995.42  127.23 1025.87  129.37  1048.7  131.63 1066.51  132.61
#Mann= 3 , 0 , 0
       0      .1       0  717.06    .045       0  747.02      .1       0
Bank Sta=717.06,747.02
XS Rating Curve= 0 ,0
Exp/Cntr=0.3,0.1

Type RM Length L Ch R = 1 ,10920.50,278.93,372.28,258.77
XS GIS Cut Line= 5
1622747.68235359 717332.63329263 1622571.6094566716746.328697577
1622515.33873695716680.9820554261622431.84024972716533.952110514
1622344.71139351716334.281815022
#Sta/Elev= 30
       0   129.4  197.34  124.02  233.88  122.18  306.97  119.79  336.21  119.18
  358.13  119.46  409.29  118.84   416.6  118.49  431.22  116.96  511.62  115.48
  548.16  115.18  570.09   114.5  606.63  114.31  649.12  113.19  656.34  112.06
   667.6  110.49  676.84     111  686.07  112.06  706.46  113.28  738.66  112.86
  754.76  113.17  811.11  113.02  827.21  112.25  851.36   112.6  875.13  117.27
  905.68  120.73  989.69  126.65 1004.97  126.91 1027.88  129.57 1085.35  132.08
#Mann= 3 , 0 , 0
       0      .1       0  656.34    .045       0  686.07      .1       0
Bank Sta=656.34,686.07
XS Rating Curve= 0 ,0
Exp/Cntr=0.3,0.1

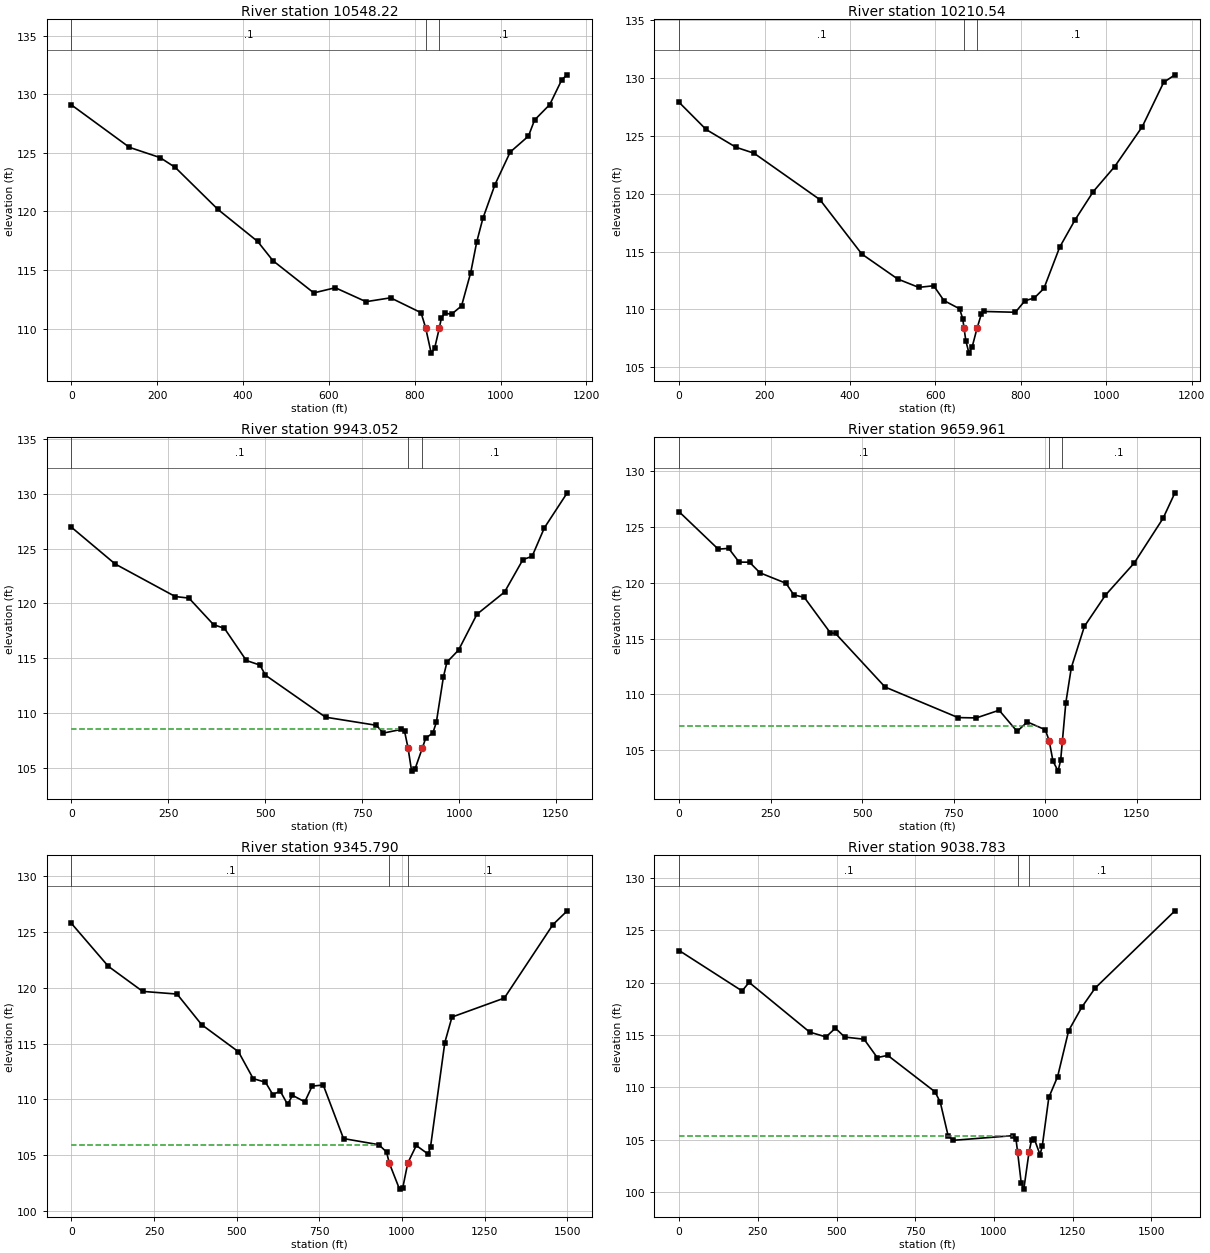
Type RM Length L Ch R = 1 ,10548.22,247.92,337.68,308.24
XS GIS Cut Line= 5
1622856.70607284717322.689461023 1622760.3886451716788.077941194
1622705.93310994716530.3217415061622658.73831281716439.562516272
1622620.61943822716196.327792645
#Sta/Elev= 30
       0  129.08  135.14  125.46  206.27  124.59  241.83  123.75  341.41  120.16
  433.87  117.43  469.44  115.79  564.68  113.04  614.76  113.48  686.31  112.29
  743.55  112.62  814.56  111.35  825.21  110.07  838.22   107.9  846.11   108.3
  857.32  110.07  861.89  110.89  869.78  111.31  885.56  111.22  908.96  111.93
  930.22  114.76  944.39   117.4  958.56  119.39   986.9  122.29 1022.33  125.06
 1064.84  126.42 1079.01  127.79 1114.44  129.11 1142.78  131.25 1155.17  131.65
#Mann= 3 , 0 , 0
       0      .1       0  825.21    .045       0  857.32      .1       0
Bank Sta=825.21,857.32
XS Rating Curve= 0 ,0
Exp/Cntr=0.3,0.1

Type RM Length L Ch R = 1 ,10210.54,237.59,267.49,213.71
XS GIS Cut Line= 5
1622976.39560117717292.6992335471622941.90709557716673.721317396
1622914.67932798 716584.777276651622860.22379282716430.486593738
1622800.32270418716152.763364509
#Sta/Elev= 30
       0  127.89    63.1  125.55  133.21  124.01  175.27   123.5  329.51  119.49
  427.66  114.79  511.79  112.63  560.87  111.91  595.92  112.05  619.94  110.77
  656.54  110.06  663.86  109.21     667  108.39  671.18   107.3   678.5  106.23
  685.82  106.74  697.46  108.38  707.79  109.64  712.96  109.83  787.19  109.76
  809.46  110.75  831.73     111     854  111.82   890.9  115.38   926.7  117.73
  969.67  120.19 1019.79  122.35 1084.24  125.79 1134.37  129.62 1160.69  130.27
#Mann= 3 , 0 , 0
       0      .1       0     667    .045       0  697.46      .1       0
#XS Ineff= 2 , 0
                          720.73          109.82
Permanent Ineff=
       F       F
Bank Sta=667,697.46
XS Rating Curve= 0 ,0
Exp/Cntr=0.3,0.1

Type RM Length L Ch R = 1 ,9943.052,215.03,283.1,272.46
XS GIS Cut Line= 5
1623046.58614893717318.2454592291623125.56453474716651.514872119
1623117.11476815716545.8031649891622990.67656063716393.948160842
1622849.28191619716124.770440519
#Sta/Elev= 30
       0  126.95  112.78   123.6  267.86  120.63   303.1  120.49  366.54  118.07
  394.74  117.73  451.13   114.8  486.38  114.38  500.48  113.46  655.55  109.63
  786.55  108.89  804.77  108.18  850.31  108.51  859.42  108.35  868.53  106.79
  877.64  104.71  886.75  104.94  904.96  106.78  914.07  107.73  932.29  108.18
   941.4  109.16  959.62  113.29  968.73  114.65  998.76  115.75 1046.21  119.02
 1117.37  121.04 1164.81     124 1188.53   124.3 1220.16   126.9  1279.1  130.09
#Mann= 3 , 0 , 0
       0      .1       0  868.53    .045       0  904.96      .1       0
#XS Ineff= 2 , 0
          842.23  108.52
Permanent Ineff=
       F       F
Bank Sta=868.53,904.96
XS Rating Curve= 0 ,0
Exp/Cntr=0.3,0.1

Type RM Length L Ch R = 1 ,9659.961,223.14,314.18,288.57
XS GIS Cut Line= 4
1623080.92616273717328.547463372 1623240.5062267716476.107121542
1623232.42622347716272.0870397541623171.82619914715995.548928842
#Sta/Elev= 30
       0  126.37  106.82  123.02  135.31  123.09   163.8  121.86  192.28  121.85
  220.77   120.9  291.99  119.96  313.35  118.92  341.84   118.7  413.05  115.52
   427.3  115.46  562.61  110.66  762.01  107.92  811.86  107.89  874.25  108.58
  923.29  106.68  951.31  107.53 1000.35  106.83 1010.88  105.85 1021.37  104.02
 1035.38  103.12 1042.39  104.11 1047.15  105.84  1056.4  109.23 1071.43  112.39
 1107.26   116.1 1164.59  118.89 1243.42  121.78 1322.24  125.79 1354.53  128.07
#Mann= 3 , 0 , 0
       0      .1       0 1010.88    .045       0 1047.15      .1       0
#XS Ineff= 2 , 0
          979.44  107.18
Permanent Ineff=
       F       F
Bank Sta=1010.88,1047.15
XS Rating Curve= 0 ,0
Exp/Cntr=0.3,0.1

Type RM Length L Ch R = 1 ,9345.790,250.74,307.01,247.37
XS GIS Cut Line= 6
1623105.16617246717330.1634640251623358.21159713716619.709209546
1623439.03979176 716437.691519321623493.00632797716384.803084925
1623527.34634173716241.3830274341623547.54634984715918.384897918
#Sta/Elev= 30
       0  125.76  111.46  121.92  215.49  119.67  319.52  119.43  393.83  116.69
  505.29  114.26  549.88  111.85  587.03  111.53  609.32  110.42  631.61  110.74
  653.91  109.54  668.77  110.36  705.92  109.77  728.21  111.18  761.83  111.28
  823.11  106.48  930.34  105.93  953.33  105.27  961.54  104.29  992.54  101.95
 1002.34  102.06  1017.6  104.29 1043.29  105.86 1079.28  105.09 1086.48  105.75
 1129.66  115.09 1151.26  117.37 1309.63  119.07 1456.91  125.66    1500  126.89
#Mann= 3 , 0 , 0
       0      .1       0  961.54    .045       0  1017.6      .1       0
#XS Ineff= 2 , 0
          930.35  105.93 1043.38          105.85
Permanent Ineff=
       F       F
Bank Sta=961.54,1017.6
XS Rating Curve= 0 ,0
Exp/Cntr=0.3,0.1

Type RM Length L Ch R = 1 ,9038.783,274.57,265.36,237.39
XS GIS Cut Line= 6
1623232.42622347717457.4235150371623424.61575703716902.111008704
 1623595.5031943716638.6044693741623678.92704889716511.371880934
1623724.15048911716438.6211293341623723.28642029716003.022931844
#Sta/Elev= 30
       0  123.07     200  119.21  222.22  120.03  414.81  115.28  466.66  114.82
  496.29  115.66  525.92  114.81  587.63   114.6  629.35  112.85  662.72  113.06
  812.89  109.58  829.58  108.59  854.61  105.38   871.3  104.95 1062.08   105.4
 1070.33  105.05 1075.37  103.81 1086.81  100.88 1095.05  100.29 1111.54  103.81
 1119.78  104.99 1128.02  105.11  1146.5  103.58  1153.5  104.36  1174.5  109.04
  1202.5  111.04  1237.5  115.42  1279.5  117.67  1321.5  119.48  1575.1  126.86
#Mann= 3 , 0 , 0
       0      .1       0 1075.37    .045       0 1111.54      .1       0
#XS Ineff= 2 , 0
         1062.05   105.4
Permanent Ineff=
       F       F
Bank Sta=1075.37,1111.54
XS Rating Curve= 0 ,0
Exp/Cntr=0.3,0.1

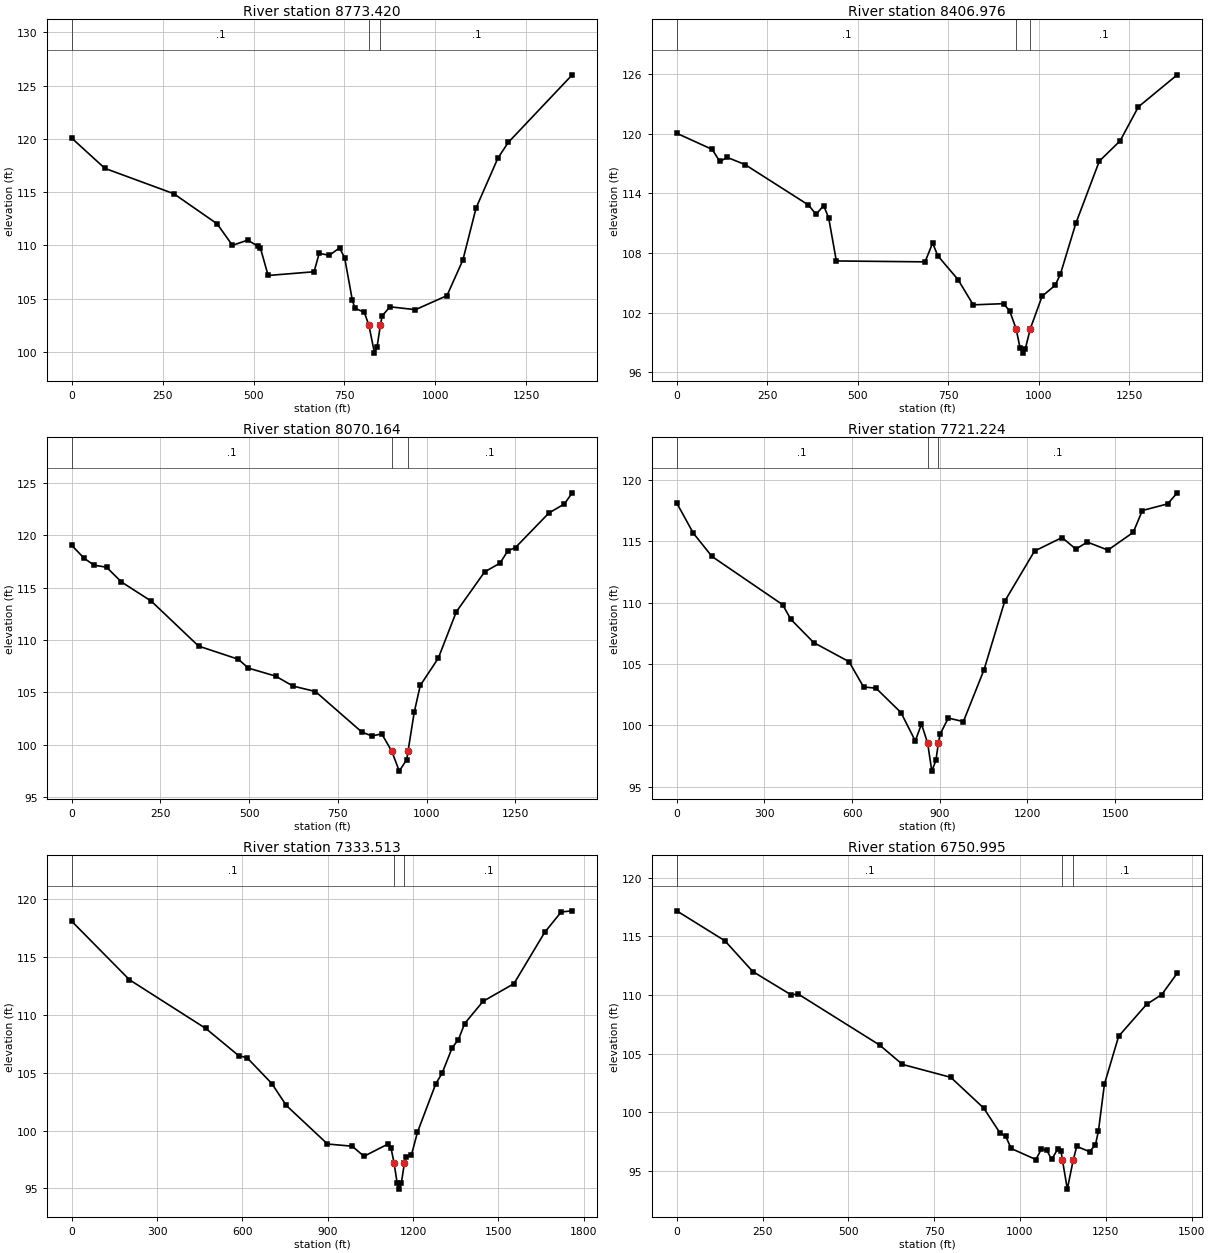
Type RM Length L Ch R = 1 ,8773.420,285.79,366.45,321.81
XS GIS Cut Line= 6
1623866.70647781717404.9034939861623921.73421849716602.095263317
 1623925.9636752716538.6534127891623917.20649804716396.923089787
1623874.60220622716248.1097214671623840.44646728716039.382946432
#Sta/Elev= 30
       0  120.08   91.21  117.24  280.66  114.86  399.94  112.03  442.03  110.01
  484.13   110.5   512.2  109.92  519.22  109.73  540.26  107.18  666.56  107.53
  680.59  109.25  708.66  109.08  736.72  109.77  750.76  108.83  771.81  104.86
  778.82  104.11  804.69  103.72  817.27  102.52  832.75   99.89  839.77  100.45
  848.99  102.52   853.8  103.39  875.29  104.24  945.42  103.97 1032.12  105.29
 1075.81  108.63 1112.21  113.53 1172.16   118.2 1200.53  119.67 1376.57  126.02
#Mann= 3 , 0 , 0
       0      .1       0  817.27    .045       0  848.99      .1       0
#XS Ineff= 2 , 0
                          875.04          104.21
Permanent Ineff=
       F       F
Bank Sta=817.27,848.99
XS Rating Curve= 0 ,0
Exp/Cntr=0.3,0.1

Type RM Length L Ch R = 1 ,8406.976,289.61,336.81,294.78
XS GIS Cut Line= 4
1624088.68057877717364.1691031161624121.06528704716444.066682845
1624132.81662254 716377.475781621624042.44654825715992.922927797
#Sta/Elev= 30
       0  120.03   98.06  118.41  119.07   117.2  140.09   117.6  189.12  116.88
  364.23  112.82  385.24  111.88  406.25  112.77  420.26  111.49  441.27   107.2
  686.42  107.11  707.44     109  721.45  107.73  777.48  105.33  819.51  102.79
  903.56  102.91  920.67  102.15     938  100.39   949.1   98.44  956.21   97.94
  963.32   98.35  977.54  100.41 1009.86  103.65 1045.82  104.75  1060.2  105.84
 1103.34     111 1168.06  117.23 1225.58  119.27 1275.92  122.68 1383.32   125.9
#Mann= 3 , 0 , 0
       0      .1       0     938    .045       0  977.54      .1       0
#XS Ineff= 2 , 0
          886.03  102.82
Permanent Ineff=
       F       F
Bank Sta=938,977.54
XS Rating Curve= 0 ,0
Exp/Cntr=0.3,0.1

Type RM Length L Ch R = 1 ,8070.164,324.2,348.93,327.13
XS GIS Cut Line= 4
1624371.17534061717333.6612235011624412.62727264716538.178908676
1624394.86215891716360.5277713841624280.37587042715940.284136593
#Sta/Elev= 30
       0  119.03   35.05  117.79   63.09  117.13   98.13  116.94  140.19  115.53
   224.3   113.7  357.48  109.41  469.64  108.15  497.67  107.31  574.78  106.54
  623.85  105.59  686.93  105.07  817.67   101.2  845.81  100.83  873.95  101.02
  902.09   99.37  923.19   97.47   944.3   98.58  947.89   99.37   965.4   103.1
  982.35  105.65 1033.14  108.25 1083.93  112.68 1163.73  116.49 1207.26  117.33
 1229.03   118.5 1250.79  118.82 1345.11  122.12 1388.64  122.98 1410.66  124.04
#Mann= 3 , 0 , 0
       0      .1       0  902.09    .045       0  947.89      .1       0
Bank Sta=902.09,947.89
XS Rating Curve= 0 ,0
Exp/Cntr=0.3,0.1

Type RM Length L Ch R = 1 ,7721.224,337.92,387.71,372.29
XS GIS Cut Line= 4
1624600.23782493717275.6721428631624734.20071556716499.172119826
1624708.37991008716308.0981593731624377.09704521 715655.84492676
#Sta/Elev= 30
       0  118.11   56.83  115.65  120.76  113.75  362.27  109.83  390.69  108.63
  468.83  106.74  589.58  105.19  639.31  103.13  681.93  103.03  767.17  101.05
  816.23   98.74  837.42  100.11  858.61   98.56  872.73   96.28  886.86   97.15
  895.27   98.56  900.99   99.28  929.24   100.6  980.78  100.31 1051.44  104.53
  1122.1   110.1 1224.17  114.19 1318.38  115.29 1365.49  114.35 1404.75  114.92
 1475.41  114.27 1561.77  115.71 1593.17  117.49 1679.54  118.03 1712.35  118.93
#Mann= 3 , 0 , 0
       0      .1       0  858.61    .045       0  895.27      .1       0
#XS Ineff= 2 , 0
                          929.21          100.54
Permanent Ineff=
       F       F
Bank Sta=858.61,895.27
XS Rating Curve= 0 ,0
Exp/Cntr=0.3,0.1

Type RM Length L Ch R = 1 ,7333.513,342.11,582.53,499.45
XS GIS Cut Line= 6
1624780.67816538717346.0945392851625040.56964803716388.128311947
1625044.27576084716257.8848920461625032.43235168716208.537353903
1625036.38015474716123.6595883071625160.73595087715638.079813018
#Sta/Elev= 30
       0   118.1  203.08  113.04  471.45  108.83   587.5  106.47  616.51   106.3
  703.54  104.07  754.32  102.18  899.38   98.84  986.41   98.65 1027.61   97.78
 1111.64   98.83 1122.89   98.48  1133.4    97.2 1144.49   95.43 1151.69   94.94
 1158.88   95.45 1169.99   97.21 1173.64   97.71 1194.66    97.9 1215.68   99.86
 1280.29  104.06 1301.96  104.94 1338.09  107.18 1359.77  107.86 1381.45  109.25
 1446.48  111.18 1554.87   112.7 1663.26  117.15 1721.07   118.9 1759.86     119
#Mann= 3 , 0 , 0
       0      .1       0  1133.4    .045       0 1169.99      .1       0
Bank Sta=1133.4,1169.99
XS Rating Curve= 0 ,0
Exp/Cntr=0.3,0.1

Type RM Length L Ch R = 1 ,6750.995,371.7,485.91,458.22
XS GIS Cut Line= 6
1624967.45563804717413.5011210141625217.98400529716672.247085944
1625367.78447232716401.0565852971625432.35363917716346.818485156
1625489.17450593716269.3354849821625548.57813941716093.707351223
#Sta/Elev= 30
       0  117.17  140.39  114.62  221.67     112   332.5  110.03  354.67  110.07
  591.12  105.74  657.62  104.09  798.44  102.99   894.4  100.37  942.38   98.23
  958.38   97.98  974.37   96.93 1046.35   95.99 1062.34   96.88 1078.33   96.77
 1092.26      96 1110.54   96.91 1119.69   96.68 1123.88   95.92 1137.97   93.47
 1154.99   95.93 1165.39   97.11 1202.63   96.66 1219.99   97.25 1228.67   98.44
 1246.03  102.41 1287.45  106.49 1368.73   109.2 1413.07  110.04 1458.07  111.86
#Mann= 3 , 0 , 0
       0      .1       0 1123.88     .04       0 1154.99      .1       0
Bank Sta=1123.88,1154.99
XS Rating Curve= 0 ,0
Exp/Cntr=0.3,0.1

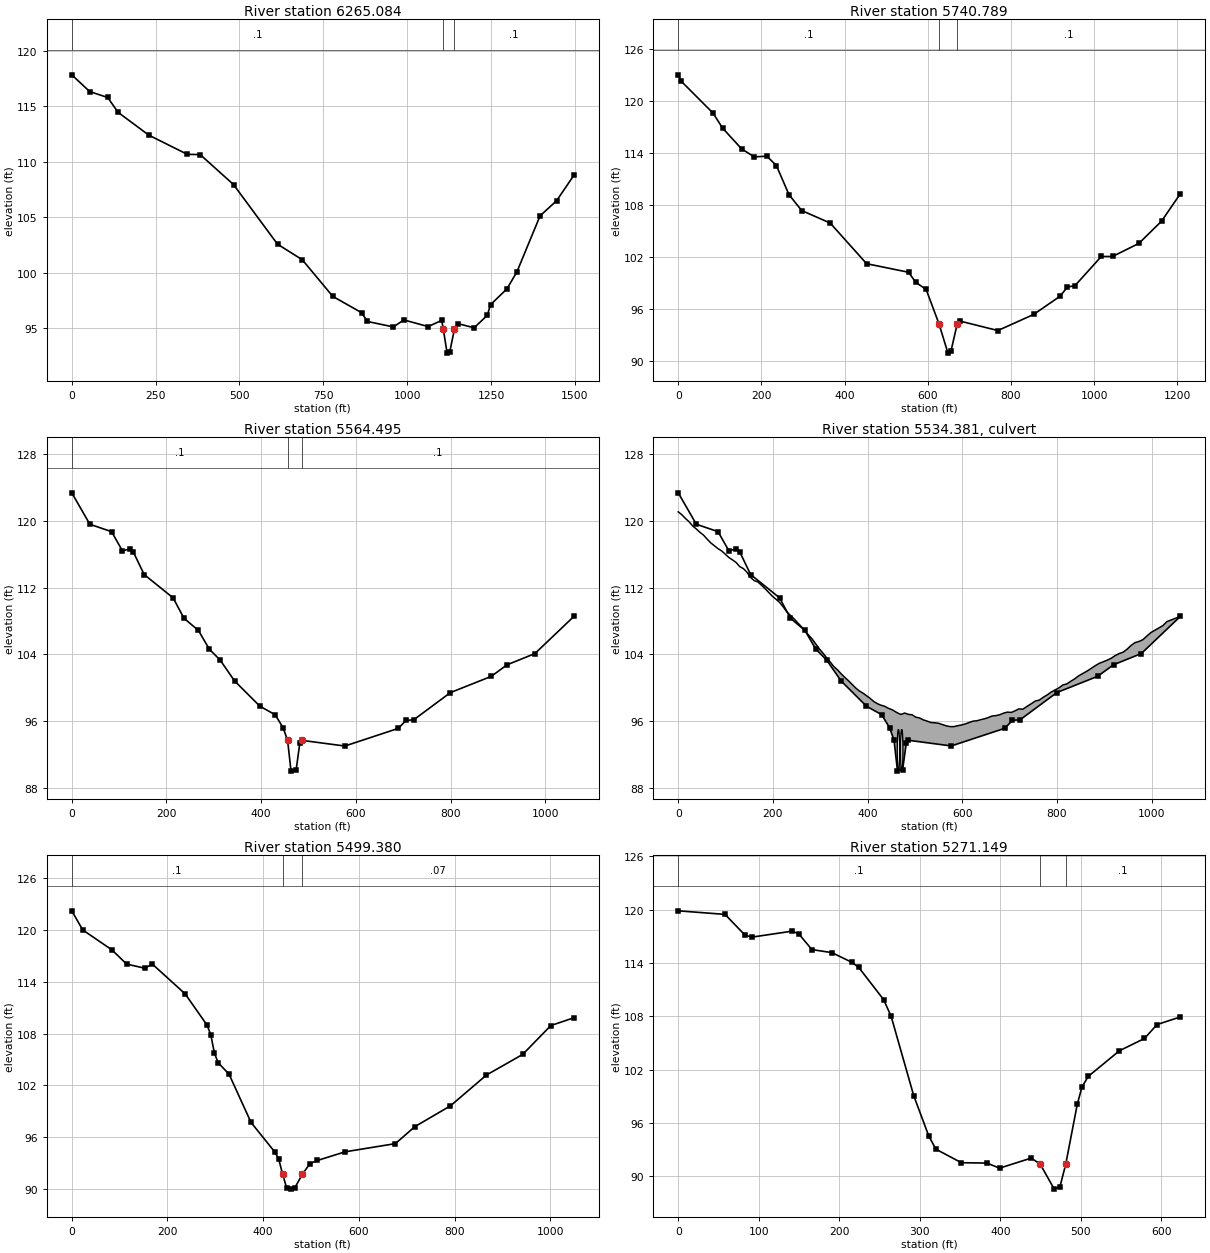
Type RM Length L Ch R = 1 ,6265.084,333.85,524.3,403.46
XS GIS Cut Line= 6
1625130.01204956717447.6767612251625308.38083886717044.165486813
 1625465.9296059716785.8888195311625653.36890958716652.093148291
1625857.76604451716535.9764879791626059.96594059716331.321885139
#Sta/Elev= 30
       0  117.82   53.57  116.31  107.15  115.78  137.76  114.45   229.6  112.39
   344.4  110.66  382.67  110.64  482.17  107.94  613.37  102.57  687.16  101.17
  778.12   97.87  864.12    96.4  881.32   95.61  958.72   95.12  990.11   95.75
 1062.56   95.15 1102.82   95.71 1107.62   94.92 1118.92   92.76 1126.97   92.88
  1140.8   94.92 1151.12   95.42 1199.43   95.04  1238.6   96.16 1248.44   97.12
 1297.65   98.56 1327.17  100.09 1396.05  105.12 1445.25  106.48 1496.78  108.77
#Mann= 3 , 0 , 0
       0      .1       0 1107.62     .04       0  1140.8      .1       0
Bank Sta=1107.62,1140.8
XS Rating Curve= 0 ,0
Exp/Cntr=0.3,0.1

Type RM Length L Ch R = 1 ,5740.789,196.95,176.29,134.2
XS GIS Cut Line= 6
1625374.90437642717555.2363528161625539.50472043717169.762042955
1625642.20408033717016.4164233361625718.17346989716988.279612407
1625832.12755416716888.3939335791626067.06992549716601.398462027
#Sta/Elev= 30
       0  122.98    7.61  122.22   83.73  118.57  106.56  116.85  152.23  114.46
  182.68  113.53  213.12  113.61  235.96  112.53   266.4  109.17  296.85  107.35
  365.35  105.91  452.85  101.23  553.94  100.24  570.79    99.1  596.07   98.26
  626.89   94.31  648.49   90.93  655.96   91.21  670.89   94.32  678.35   94.61
  768.49   93.53  854.34   95.38  917.67   97.47  935.76   98.54  953.86    98.7
 1017.18  102.06 1044.32  102.06 1107.64  103.57 1161.92  106.12 1207.15  109.28
#Mann= 3 , 0 , 0
       0      .1       0  626.89     .04       0  670.89      .1       0
Bank Sta=626.89,670.89
XS Rating Curve= 0 ,0
Exp/Cntr=0.5,0.3

Type RM Length L Ch R = 1 ,5564.495,65.35,65.11,67.63
BEGIN DESCRIPTION:
Center of channel lowered 2.0 ft based on bridge survey info. and photos.
END DESCRIPTION:
XS GIS Cut Line= 6
1625582.94438322717573.5637825731625755.42783862717180.068817154
 1625775.6201033 717149.804327981625803.91959272 717094.38449432
1625914.27546419716902.2567313161626084.28797071716642.476476654
#Sta/Elev= 30
       0  123.39   38.21  119.62   84.07  118.73     107  116.43  122.29  116.66
  129.93   116.3  152.86  113.59     214  110.79  236.93  108.35   267.5  106.88
  290.43  104.64  313.36  103.33  343.93  100.82  397.43   97.79  429.64   96.77
  446.47   95.19  455.82   93.69  463.02   90.01  473.88   90.18  481.74   93.43
  486.04    93.7  576.68   93.02   689.7   95.14  705.84    96.1  721.99   96.16
  799.65   99.43   885.6  101.37  919.22  102.76  978.05  104.11 1060.29  108.56
#Mann= 3 , 0 , 0
       0      .1       0  455.82     .04       0  486.04      .1       0
Bank Sta=455.82,486.04
XS Rating Curve= 0 ,0
Exp/Cntr=0.5,0.3

Type RM Length L Ch R = 2 ,5534.381,,,
BEGIN DESCRIPTION:
Deaver Road, MDE Bridge #: CE050207FS-4
Top of road obtained from DEM.
Opening from MDE2 bridge/culvert surveys.
END DESCRIPTION:
Bridge Culvert--1,0,-1,-1, 0
Deck Dist Width WeirC Skew NumUp NumDn MinLoCord MaxHiCord MaxSubmerge Is_Ogee
23.1,19,2.6,0, 131, 132, , , 0.95, 0, 2,2,,
       0    7.64   15.29   22.93   30.57   38.21   45.86    53.5   61.14   68.79
   76.43   84.07   91.72   99.36     107  114.64  122.29  129.93  137.57  145.22
  152.86   160.5  168.15  175.79  183.43  191.07  198.72  206.36     214  221.65
  229.29  236.93  244.57  252.22  259.86   267.5  275.15  282.79  290.43  298.08
  305.72  313.36     321  328.65  336.29  343.93  351.58  359.22  366.86  374.51
  382.15  389.79  397.43  405.08  412.72  420.36     427  435.42  443.83  452.25
   462.5  470.35  478.21  486.07  493.93  501.79  509.65  517.51  525.73   533.8
  541.87  549.95  558.02  566.09  574.16  582.24  590.31  598.38  606.45  614.53
   622.6  630.67  638.74  646.82  654.89  662.96  671.04  679.11  687.18  695.25
  703.33   711.4  719.47  727.54  735.62  745.85  754.16  762.46  770.77  779.07
  787.38  795.69  803.99   812.3   820.6  828.91  837.21  845.52  853.82  863.85
  872.26  880.66  889.06  897.47  905.87  914.28  922.68  931.09  939.49  947.89
   956.3   964.7  973.11  981.51  989.92  998.32 1006.72 1015.13 1023.53 1031.94
 1060.29
  121.11  120.76  120.31  119.92  119.41  119.05  118.65  118.31  117.83  117.38
  117.04  116.69  116.42  116.02  115.63  115.34  115.03  114.53   114.3  113.86
  113.23  112.86   112.7  112.31  111.89  111.44  110.99  110.63  110.24  109.71
  109.11  108.68  108.27   107.8  107.34  106.84  106.33  105.86  105.25  104.66
  104.15   103.6  103.09  102.54  102.16  101.68  101.26  100.86  100.42   99.99
   99.63   99.37   99.05   98.74   98.36    98.1   97.93   97.79   97.54   97.35
      97    96.8   96.97   96.81   96.76   96.47   96.38   96.15      96   95.83
    95.8   95.74   95.59   95.43   95.34   95.34   95.45   95.54   95.67   95.84
      96   96.04   96.17   96.28   96.43   96.62   96.66   96.77   96.96   97.08
   97.04   97.24   97.47   97.43   97.73   98.12   98.41   98.52   98.86   99.14
   99.48   99.74   99.99  100.34  100.46  100.78  101.07  101.43   101.7  102.02
  102.34  102.65  102.93  103.12  103.31  103.54  103.86   104.1  104.27  104.63
  105.08  105.42  105.56  105.78  106.22  106.63  106.91   107.2  107.46  107.94
  108.56
                                                                                
                                                                                
                                                                                
                                                                                
                                                                                
                                                                                
                                                                                
                                                                                
                                                                                
                                                                                
                                                                                
                                                                                
                                                                                
        
       0    7.64   15.29   22.93   30.57   38.21   45.86    53.5   61.14   68.79
   76.43   84.07   91.72   99.36     107  114.64  122.29  129.93  137.57  145.22
  152.86   160.5  168.15  175.79  183.43  191.07  198.72  206.36     214  221.65
  229.29  236.93  244.57  252.22  259.86   267.5  275.15  282.79  290.43  298.08
  305.72  313.36     321  328.65  336.29  343.93  351.58  359.22  366.86  374.51
  382.15  389.79  397.43  405.08  412.72  420.36     427  435.42  443.83  452.25
   462.5  470.35  478.21  486.07  493.93  501.79  509.65  517.51  525.73   533.8
  541.87  549.95  558.02  566.09  574.16  582.24  590.31  598.38  606.45  614.53
   622.6  630.67  638.74  646.82  654.89  662.96  671.04  679.11  687.18  695.25
  703.33   711.4  719.47  727.54  735.62  745.85  754.16  762.46  770.77  779.07
  787.38  795.69  803.99   812.3   820.6  828.91  837.21  845.52  853.82  863.85
  872.26  880.66  889.06  897.47  905.87  914.28  922.68  931.09  939.49  947.89
   956.3   964.7  973.11  981.51  989.92  998.32 1006.72 1015.13 1023.53 1031.94
 1040.34 1048.75
  121.11  120.76  120.31  119.92  119.41  119.05  118.65  118.31  117.83  117.38
  117.04  116.69  116.42  116.02  115.63  115.34  115.03  114.53   114.3  113.86
  113.23  112.86   112.7  112.31  111.89  111.44  110.99  110.63  110.24  109.71
  109.11  108.68  108.27   107.8  107.34  106.84  106.33  105.86  105.25  104.66
  104.15   103.6  103.09  102.54  102.16  101.68  101.26  100.86  100.42   99.99
   99.63   99.37   99.05   98.74   98.36    98.1   97.93   97.79   97.54   97.35
      97    96.8   96.97   96.81   96.76   96.47   96.38   96.15      96   95.83
    95.8   95.74   95.59   95.43   95.34   95.34   95.45   95.54   95.67   95.84
      96   96.04   96.17   96.28   96.43   96.62   96.66   96.77   96.96   97.08
   97.04   97.24   97.47   97.43   97.73   98.12   98.41   98.52   98.86   99.14
   99.48   99.74   99.99  100.34  100.46  100.78  101.07  101.43   101.7  102.02
  102.34  102.65  102.93  103.12  103.31  103.54  103.86   104.1  104.27  104.63
  105.08  105.42  105.56  105.78  106.22  106.63  106.91   107.2  107.46  107.94
  108.38  108.64
                                                                                
                                                                                
                                                                                
                                                                                
                                                                                
                                                                                
                                                                                
                                                                                
                                                                                
                                                                                
                                                                                
                                                                                
                                                                                
                
BR Coef=-1 , 0 , 0 ,, 0 ,,,0.8,0,,0,
WSPro=,,,, 1 ,,,, 0 ,,,, 0 ,,,,-1 ,-1 ,-1 , 0 , 0 , 0 , 0 , 0
Multiple Barrel Culv=1,5,,34,0.024,0.9,1,2,3,90,90, 2,Culvert #1  , 0 ,15.6
     465     455     472     462
Culvert Bottom n=0.024
BC Design=,, 0 ,, 0 ,,,,,,
BC Use User HTab Curves=0
BC User HTab FreeFlow(D)= 0

Type RM Length L Ch R = 1 ,5499.380,175.49,228.23,235.56
BEGIN DESCRIPTION:
Center of channel lowered 0.5 ft based on bridge survey info. and photos.
END DESCRIPTION:
XS GIS Cut Line= 6
1625642.47629476717599.6588300761625812.66724564717211.393867776
1625831.78937517717182.7333142011625861.08082753 717125.37088652
1625969.87974444716935.9537558851626138.42684178716678.448446885
#Sta/Elev= 30
       0  122.24   22.93  120.02   84.07   117.7  114.64  116.06  152.86  115.58
  168.15  116.07  236.93   112.6  282.79  108.97  290.43  107.86  298.08  105.73
  305.72  104.63  328.65  103.28  374.51   97.69  423.93   94.28  432.34   93.45
  440.41    91.7  449.17   90.05  458.38   89.95  466.24   90.13  481.96   91.69
  497.68   92.91   513.4   93.28  571.23   94.28  676.17   95.23  716.53   97.19
  791.06   99.61   866.5  103.19  942.13  105.58 1000.96  108.93    1049  109.83
#Mann= 3 , 0 , 0
       0      .1       0  440.41     .04       0  481.96     .07       0
Bank Sta=440.41,481.96
XS Rating Curve= 0 ,0
Exp/Cntr=0.5,0.3

Type RM Length L Ch R = 1 ,5271.149,147.46,206.29,170.77
XS GIS Cut Line= 6
 1625698.4850139717601.1484207661625830.58155972717393.938152805
1625886.26931928717344.7257141621625984.69419651717292.923147187
1626053.33259776717278.6774412691626163.41305263717225.579810083
#Sta/Elev= 30
       0  119.86   58.11  119.46   83.01  117.12   91.32   116.9  141.12  117.57
  149.43   117.3  166.03   115.5  190.93  115.16  215.84  114.06  224.14   113.5
  255.08  109.88  264.42     108  292.44   99.09  311.13   94.55  320.05   93.06
  351.69   91.54  383.33    91.5  399.15   90.93  438.43   92.06  449.58   91.38
  467.02   88.57  474.17   88.86  481.32   91.39  495.62   98.11  501.38  100.03
  509.15  101.24  548.01  104.13   579.1  105.51  594.64  107.07  623.59  107.93
#Mann= 3 , 0 , 0
       0      .1       0  449.58     .04       0  481.32      .1       0
Bank Sta=449.58,481.32
XS Rating Curve= 0 ,0
Exp/Cntr=0.3,0.1