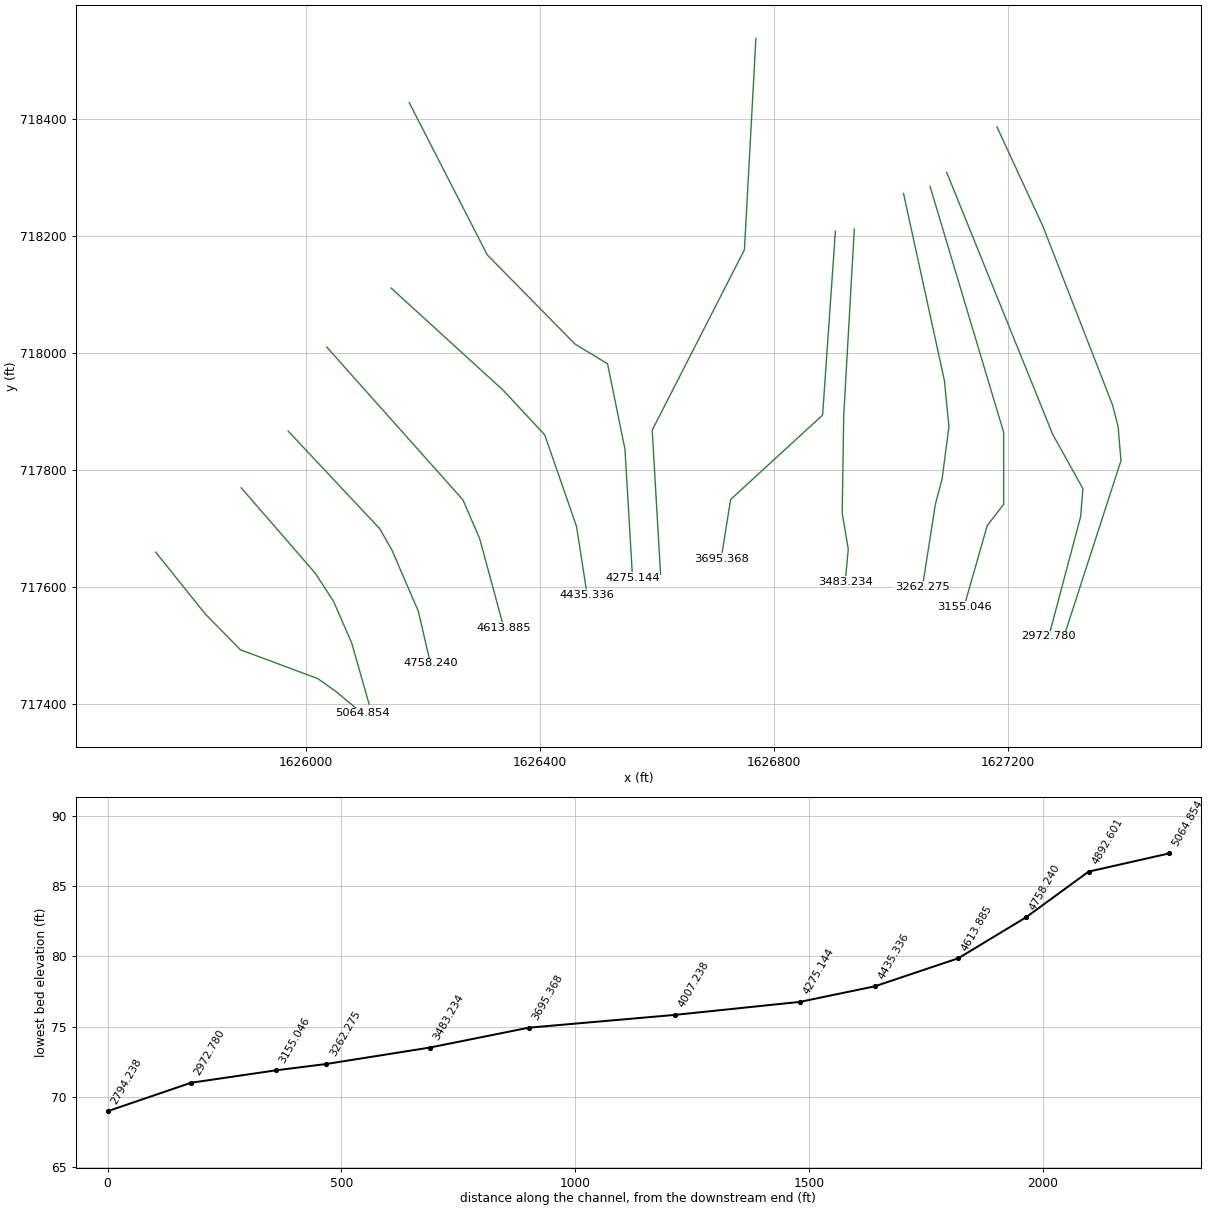
HEC-RAS study WestBranchLaurelRun.prj: West Br Laurel Run

--- WestBranchLaurelRun.g01 (geometry) --- (continued)

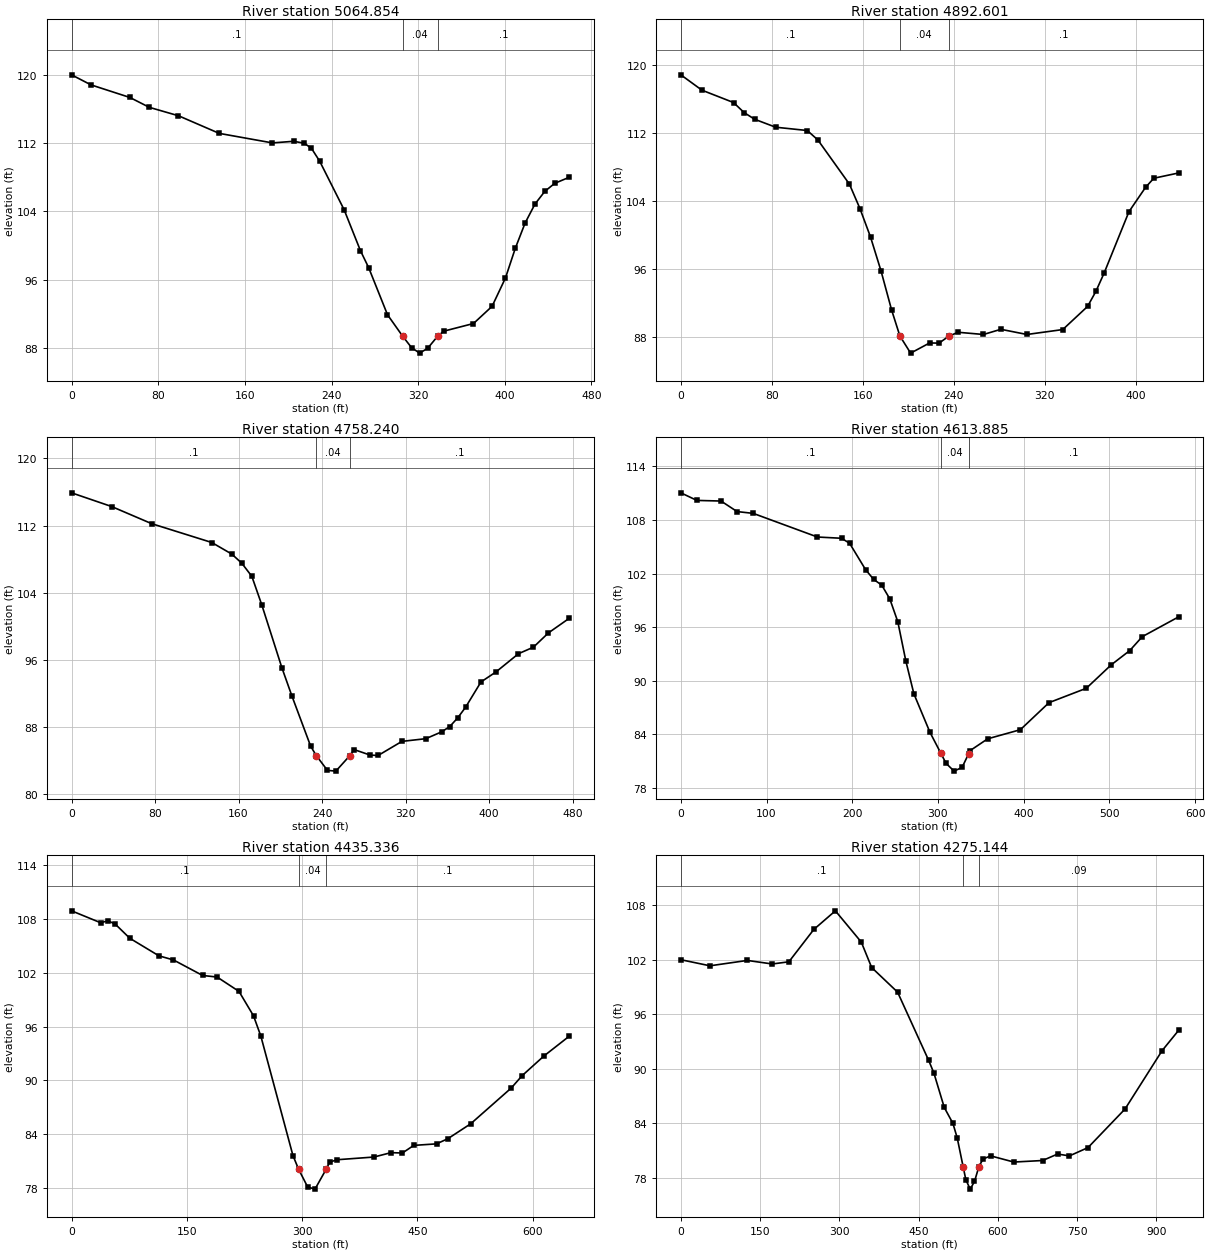
Type RM Length L Ch R = 1 ,5064.854,174.14,172.25,127.45
XS GIS Cut Line= 6
1625742.51719582717659.4263086021625827.86397104717553.083962351
1625887.56438342717492.3630300911626019.66092923717443.150591448
 1626050.7424694717421.1345004591626096.06971553717383.577639416
#Sta/Elev= 30
       0  120.05   17.95  118.87   53.85  117.39    71.8  116.23   98.73  115.24
  136.36  113.17  185.44  112.05  205.07  112.24  214.89  112.01  221.51  111.41
  229.05  109.91  251.67  104.19  266.74   99.38  274.28    97.4  291.69   91.86
  305.86   89.31  313.95   87.99  321.37   87.35  328.79   87.92  337.89   89.32
  343.62   89.93  371.09   90.83  388.24   92.85   400.6   96.18  409.69   99.67
  418.78  102.65  427.87  104.87  436.96  106.36  446.05   107.3  459.46  108.01
#Mann= 3 , 0 , 0
       0      .1       0  305.86     .04       0  337.89      .1       0
Bank Sta=305.86,337.89
XS Rating Curve= 0 ,0
Exp/Cntr=0.3,0.1

Type RM Length L Ch R = 1 ,4892.601,134.59,134.36,135.74
XS GIS Cut Line= 5
1625888.85944757717769.5067634731626015.77573673717623.164511725
1626046.85727692717575.2471372781626077.93881708717504.018607661
1626107.72529311  717399.1184095
#Sta/Elev= 30
       0  118.88   18.53  117.07   46.33  115.61   55.59  114.43   64.86  113.64
   83.39   112.7  111.19  112.31  120.46   111.2  148.25  105.98  157.52  103.09
  166.78   99.75  176.05   95.73  185.32   91.14   192.6   88.07  202.05   86.05
  218.74   87.25  227.09   87.23  235.43   88.04  243.77   88.51   266.1   88.25
  281.38   88.86  304.29   88.25  335.82   88.83  357.65   91.56  364.92   93.33
   372.2    95.5  394.03  102.74  408.58   105.6  415.86  106.68  437.59   107.3
#Mann= 3 , 0 , 0
       0      .1       0   192.6     .04       0  235.43      .1       0
Bank Sta=192.6,235.43
XS Rating Curve= 0 ,0
Exp/Cntr=0.3,0.1

Type RM Length L Ch R = 1 ,4758.240,140.27,144.35,148.81
XS GIS Cut Line= 5
1625969.15342641717866.6365765781626125.85619156717699.573298022
1626146.57721834717663.3115011451626191.90446445717558.411302999
1626212.62549125717469.051874936
#Sta/Elev= 30
       0  115.89   38.39  114.26   76.78  112.22  134.36  109.98  153.56   108.6
  163.16  107.51  172.75  105.95  182.35  102.53  201.55   95.07  211.14   91.72
  229.05   85.76  234.45   84.63  245.18   82.87  253.24   82.78   266.6   84.62
  270.82   85.34  286.07   84.69   293.7   84.64  316.57   86.32  339.45   86.64
   354.7   87.46  362.33   88.08  369.95   89.11  377.58   90.39  392.28   93.39
  406.65   94.58  428.21   96.75  442.58   97.53  456.95   99.23  476.82  100.96
#Mann= 3 , 0 , 0
       0      .1       0  234.45     .04       0   266.6      .1       0
Bank Sta=234.45,266.6
XS Rating Curve= 0 ,0
Exp/Cntr=0.3,0.1

Type RM Length L Ch R = 1 ,4613.885,177.51,178.55,179.31
XS GIS Cut Line= 4
1626035.20169932718010.3886999491626268.31325075717748.785736665
1626296.80466263717682.737463757 1626338.2467162717529.919891134
#Sta/Elev= 30
       0  111.04   18.75  110.19   46.88  110.12   65.63  108.94   84.38  108.74
  159.39  106.09  187.52  105.95  196.89  105.39  215.65  102.42  225.02  101.34
   234.4   100.7  243.77   99.17  253.15    96.6  262.53    92.2   271.9   88.53
  290.65   84.22  303.47   81.85  309.41   80.75  318.78   79.87  328.16   80.29
  335.91   81.84  337.53   82.17  358.02   83.49  396.14   84.51  429.58   87.54
   473.1   89.15  502.11   91.77  523.87   93.38  538.37   94.93  580.66   97.14
#Mann= 3 , 0 , 0
       0      .1       0  303.47     .04       0  335.91      .1       0
Bank Sta=303.47,335.91
XS Rating Curve= 0 ,0
Exp/Cntr=0.3,0.1

Type RM Length L Ch R = 1 ,4435.336,149.14,160.19,143.99
XS GIS Cut Line= 5
1626145.28215419718111.4037055821626336.95165206717936.570041999
1626408.18018165717860.1612557021626462.57287697717703.458490565
1626480.70377541717586.902714849
#Sta/Elev= 30
       0  108.92    37.9  107.59   47.37  107.81   56.85  107.44    75.8  105.86
   113.7   103.9  132.65  103.44  170.54  101.71  189.49  101.53  217.92   99.93
  236.87    97.2  246.34   94.95  288.14   81.62   295.4   80.11  307.28   78.11
  316.85   77.87  331.53   80.11  335.99   80.88  345.56   81.15  393.53   81.45
  415.76   81.94  430.58    81.9   445.4   82.75  475.04   82.92  489.85    83.5
  519.49   85.16  572.27   89.15  586.44   90.53  614.77   92.72  647.72   94.93
#Mann= 3 , 0 , 0
       0      .1       0   295.4     .04       0  331.53      .1       0
Bank Sta=295.4,331.53
XS Rating Curve= 0 ,0
Exp/Cntr=0.3,0.1

Type RM Length L Ch R = 1 ,4275.144,254.79,267.91,95.4
XS GIS Cut Line= 6
1626176.36369437718428.5649219751626309.75530438718168.257022858
1626459.98274861718015.4394502341626515.67050813 717981.76778169
1626545.45698416717835.425529942 1626558.4076259717615.394126683
#Sta/Elev= 30
       0  102.01   55.06  101.34  125.85  101.93  173.04  101.54   204.5  101.78
   251.7  105.34   292.5  107.39  341.58  103.95  361.21  101.15  410.29   98.44
  469.18   90.92     479   89.54  498.63   85.75  514.97      84  523.15    82.4
  534.37   79.22  539.51   77.79  547.69   76.76  555.87    77.6  564.05   79.21
  571.86   80.07  586.47   80.42   630.3   79.74  684.83   79.91  713.09   80.62
  735.66   80.42  770.72   81.33  840.85   85.58  910.97      92  942.05   94.22
#Mann= 3 , 0 , 0
       0      .1       0  534.37     .04       0  564.05     .09       0
Bank Sta=534.37,564.05
XS Rating Curve= 0 ,0
Exp/Cntr=0.3,0.1

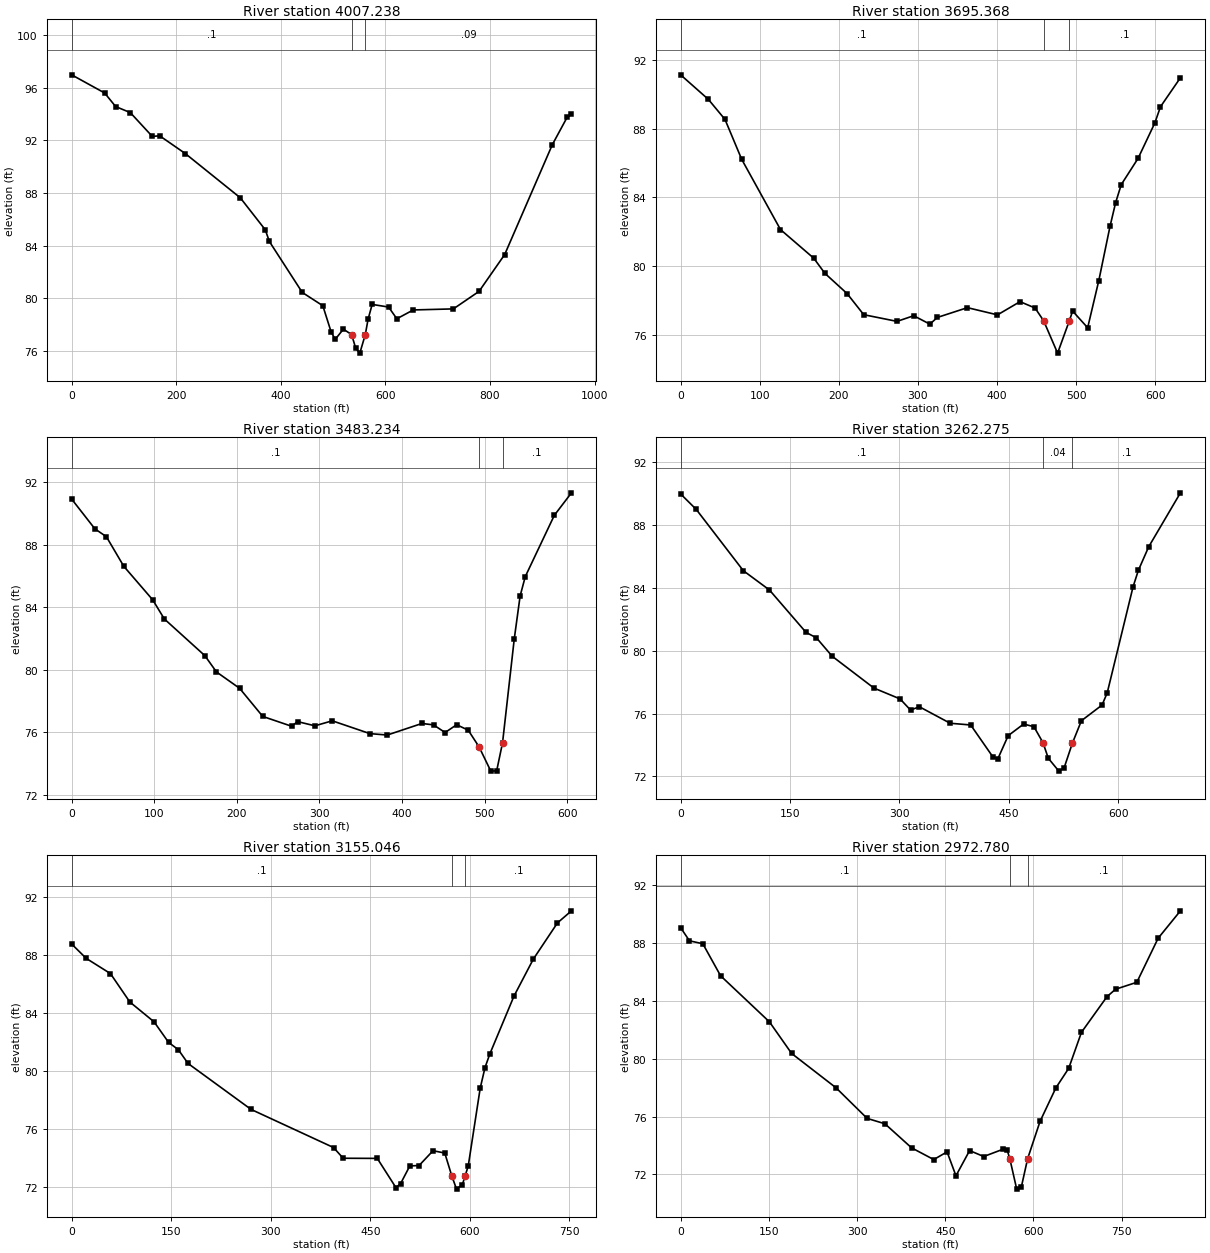
Type RM Length L Ch R = 1 ,4007.238,263.04,311.87,220.62
XS GIS Cut Line= 4
1626769.50308634718538.6453768161626749.83548801718176.783787072
1626592.05130591717868.2280531821626606.32500036717621.739941135
#Sta/Elev= 30
       0   96.97   63.09   95.59   84.12   94.56  112.17    94.1  154.23   92.29
  168.25   92.34  217.32   90.99  322.48   87.63  370.26    85.2  378.12   84.31
  441.02   80.44  480.33   79.43  496.05   77.46  503.91   76.87  519.64   77.65
  535.36   77.24  543.22    76.2  551.09   75.83  561.57   77.24  566.81   78.39
  574.67   79.53  606.12   79.33  621.85   78.44  653.29   79.11  729.99   79.19
  779.07   80.52  828.15   83.32   919.3   91.67  947.35   93.73  955.85   93.96
#Mann= 3 , 0 , 0
       0      .1       0  535.36     .04       0  561.57     .09       0
Bank Sta=535.36,561.57
XS Rating Curve= 0 ,0
Exp/Cntr=0.3,0.1

Type RM Length L Ch R = 1 ,3695.368,95.58,212.14,224.72
XS GIS Cut Line= 4
 1626905.4848247718208.4040122781626883.59913404717894.028745949
1626726.21490824717749.5448664871626709.93013434717647.641224623
#Sta/Elev= 30
       0   91.14   35.08   89.71   56.14   88.54   77.19   86.22   126.3   82.12
  168.41   80.45  182.44   79.57  210.51   78.39  231.56   77.16  273.66   76.77
  294.71    77.1  315.14   76.61  324.64      77  362.65   77.57  400.66   77.15
  429.17   77.92  448.17   77.55  458.98   76.81  476.68   74.92  491.55   76.81
  495.68   77.37  514.69    76.4  528.78   79.15  542.96   82.31  550.05   83.69
  557.14   84.74  578.41   86.27  599.67   88.34  606.76   89.28  631.98   90.97
#Mann= 3 , 0 , 0
       0      .1       0  458.98     .04       0  491.55      .1       0
Bank Sta=458.98,491.55
XS Rating Curve= 0 ,0
Exp/Cntr=0.3,0.1

Type RM Length L Ch R = 1 ,3483.234,174.87,220.96,167.28
XS GIS Cut Line= 5
1626937.86142908718212.2892047761626919.73053065717893.703417823
 1626917.1404023717726.6401392971626927.50091569717664.477058887
  1626922.320659717608.789299399
#Sta/Elev= 30
       0   90.91   28.05   89.01   42.07    88.5    63.1   86.61   98.16   84.46
  112.18   83.24  161.26   80.89  175.28   79.85  203.33    78.8  231.37      77
  266.43   76.37  273.44   76.67  294.48    76.4  315.51   76.72  361.11    75.9
  382.11   75.81  424.11   76.55  438.12   76.46  452.12   75.97  466.12   76.47
  480.12   76.12  493.28   75.05  507.47    73.5  514.57   73.52  521.67   75.31
  535.86   81.96  542.96   84.71  549.21   85.95  584.36   89.87  605.13   91.31
#Mann= 3 , 0 , 0
       0      .1       0  493.28     .04       0  521.67      .1       0
Bank Sta=493.28,521.67
XS Rating Curve= 0 ,0
Exp/Cntr=0.3,0.1

Type RM Length L Ch R = 1 ,3262.275,106.11,107.25,98.67
XS GIS Cut Line= 6
1627022.04060042718273.1572210041627091.97406587717953.276369855
1627099.74445093717874.2774552111627088.08887339717784.918027148
1627076.43329579717740.885845199 1627054.4172048717599.723850176
#Sta/Elev= 30
       0   89.99    21.5      89   85.98    85.1  121.81   83.87  171.97   81.17
   186.3   80.82  207.79   79.65  265.12   77.62  300.94   76.93  315.27   76.22
  327.44   76.43  369.64   75.38  397.77   75.27  427.99   73.25  435.05   73.12
  449.17   74.59  470.35   75.33  484.47   75.16  496.93   74.14  504.17   73.15
  518.66   72.33   525.9   72.54  537.11    74.1  549.56   75.54  577.89   76.54
  584.98   77.32  620.39   84.07  627.65   85.12  641.83   86.62  685.35   90.06
#Mann= 3 , 0 , 0
       0      .1       0  496.93     .04       0  537.11      .1       0
Bank Sta=496.93,537.11
XS Rating Curve= 0 ,0
Exp/Cntr=0.3,0.1

Type RM Length L Ch R = 1 ,3155.046,81.82,182.25,180.82
XS GIS Cut Line= 5
1627067.49027941 718285.205849291627193.48655081717864.113047615
1627193.48655081717741.4324676251627165.30317429717704.959862739
1627125.51487808717565.700825974
#Sta/Elev= 30
       0   88.79   21.92    87.8   58.45   86.75   87.68   84.79  124.21   83.42
  146.13      82  160.75    81.5  175.36   80.55  270.35   77.38  394.56   74.75
  409.17   74.01  460.54      74  488.54   71.99  495.54   72.25  509.54   73.48
  523.54   73.51  544.54   74.53  562.22   74.37  572.61   72.82  579.91   71.88
  588.76   72.19  592.87   72.79   597.6   73.48  615.59   78.84  622.87   80.27
  630.15   81.21  666.55    85.2  695.67   87.75  732.07   90.25  753.14   91.08
#Mann= 3 , 0 , 0
       0      .1       0  572.61     .04       0  592.87      .1       0
Bank Sta=572.61,592.87
XS Rating Curve= 0 ,0
Exp/Cntr=0.3,0.1

Type RM Length L Ch R = 1 ,2972.780,113.51,178.55,133.3
XS GIS Cut Line= 5
1627095.85925837718309.4190178811627277.16824284717861.326813445
1627328.97080986717768.082192883 1627325.0856173717720.164818421
  1627270.692922717515.544678807
#Sta/Elev= 30
       0   89.03    15.1   88.12   37.76   87.92   67.96   85.71  151.03   82.53
  188.78   80.35   264.3   77.98  317.16   75.87  347.36    75.5  392.67   73.84
  430.42   73.03  453.08   73.56  468.18   71.91  491.39   73.65  515.41   73.24
  547.44   73.73  555.45   73.66   559.8   73.08  571.47   70.99  579.48   71.16
  590.05   73.09  611.12   75.66  638.13   77.98  659.85   79.32  681.58   81.81
  725.04   84.27  739.53   84.78  775.74   85.26  811.96    88.3  849.85   90.19
#Mann= 3 , 0 , 0
       0      .1       0   559.8     .04       0  590.05      .1       0
Bank Sta=559.8,590.05
XS Rating Curve= 0 ,0
Exp/Cntr=0.5,0.3

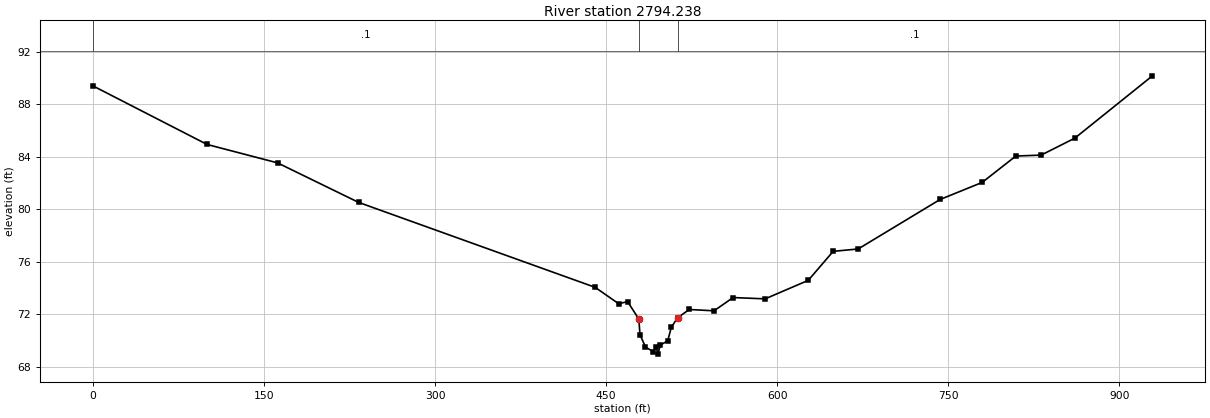
Type RM Length L Ch R = 1 ,2794.238,31.77,30.19,35.37
XS GIS Cut Line= 6
1627181.96282983718387.0467629731627260.77746734718216.497055516
 1627379.5969412717911.4686952081627389.24211611717874.093642503
1627394.08591048717815.9681097121627296.61124547717515.112586498
#Sta/Elev= 30
       0    89.4  100.25   84.93  161.94   83.53     233   80.52  440.32   74.05
  461.01    72.8  468.83   72.96  478.65   71.63  479.67   70.45  484.49    69.5
  491.13   69.16     494   69.47  495.41   68.96   497.4   69.65  504.01   69.97
  507.11      71  512.65   71.73  522.89   72.36  544.58   72.26  561.29   73.27
  589.38   73.17  627.17   74.58  649.04   76.79  670.91   76.97  742.74   80.74
  779.63   82.04  809.15   84.05  831.29   84.12  860.81   85.41  928.88   90.16
#Mann= 3 , 0 , 0
       0      .1       0  478.65     .04       0  512.65      .1       0
Bank Sta=478.65,512.65
XS Rating Curve= 0 ,0
Exp/Cntr=0.5,0.3