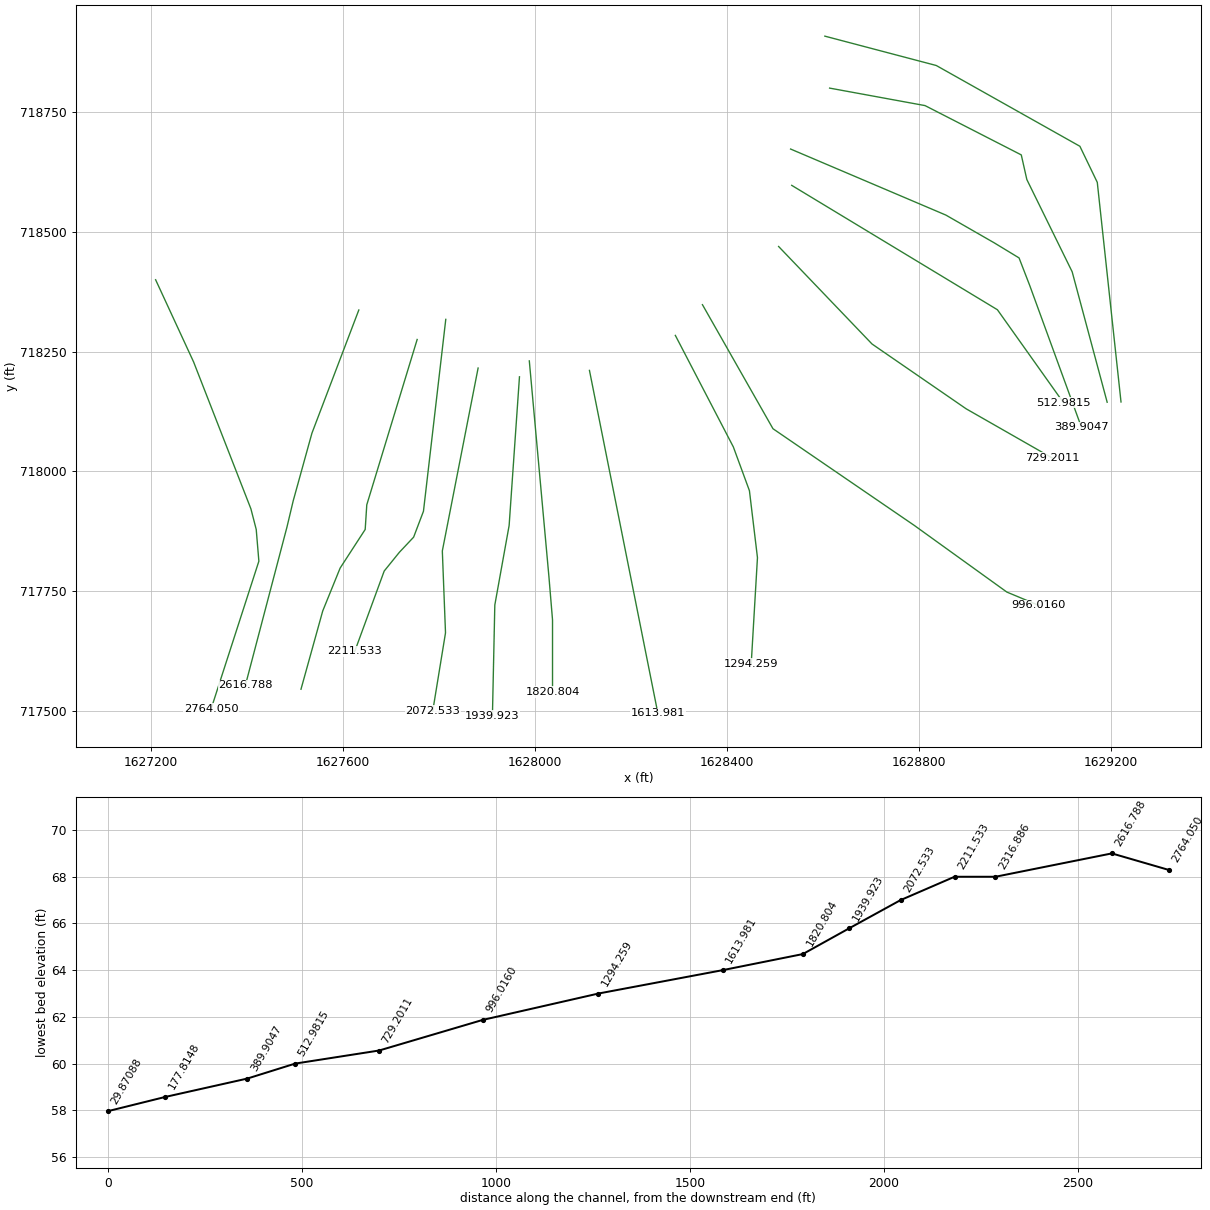
HEC-RAS study WestBranchLaurelRun.prj: West Br Laurel Run

--- WestBranchLaurelRun.g01 (geometry) --- (continued)

Type RM Length L Ch R = 2 ,2779.226,,,
BEGIN DESCRIPTION:
Morley Road, MDE Bridge #: CE050207FS-3
Top of road obtained from DEM.
Opening from MDE2 bridge/culvert surveys.
END DESCRIPTION:
Bridge Culvert--1,0,-1,-1, 0
Deck Dist Width WeirC Skew NumUp NumDn MinLoCord MaxHiCord MaxSubmerge Is_Ogee
9.6,11,2.6,0, 109, 111, , , 0.95, 0, ,,,
       0    7.71   15.42   23.13   30.85   38.56   46.27   53.98   61.69    69.4
   77.11   84.82   92.54  100.25  107.96  115.67  123.38  131.09   138.8  146.51
  154.23  161.94  169.65  177.36  188.32  195.84  203.36  210.88   218.4  225.92
  233.44  240.96  248.49  256.01  263.53  271.05  278.57  286.09  293.61  301.13
  308.65  316.17  323.69  331.21  338.74  346.26  353.78   361.3  368.82  376.34
  383.12  390.45  397.78  405.11  412.44  419.76  427.09  434.42  441.75  449.08
  456.41  461.77  469.59  516.79  600.39  607.42  614.44  620.63  627.92  635.21
   642.5  649.79  657.08  664.37  671.66  678.95  686.24  694.81  702.19  709.57
  716.95  724.33  731.71  739.09  746.47  753.84  761.22   768.6  775.98  783.36
  790.74  798.12   805.5  812.88  820.26  827.64  835.02   842.4  849.78  857.16
  864.54  871.92   879.3  886.67  894.05  901.43  908.81  916.19  923.57
   88.75    88.6    88.3   88.01   87.41   87.39   87.17   86.97    86.5    86.2
   85.77   85.46   85.17   84.86   84.75   84.28   84.01   83.75   83.82   83.64
   83.25   83.11   82.88    82.5    82.1   81.83   81.63   81.38   81.15   80.94
   80.46   80.17   80.03   79.73   79.43   79.27   79.05   78.78   78.52    78.3
   78.15   78.03   77.75   77.44   77.24   77.09   76.81   76.54   76.46   76.23
   75.88   75.65   75.44   75.25   75.16   75.12      75      75      75      75
      75      75      75      75   74.02   74.34   74.55   74.73   75.02   75.25
   75.46   75.73   75.84   75.98   76.52   76.78   77.26   77.62   77.55   77.73
   78.21   78.87   79.25   79.39    79.5   80.01   80.31   80.52   80.79   81.04
   81.22   81.46   81.86   82.07   82.46   82.77   83.13   83.39   83.79   84.08
   84.66   85.03   85.42    85.9   86.44   86.91   87.13   87.49   88.08
                                                                                
                                                                                
                                                                                
                                                                                
                                                                                
                                                                                
                                                                                
                                                                                
                                                                                
                                                                                
                                                                        
       0    7.71   15.42   23.13   30.85   38.56   46.27   53.98   61.69    69.4
   77.11   84.82   92.54  100.25  107.96  115.67  123.38  131.09   138.8  146.51
  154.23  161.94  169.65  177.36  188.32  195.84  203.36  210.88   218.4  225.92
  233.44  240.96  248.49  256.01  263.53  271.05  278.57  286.09  293.61  301.13
  308.65  316.17  323.69  331.21  338.74  346.26  353.78   361.3  368.82  376.34
  383.12  390.45  397.78  405.11  412.44  419.76  427.09  434.42  441.75  449.08
  456.41  461.77  469.59  516.79  600.39  607.42  614.44  620.63  627.92  635.21
   642.5  649.79  657.08  664.37  671.66  678.95  686.24  694.81  702.19  709.57
  716.95  724.33  731.71  739.09  746.47  753.84  761.22   768.6  775.98  783.36
  790.74  798.12   805.5  812.88  820.26  827.64  835.02   842.4  849.78  857.16
  864.54  871.92   879.3  886.67  894.05  901.43  908.81  916.19  923.57  930.95
  940.28
   88.75    88.6    88.3   88.01   87.41   87.39   87.17   86.97    86.5    86.2
   85.77   85.46   85.17   84.86   84.75   84.28   84.01   83.75   83.82   83.64
   83.25   83.11   82.88    82.5    82.1   81.83   81.63   81.38   81.15   80.94
   80.46   80.17   80.03   79.73   79.43   79.27   79.05   78.78   78.52    78.3
   78.15   78.03   77.75   77.44   77.24   77.09   76.81   76.54   76.46   76.23
   75.88   75.65   75.44   75.25   75.16   75.12      75      75      75      75
      75      75      75      75   74.02   74.34   74.55   74.73   75.02   75.25
   75.46   75.73   75.84   75.98   76.52   76.78   77.26   77.62   77.55   77.73
   78.21   78.87   79.25   79.39    79.5   80.01   80.31   80.52   80.79   81.04
   81.22   81.46   81.86   82.07   82.46   82.77   83.13   83.39   83.79   84.08
   84.66   85.03   85.42    85.9   86.44   86.91   87.13   87.49   88.08   88.45
   89.07
                                                                                
                                                                                
                                                                                
                                                                                
                                                                                
                                                                                
                                                                                
                                                                                
                                                                                
                                                                                
                                                                                
        
BR Coef=-1 , 0 , 0 ,, 0 ,,,0.8,0,,0,
WSPro=,,,, 1 ,,,, 0 ,,,, 0 ,,,,-1 ,-1 ,-1 , 0 , 0 , 0 , 0 , 0
Culvert=1,4,,21,0.024,0.9,1,2,3,69.3,485,68.7,485,Culvert #1  , 0 ,4.6
Culvert Bottom n=0.024
Multiple Barrel Culv=1,4,,21,0.024,0.9,1,2,3,69.3,68.7, 2,Culvert #2  , 0 ,4.6
     491     491     496     496
Culvert Bottom n=0.024
BC Design=,, 0 ,, 0 ,,,,,,
BC Use User HTab Curves=0
BC User HTab FreeFlow(D)= 0

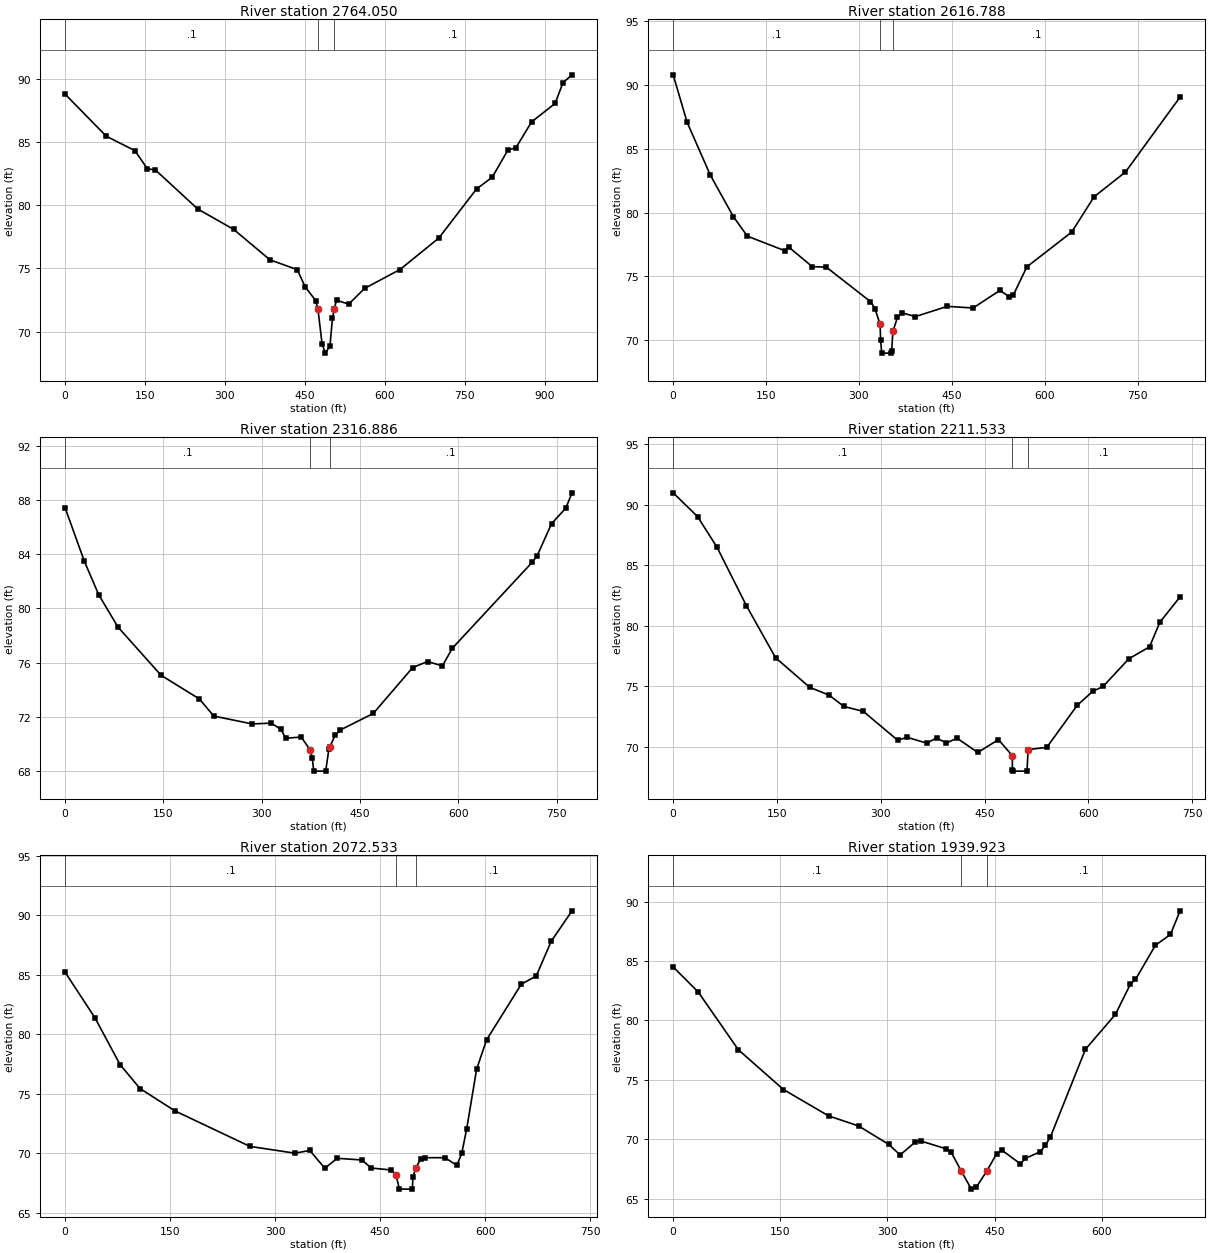
Type RM Length L Ch R = 1 ,2764.050,153.11,147.27,74.04
BEGIN DESCRIPTION:
Upstream Limit of Detailed Study, Section C
END DESCRIPTION:
XS GIS Cut Line= 6
1627209.19556993718399.6315898451627288.37876165718228.284355193
1627407.85109597717922.0424250511627418.92694785717879.123498946
1627424.44366688717812.9228709641627325.06857744717505.616257742
#Sta/Elev= 30
       0   88.77   77.11   85.45  131.09    84.3  154.23   82.88  169.65   82.77
  248.93   79.69  316.61   78.07  384.55   75.67  435.85   74.89  450.51   73.54
  470.35   72.45   474.7   71.75  482.44      69  488.63   68.29  497.23   68.87
  501.89   71.06  505.06   71.76  509.48   72.48  532.37   72.16  562.23   73.41
  628.67    74.9  701.57   77.39  772.33   81.27  801.85    82.2  831.37   84.36
  846.13   84.52  875.64   86.57  919.92   88.04  934.68   89.68  951.68    90.3
#Mann= 3 , 0 , 0
       0      .1       0   474.7     .04       0  505.06      .1       0
Bank Sta=474.7,505.06
XS Rating Curve= 0 ,0
Exp/Cntr=0.5,0.3

Type RM Length L Ch R = 1 ,2616.788,163.75,299.9,155.85
XS GIS Cut Line= 5
 1627632.8156549718336.5990652591627535.00276002718079.632985502
1627496.03408816717938.7716503291627483.08344653717884.378955856
1627396.31414609717554.137590423
#Sta/Elev= 30
       0   90.77   22.47   87.06   59.92   82.93   97.37   79.66  119.84   78.15
  179.76   77.02  187.25   77.27   224.7   75.76  247.17   75.73  318.53   73.03
  325.79   72.49   334.1   71.24  334.98      70  336.76      69  351.99      69
  352.77    69.2  354.81   70.71  362.11   71.79  369.37   72.15  391.16   71.86
  442.69   72.66  484.26   72.53  527.68   73.91  542.16   73.42  549.39   73.56
  571.11   75.75  643.48   78.47  679.67   81.23  730.33   83.17  818.47   89.03
#Mann= 3 , 0 , 0
       0      .1       0   334.1     .04       0  354.81      .1       0
Bank Sta=334.1,354.81
XS Rating Curve= 0 ,0
Exp/Cntr=0.3,0.1

Type RM Length L Ch R = 1 ,2316.886,132.59,105.35,85.37
XS GIS Cut Line= 6
1627754.42267519718275.1255558281627649.39411169717930.426874653
1627646.07842033717879.0336587131627593.83471783717798.541939586
1627557.57292084717709.1825111511627512.24567516717546.004423946
#Sta/Elev= 30
       0   87.41   29.27   83.48   51.22   81.01    80.5   78.63  146.35   75.07
   204.9   73.32  226.85   72.06  285.39   71.48  314.66   71.54   329.3   71.08
  336.62   70.43  360.34   70.51  374.37   69.53  377.07      69  379.41      68
  397.64      68  402.43    69.6  403.97   69.77  411.84   70.63  420.19   71.04
  470.26   72.25  530.47   75.64  553.13   76.08  575.79   75.76   590.9   77.06
  713.22   83.42  720.48   83.89  742.28   86.24  764.07   87.39   773.6   88.52
#Mann= 3 , 0 , 0
       0      .1       0  374.37     .04       0  403.97      .1       0
Bank Sta=374.37,403.97
XS Rating Curve= 0 ,0
Exp/Cntr=0.3,0.1

Type RM Length L Ch R = 1 ,2211.533,69.54,139,160.85
XS GIS Cut Line= 6
1627814.06645198 718317.016457261627767.55460925717917.014599517
1627747.08939739717863.0608603661627717.32181726  717831.4328067
1627685.69376366717792.3628585041627624.29812998717624.920220107
#Sta/Elev= 30
       0   90.98   35.24   89.02   63.42   86.48  105.71   81.67  147.99   77.36
  197.32   74.92  225.51   74.27  246.65   73.34  274.84   72.93  324.17   70.56
  338.26   70.79  366.45   70.31  380.55   70.74  394.64   70.32  410.18   70.72
  440.13   69.54  470.01    70.6  490.01   69.28  490.25   68.06  490.38      68
  511.32      68  512.84   69.78  539.86   69.96  583.92   73.44  606.29   74.59
   621.2   74.99  658.48   77.28  688.31   78.26  703.22   80.29  732.45   82.39
#Mann= 3 , 0 , 0
       0      .1       0  490.01     .04       0  512.84      .1       0
Bank Sta=490.01,512.84
XS Rating Curve= 0 ,0
Exp/Cntr=0.3,0.1

Type RM Length L Ch R = 1 ,2072.533,130.89,132.61,105.02
XS GIS Cut Line= 4
 1627881.4925063  718215.57633091627806.88945088717834.271825463
1627813.52083363717663.5137208551627786.99530278717501.044844612
#Sta/Elev= 30
       0   85.22    42.8   81.37   78.46   77.46  106.99   75.45  156.92   73.57
  263.91   70.59  328.11   70.02   349.5   70.25   370.9   68.75  388.53   69.59
  423.56   69.45  437.57   68.77  465.59   68.61   472.6   68.18  477.49      67
  495.91      67  496.86      68  500.62   68.75  507.62   69.51  514.63   69.64
  542.65   69.64  559.42   68.99  566.51      70  573.61   72.08  587.79   77.08
  601.98   79.54  651.63   84.22   672.9    84.9  694.18   87.81  724.04   90.38
#Mann= 3 , 0 , 0
       0      .1       0   472.6     .04       0  500.62      .1       0
Bank Sta=472.6,500.62
XS Rating Curve= 0 ,0
Exp/Cntr=0.3,0.1

Type RM Length L Ch R = 1 ,1939.923,90.25,119.12,119.43
XS GIS Cut Line= 4
1627967.70048144 718197.340028481627946.14848766717887.322887078
1627916.30726551717721.5383194981627911.33372851717491.097770557
#Sta/Elev= 30
       0    84.5   35.08   82.39   91.22   77.53  154.37   74.18  217.52   71.96
  259.63   71.11  301.73   69.56  317.88   68.67  339.22   69.77  346.33   69.85
  381.89   69.19     389   68.92  403.23   67.33  417.45   65.79  424.57   65.97
  438.79   67.28  453.02   68.79  460.13   69.07  486.22   67.92  493.22   68.38
  514.22   68.95  521.22    69.5  528.23   70.19  577.24   77.57  619.25   80.51
  640.25   83.07  647.25   83.45  675.26   86.33  696.27   87.24  709.71   89.23
#Mann= 3 , 0 , 0
       0      .1       0  403.23     .04       0  438.79      .1       0
Bank Sta=403.23,438.79
XS Rating Curve= 0 ,0
Exp/Cntr=0.3,0.1

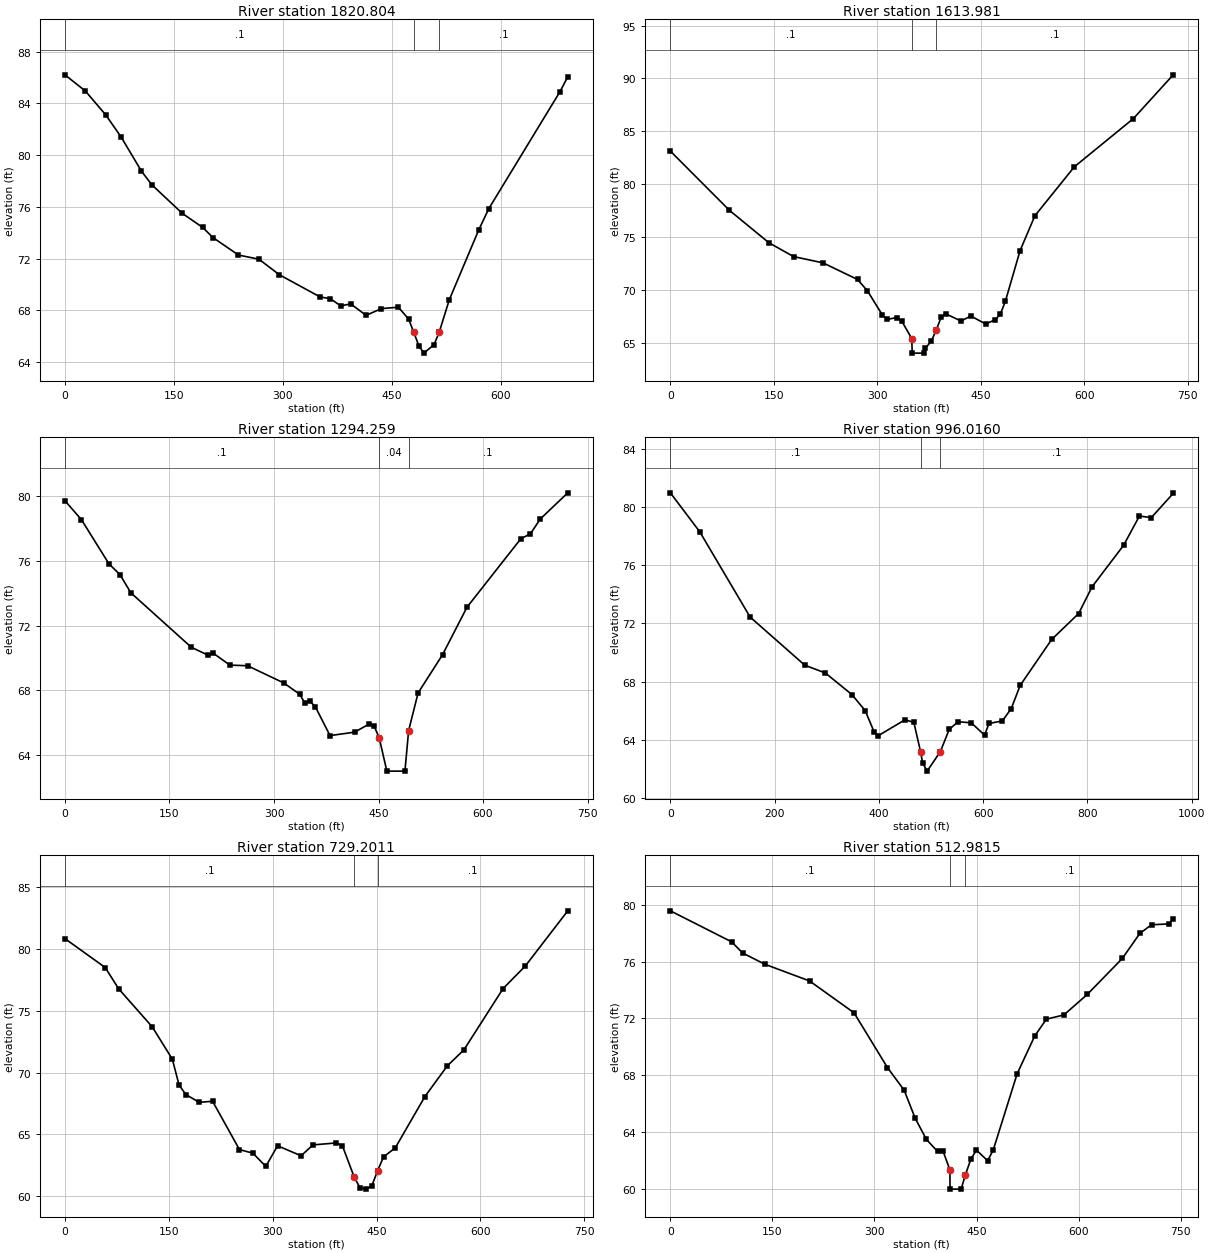
Type RM Length L Ch R = 1 ,1820.804,162.14,206.82,181.94
BEGIN DESCRIPTION:
Section B
END DESCRIPTION:
XS GIS Cut Line= 4
1627988.21411519718230.4400463251628029.14453702717780.205398574
1628036.58643346717690.9026584771628036.58643346717540.204284668
#Sta/Elev= 30
       0    86.2   28.12   84.95   56.23    83.1   77.32    81.4  105.43   78.75
  119.49   77.71  161.66   75.49  189.78    74.4  203.84   73.62  238.98   72.27
   267.1   71.95  295.21   70.75  351.44   69.03   365.5    68.9  379.56   68.35
  393.62   68.49   414.7   67.61  435.79   68.13  459.12   68.24  473.16   67.33
  480.19   66.33  487.21   65.27  494.24   64.69  508.29   65.35  515.31    66.3
  529.36   68.83   569.7    74.2   583.7   75.86   681.7    84.9   692.4   86.05
#Mann= 3 , 0 , 0
       0      .1       0  480.19     .04       0  515.31      .1       0
Bank Sta=480.19,515.31
XS Rating Curve= 0 ,0
Exp/Cntr=0.3,0.1

Type RM Length L Ch R = 1 ,1613.981,276.81,319.72,271.64
XS GIS Cut Line= 2
1628113.59090094718210.6027938721628256.16562909717496.071307585
#Sta/Elev= 30
       0   83.12   85.66   77.51  142.76   74.45  178.45   73.14  221.28   72.54
  271.24   70.97  285.52    69.9  306.93   67.64  314.07   67.19  328.35   67.37
  335.49   67.01  349.76   65.38  350.49      64  367.99      64   369.6   64.46
  378.31   65.16  385.45   66.21  392.59   67.44  399.73    67.7  421.14   67.04
  435.42   67.51  456.83   66.76  471.11   67.17  478.25   67.71  485.38    68.9
   506.8   73.71  528.21      77  585.32   81.63  670.97    86.2  728.62   90.34
#Mann= 3 , 0 , 0
       0      .1       0  349.76     .04       0  385.45      .1       0
Bank Sta=349.76,385.45
XS Rating Curve= 0 ,0
Exp/Cntr=0.3,0.1

Type RM Length L Ch R = 1 ,1294.259,204.67,298.24,294.66
XS GIS Cut Line= 5
1628292.66858245718283.5832736491628413.59937622718051.024054304
1628447.08790354717959.8608405741628463.83216815717820.325308576
1628450.80885269717598.928932935
#Sta/Elev= 30
       0   79.73   23.67   78.56   63.12   75.83    78.9   75.16   94.68   74.03
  181.47   70.66  205.14   70.18  213.03   70.29   236.7   69.56  262.12   69.52
  314.32   68.45   336.7   67.76  344.15   67.23  351.61   67.32  359.24   66.99
  380.39    65.2  415.64   65.41  436.79   65.92  443.84   65.77  450.89   65.07
  461.96      63  487.89      63   493.2   65.51  506.79   67.84  541.85    70.2
  576.91   73.14  654.04   77.37  668.07   77.69  682.09    78.6  721.56   80.22
#Mann= 3 , 0 , 0
       0      .1       0  450.89     .04       0   493.2      .1       0
Bank Sta=450.89,493.2
XS Rating Curve= 0 ,0
Exp/Cntr=0.3,0.1

Type RM Length L Ch R = 1 ,996.0160,262.45,266.82,264.48
XS GIS Cut Line= 5
1628349.14602283718347.6498947291628496.14243127718089.081983566
1628790.27032857717887.8365802761628983.77552418717748.512838379
1629050.54463005717720.670238495
#Sta/Elev= 30
       0   80.96   56.36   78.29  152.99   72.44  257.67   69.14  297.43    68.6
  348.32   67.12  373.77   66.02  390.73   64.57  399.21   64.31   450.1   65.39
  467.06   65.22  480.09   63.18  484.03   62.42  492.51   61.87  517.96   63.21
  534.92   64.73  551.88   65.26  577.33   65.18  602.77   64.34  611.25   65.14
   636.7   65.31  653.82   66.15  671.07   67.75  731.45    70.9   783.2   72.68
  809.08   74.52  869.46   77.36  899.84   79.37   922.6   79.26   964.6   80.92
#Mann= 3 , 0 , 0
       0      .1       0  480.09     .04       0  517.96      .1       0
Bank Sta=480.09,517.96
XS Rating Curve= 0 ,0
Exp/Cntr=0.3,0.1

Type RM Length L Ch R = 1 ,729.2011,204.1,216.22,211.57
XS GIS Cut Line= 4
1628507.91607258718468.9673962151628702.70873427718265.643667653
1628898.92324039718130.5684647111629078.07561657718028.195679143
#Sta/Elev= 30
       0   80.84   58.16    78.5   77.55   76.78  126.02    73.7   155.1   71.08
   164.8   68.99  174.49   68.22  193.88   67.59  213.27   67.67  252.04   63.76
  271.43   63.47  290.07    62.4  307.07   64.07  341.06   63.26  358.06   64.14
  392.05    64.3  400.55   64.09  417.55   61.56  426.05   60.67  434.55   60.56
  443.04   60.81  451.54   62.05  460.04   63.17  477.04    63.9  519.79   68.05
  552.04   70.53  576.22   71.84  632.66   76.79  664.91   78.63  726.13   83.09
#Mann= 3 , 0 , 0
       0      .1       0  417.55     .04       0  451.54      .1       0
Bank Sta=417.55,451.54
XS Rating Curve= 0 ,0
Exp/Cntr=0.3,0.1

Type RM Length L Ch R = 1 ,512.9815,115.37,123.08,115.97
BEGIN DESCRIPTION:
Downstream limit of detailed study, Section A
END DESCRIPTION:
XS GIS Cut Line= 3
 1628535.2682261718596.3886878491628964.04640909718337.109484434
1629101.86420392 718143.14506413
#Sta/Elev= 30
       0   79.57   89.98   77.39  106.34    76.6  139.06   75.81  204.51   74.64
  269.95    72.4  319.03   68.55  343.57   66.96  359.93   64.97  376.29    63.5
  392.65   62.65  400.83   62.66  410.82   61.36  411.07      60  427.34      60
  433.56      61  441.74   62.12  449.92   62.74  466.28      62  474.46   62.74
  509.66   68.11  535.42   70.76   552.6   71.95  578.36   72.25  612.71   73.69
  664.23   76.22  689.99   77.98  707.17   78.59  732.93   78.65  739.02   79.02
#Mann= 3 , 0 , 0
       0      .1       0  410.82     .04       0  433.56      .1       0
Bank Sta=410.82,433.56
XS Rating Curve= 0 ,0
Exp/Cntr=0.3,0.1

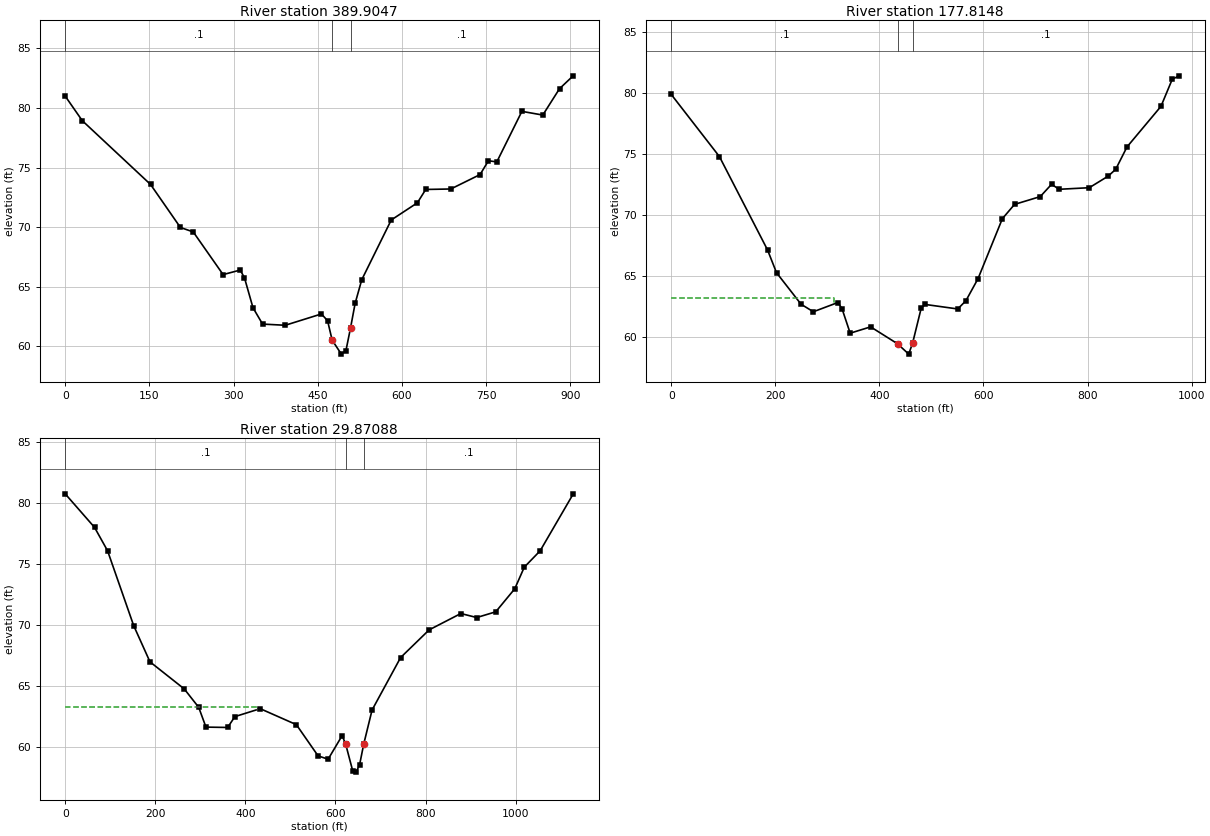
Type RM Length L Ch R = 1 ,389.9047,199.73,212.09,116.26
XS GIS Cut Line= 6
1628532.89084791718672.1091975421628856.61328098718534.434139133
1628957.07886478718476.7594527011629009.17212841718445.131399035
1629031.49781393718387.4567126041629139.40529223718091.641385928
#Sta/Elev= 30
       0      81   30.43   78.94  152.13   73.59  205.38   69.98   228.2   69.61
  281.45   66.03  311.88   66.41  319.48   65.77   334.7   63.25  351.78   61.88
  392.14   61.78  456.71   62.73  467.63   62.16  475.81   60.53  492.19   59.36
  500.38   59.66  508.57   61.56  516.76   63.62  528.57    65.6  581.11   70.61
  627.67   72.05  642.57   73.17  687.28   73.21  739.44   74.42  754.34   75.58
  769.24   75.48  813.95   79.72   851.2   79.41  881.01   81.62   905.3    82.7
#Mann= 3 , 0 , 0
       0      .1       0  475.81     .04       0  508.57      .1       0
Bank Sta=475.81,508.57
XS Rating Curve= 0 ,0
Exp/Cntr=0.3,0.1

Type RM Length L Ch R = 1 ,177.8148,129.35,147.94,131.88
XS GIS Cut Line= 6
1628614.26029503718799.1380088181628813.20177616718762.665403962
1629013.80110292718659.8789720541629025.40602265718608.485756114
1629119.90322617 718416.175657691629192.84843595718144.288966864
#Sta/Elev= 30
       0    79.9   92.52    74.8  185.03   67.13  202.26   65.26  249.45   62.67
  273.05   62.05  320.24   62.81   328.1   62.31  343.83   60.29  383.16   60.81
  434.83   59.42  456.36   58.57  463.95    59.5  480.34   62.35  488.14   62.65
  550.54   62.28  566.14   62.95  589.54   64.77  636.33    69.7  659.73   70.87
  709.11   71.51  730.85   72.52  745.35   72.11  803.33   72.24  839.57   73.19
  854.06   73.75  875.81   75.59  941.03   78.92  962.78   81.15  976.12   81.43
#Mann= 3 , 0 , 0
       0      .1       0  434.83     .04       0  463.95      .1       0
#XS Ineff= 2 , 0
          312.56   63.22
Permanent Ineff=
       F       F
Bank Sta=434.83,463.95
XS Rating Curve= 0 ,0
Exp/Cntr=0.3,0.1

Type RM Length L Ch R = 1 ,29.87088,29.27,29.87,24.76
XS GIS Cut Line= 5
1628604.31651376718907.4549136311628836.59014738718846.256860092
1629135.99143504718677.8680157811629172.24199788718602.681663275
1629221.70821463718144.858254492
#Sta/Elev= 30
       0   80.77   65.15   78.02   94.11    76.1  152.02   69.97  188.21      67
  264.29   64.78  296.42   63.27  312.48   61.65  360.67   61.62  376.73   62.51
  432.95   63.16  513.26   61.85  561.45   59.29  583.71   59.02  614.79   60.95
  622.56   60.27   638.1   58.09  645.87   57.96  653.65   58.58  662.83   60.27
  681.26   63.05  744.62   67.35  807.99   69.62   878.4   70.96   913.6   70.63
  955.84    71.1  998.09   72.99 1019.21   74.76 1054.41    76.1 1127.66   80.75
#Mann= 3 , 0 , 0
       0      .1       0  622.56     .04       0  662.83      .1       0
#XS Ineff= 2 , 0
          425.92   63.28
Permanent Ineff=
       F       F
Bank Sta=622.56,662.83
XS Rating Curve= 0 ,0
Exp/Cntr=0.3,0.1

Chan Stop Cuts=-1
Use User Specified Reach Order=0

--- WestBranchLaurelRun.g02 (geometry) ---

Geom Title=lomr
Program Version=4.00

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
River Reach=WB Laurel Run   ,Herron
Reach XY= 30
     1627119.611      717750.543     1627256.399      717699.392
     1627371.712      717816.868     1627362.343      717928.577
     1627492.791      718018.666     1627611.708      718004.252
     1627603.059      717963.171     1627547.565      717940.829
     1627554.051      717904.794     1627690.265      717886.776
     1627801.254      717728.941     1627869.721      717790.201
     1627956.445      717783.361     1628027.556      717724.617
     1628096.744      717759.211     1628105.127      717829.211
     1628257.461      717884.614     1628289.173      717828.399
     1628334.577       717829.84     1628395.117      717876.686
     1628465.746      717844.975     1628522.682      717886.056
     1628649.526      717887.497     1628645.202      717950.199
     1628851.324      718204.608     1628879.432      718366.767
     1628954.386      718411.451     1629017.087      718527.485
     1628973.194      718627.252     1629061.794      718644.296

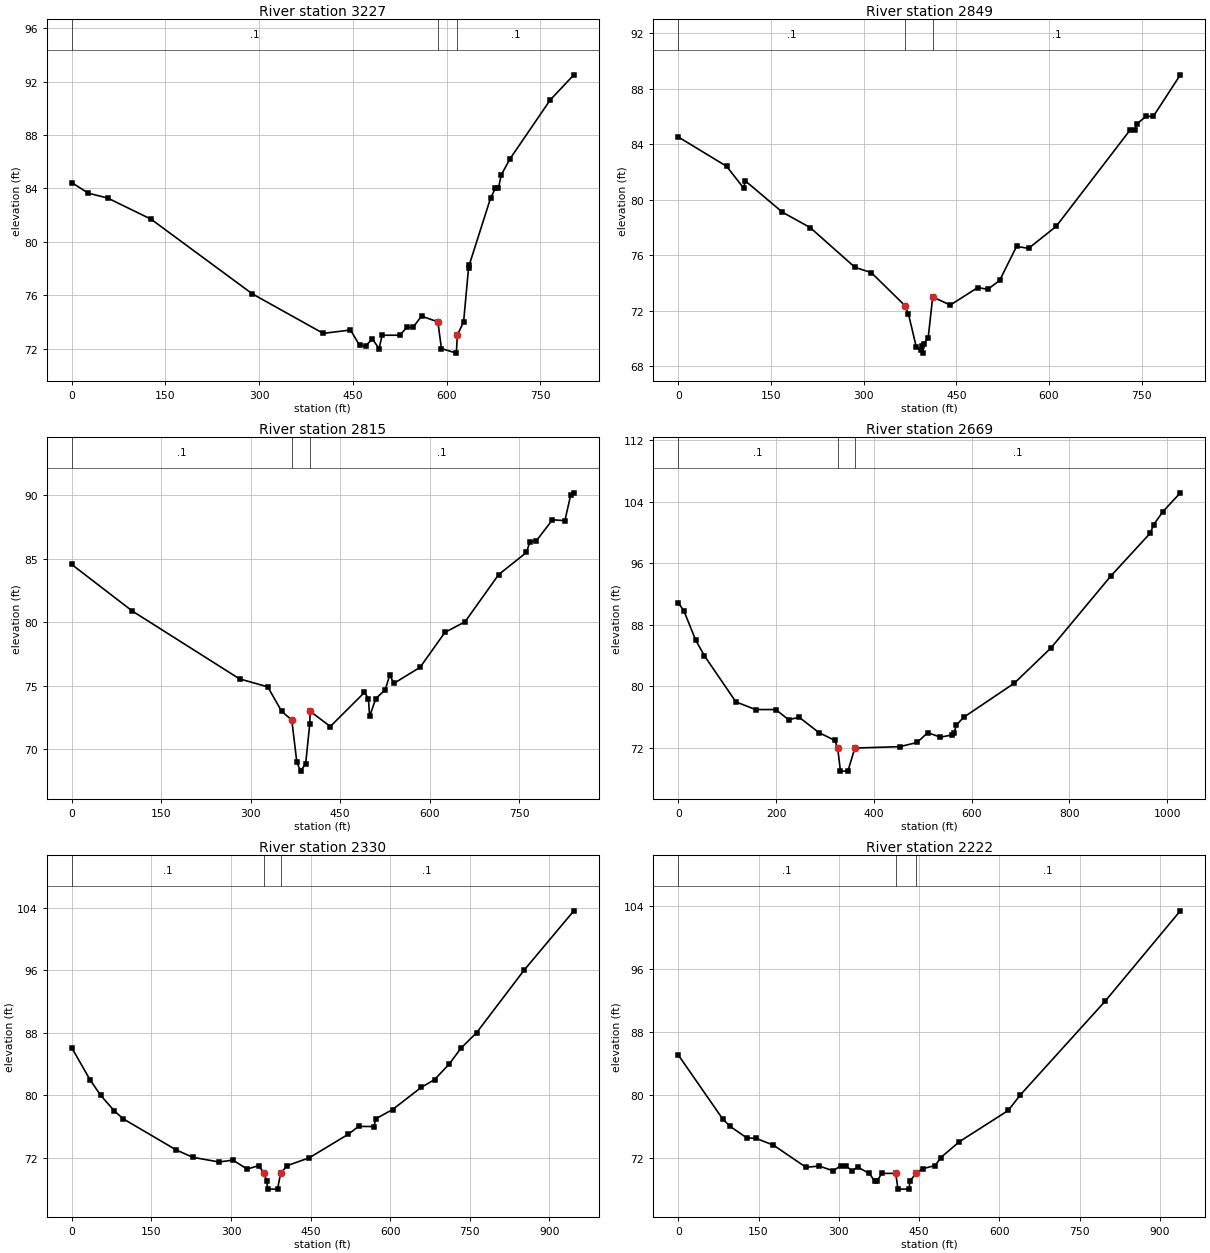
Type RM Length L Ch R = 1 ,3227    ,275.95,377.77,257.05
XS GIS Cut Line= 6
     1627238.687      718300.501     1627192.277       718182.98
     1627250.897       717939.09     1627188.309      717732.002
     1627173.711      717717.747      1627111.35      717538.919
#Sta/Elev= 30
       0   84.43   26.34   83.64   57.65   83.27  126.91   81.69  289.06    76.1
  402.59   73.14  446.23   73.39  460.81   72.25  470.38    72.2  481.27   72.72
  492.03      72  496.95      73  525.34      73  536.17   73.58  546.31   73.59
  560.06   74.43  586.18      74  591.89      72   615.8   71.66   617.3      73
  627.37      74  635.22      78   636.6   78.29   670.7   83.29  678.34      84
  683.07      84  687.61      85  701.26   86.18  765.92   90.61  803.88    92.5
#Mann= 3 , 0 , 0
       0      .1       0  586.18     .04       0   617.3      .1       0
#XS Ineff= 2 , 0
       0  560.06   74.43               0
Permanent Ineff=
       F       F
Bank Sta=586.18,617.3
XS Rating Curve= 0 ,0
Exp/Cntr=0.3,0.1

Type RM Length L Ch R = 1 ,2849    ,34.8,34.1,68.17
XS GIS Cut Line= 6
     1627245.922      718299.503      1627242.99      718269.949
     1627259.068      718233.825     1627272.784      718153.466
     1627408.722      717849.037     1627297.488      717540.755
#Sta/Elev= 30
       0   84.52   78.19   82.41  105.62   80.85  108.81   81.35  168.63    79.1
  213.41      78  286.15   75.13   312.3   74.76  367.11   72.37   372.6   71.77
  385.39   69.37  392.39   69.16     394   69.47  395.41   68.96   397.4   69.65
  404.43   70.04  411.78      73  440.27   72.42  484.77   73.68   500.9   73.55
  520.09   74.19  547.51   76.64  566.96    76.5  611.53   78.08  730.95      85
  738.97      85   742.4   85.47  757.09      86  768.82      86   812.5   88.99
#Mann= 3 , 0 , 0
       0      .1       0  367.11     .04       0  411.78      .1       0
#XS Ineff= 2 , 0
       0                  411.78       0      73
Permanent Ineff=
       F       F
Bank Sta=367.11,411.78
XS Rating Curve= 0 ,0
Exp/Cntr=0.3,0.1

Type RM Length L Ch R = 1 ,2815    ,202.95,146.69,242.29
XS GIS Cut Line= 6
     1627248.667      718298.754     1627246.172      718270.809
     1627269.127      718204.937     1627304.462      718158.377
     1627439.621      717832.216     1627333.968      717517.786
#Sta/Elev= 30
       0   84.55  101.44   80.89  281.31   75.55  328.69   74.92  351.88      73
  368.96   72.31  377.44      69  383.63   68.29  392.23   68.87  399.08      72
  399.85      73  433.52    71.8  490.82   74.48  497.48      74  499.49    72.6
  509.89      74  525.65   74.69  533.32   75.87  539.99   75.19  584.13   76.46
  625.86   79.21  659.48   80.04  715.98   83.76  762.53    85.5  768.29   86.34
  779.16   86.42  806.16   88.07  826.96      88  836.61      90  841.99   90.19
#Mann= 3 , 0 , 0
       0      .1       0  368.96     .04       0  399.85      .1       0
#XS Ineff= 2 , 0
       0                  399.85       0      73
Permanent Ineff=
       F       F
Bank Sta=368.96,399.85
XS Rating Curve= 0 ,0
Exp/Cntr=0.3,0.1

Type RM Length L Ch R = 1 ,2669    ,152.84,339.02,154.92
XS GIS Cut Line= 6
     1627631.139      718336.419     1627519.279      718023.518
     1627517.058      718012.334     1627495.184      717945.366
     1627420.221      717489.467     1627427.653      717338.907
#Sta/Elev= 30
       0   90.87   11.39   89.85   35.86      86   53.45      84  117.84      78
  158.09      77  199.39      77   225.8   75.68  247.33      76   287.9      74
  320.07      73  326.09      72  331.76      69  346.99      69  361.27      72
   453.3   72.18  488.47   72.72  510.37      74  536.19   73.41  559.63    73.7
  564.22      74  569.06      75  583.93      76  687.44   80.43  762.39   85.01
  884.81   94.35  965.55   99.93  972.07     101  991.18  102.71 1026.91  105.16
#Mann= 3 , 0 , 0
       0      .1       0  326.09     .04       0  361.27      .1       0
Bank Sta=326.09,361.27
XS Rating Curve= 0 ,0
Exp/Cntr=0.3,0.1

Type RM Length L Ch R = 1 ,2330    ,167.54,107.47,93.57
XS GIS Cut Line= 6
     1627775.089      718254.531     1627703.891       718115.25
     1627645.179      717929.082     1627646.345      717883.921
     1627552.526      717714.931     1627530.603      717359.832
#Sta/Elev= 30
       0   86.07   34.22      82   54.35      80   80.22      78   96.65      77
  197.05      73  227.89   72.07  277.49   71.47  303.63   71.71  330.43   70.56
  351.87      71  362.87      70  367.07      69  369.41      68  387.64      68
  393.41      70  405.66      71  447.31      72  520.58      75  540.39   76.02
  569.31      76  572.86      77  604.53   78.18  658.22      81  683.41      82
  711.25      84  732.99      86  762.67      88  852.24      96   945.9  103.58
#Mann= 3 , 0 , 0
       0      .1       0  362.87     .04       0  393.41      .1       0
#XS Ineff= 2 , 0
       0  351.87      71               0
Permanent Ineff=
       F       F
Bank Sta=362.87,393.41
XS Rating Curve= 0 ,0
Exp/Cntr=0.3,0.1

Type RM Length L Ch R = 1 ,2222    ,93.14,147.82,165.74
XS GIS Cut Line= 6
     1627884.588       718208.94     1627774.411      717997.913
     1627764.331      717872.761     1627697.195      717818.761
     1627644.833      717718.707     1627607.257      717357.518
#Sta/Elev= 30
       0   85.07   82.72   76.95    96.5      76  127.71   74.53  145.72   74.44
  177.65    73.6  238.54   70.78  263.54   70.93  289.33   70.33  304.29      71
  312.62      71     324   70.36  335.59   70.78   356.9      70  367.06      69
  370.94      69  380.26      70  406.27      70  410.38      68  431.32      68
  432.51      69  444.08      70  456.63    70.6  480.13      71  490.17      72
  525.28   74.04  616.32      78  639.19      80  796.87   91.86  937.76  103.39
#Mann= 3 , 0 , 0
       0      .1       0  406.27     .04       0  444.08      .1       0
#XS Ineff= 2 , 0
       0  406.27      70               0
Permanent Ineff=
       F       F
Bank Sta=406.27,444.08
XS Rating Curve= 0 ,0
Exp/Cntr=0.3,0.1

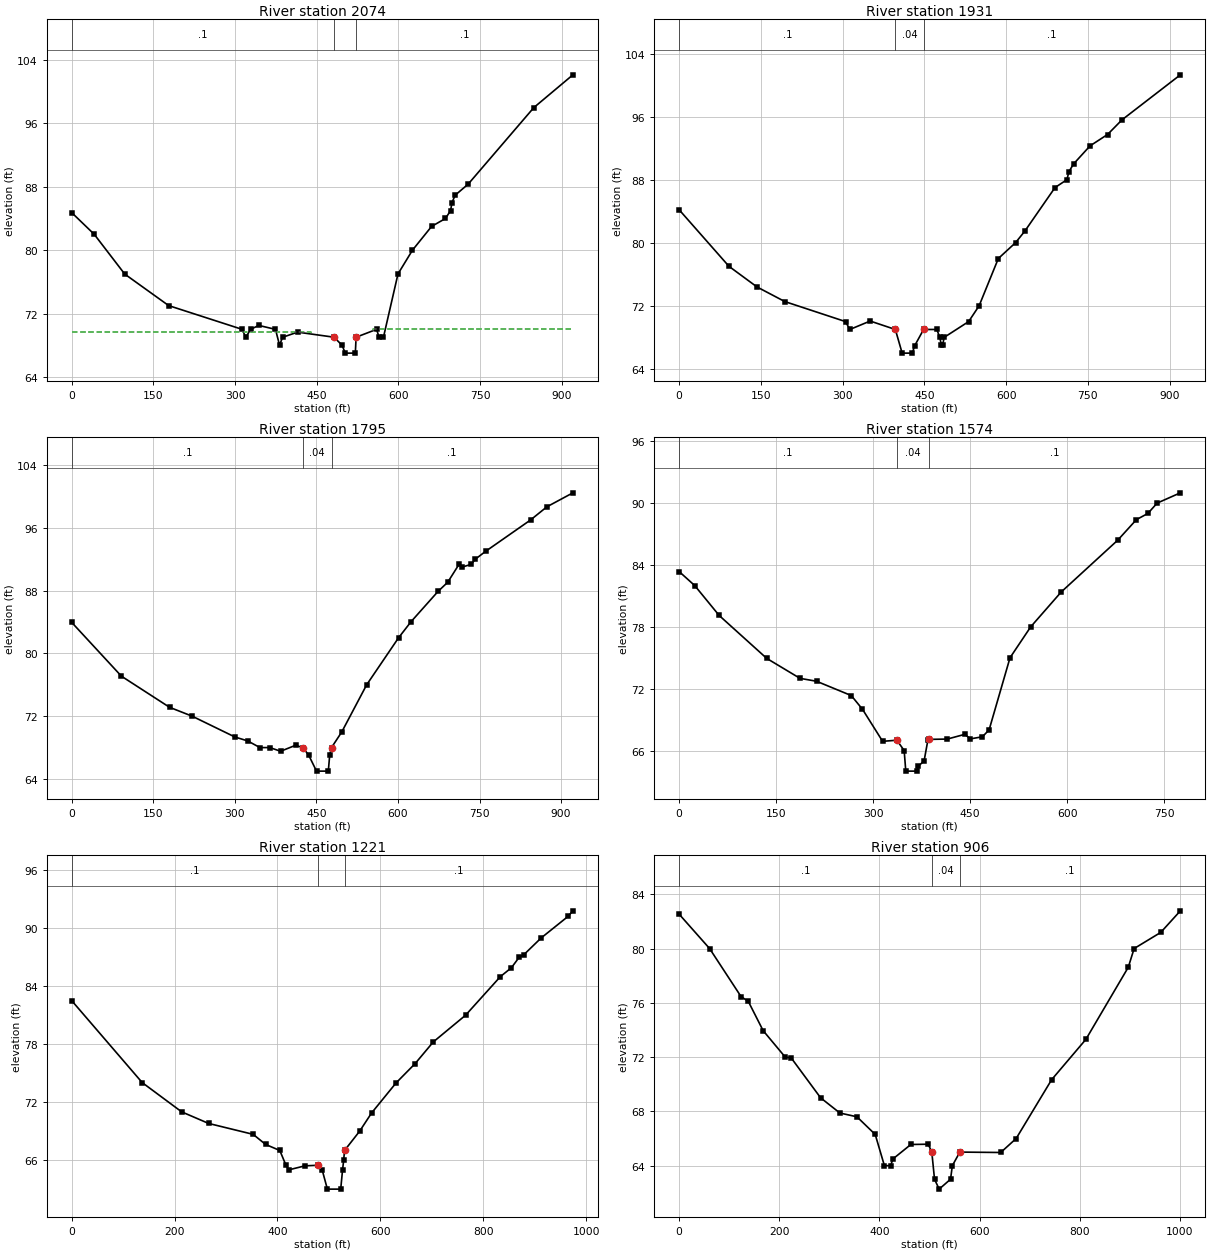
Type RM Length L Ch R = 1 ,2074    ,114.13,143.31,143.85
XS GIS Cut Line= 6
      1627935.79      718198.094     1627863.794      717880.371
     1627799.707      717824.892     1627813.377      717719.874
     1627770.218      717585.841     1627743.089      717338.134
#Sta/Elev= 30
       0   84.74   41.37      82   97.39   76.98  178.11      73  313.14      70
  319.61      69  328.66      70  343.49    70.5  374.26      70  381.71      68
  387.25      69  414.83   69.65  481.89   69.01  496.45      68  502.49      67
  520.91      67  522.34   69.01   559.9      70  564.65      69  572.56      69
  599.26      77  625.85      80     661      83  686.48      84  695.88      85
  698.39      86  704.26   86.94  728.19   88.34  848.73      98  920.55  102.14
#Mann= 3 , 0 , 0
       0      .1       0  481.89     .04       0  522.34      .1       0
#XS Ineff= 2 , 0
       0   439.6   69.63  553.31       0      70
Permanent Ineff=
       F       F
Bank Sta=481.89,522.34
XS Rating Curve= 0 ,0
Exp/Cntr=0.3,0.1

Type RM Length L Ch R = 1 ,1931    ,140.63,136,161.54
XS GIS Cut Line= 6
     1627964.725      718185.586      1627926.47      717975.837
      1627942.16      717890.728     1627899.226      717672.224
      1627933.37      717527.459      1627904.29      717294.243
#Sta/Elev= 30
       0   84.18    91.4   77.01  142.96   74.39  193.92   72.54  305.32      70
  313.22      69  350.54   70.07  396.79      69  409.26      66  427.88      66
  432.28   66.94  448.64      69  472.92      69  478.36      68  481.35      67
  483.55      67   486.4      68  531.29      70  550.51      72  585.79      78
   617.4   80.01  634.39   81.47  689.84      87  711.74      88  715.26      89
  723.95      90  754.17   92.29  786.26   93.73   812.8   95.59  919.91   101.3
#Mann= 3 , 0 , 0
       0      .1       0  396.79     .04       0  448.64      .1       0
#XS Ineff= 2 , 0
       0  350.48   70.06  448.64       0      69
Permanent Ineff=
       F       F
Bank Sta=396.79,448.64
XS Rating Curve= 0 ,0
Exp/Cntr=0.3,0.1

Type RM Length L Ch R = 1 ,1795    ,157.45,220.92,210.09
XS GIS Cut Line= 6
     1628024.275      718188.078     1628039.503      718057.947
     1628033.066      717736.129     1628048.874      717705.526
     1628074.112      717491.739     1628060.269      717273.009
#Sta/Elev= 30
       0   83.95   91.37    77.1  180.03   73.13  221.54      72  300.13   69.35
  323.59   68.85  346.21      68  364.43      68  384.19   67.53   411.6   68.29
  425.31      68  436.08      67  450.23      65  471.93      65  474.41      67
   477.8      68  496.72      70  542.45      76  601.22      82  624.08   84.04
  673.76    87.9  691.56   89.07  713.07   91.43  718.21      91  734.69   91.35
  742.19      92  761.13      93  843.85      97  873.96   98.68  921.79  100.46
#Mann= 3 , 0 , 0
       0      .1       0  425.31     .04       0   477.8      .1       0
#XS Ineff= 2 , 0
       0   411.6   68.29               0
Permanent Ineff=
       F       F
Bank Sta=425.31,477.8
XS Rating Curve= 0 ,0
Exp/Cntr=0.3,0.1

Type RM Length L Ch R = 1 ,1574    ,299.89,353.57,273.87
XS GIS Cut Line= 6
     1628111.224      718208.086     1628182.006      717863.741
      1628184.69      717850.687     1628206.819      717743.028
      1628235.24      717688.771     1628242.419      717449.755
#Sta/Elev= 30
       0   83.36   24.09      82   61.88    79.1  135.37   74.94  186.91      73
  212.44   72.72  266.22   71.33  283.52      70  314.69   66.89  336.66      67
  347.98      66  350.49      64  367.99      64   369.6   64.46  378.84      65
  384.61   66.99  386.23   67.08  414.65   67.11  441.78   67.57   450.4   67.13
  468.88   67.33  479.35      68   511.7      75  543.72      78  590.89   81.38
  678.37   86.41  707.19    88.4  724.95      89  739.18      90  775.16      91
#Mann= 3 , 0 , 0
       0      .1       0  336.66     .04       0  386.23      .1       0
Bank Sta=336.66,386.23
XS Rating Curve= 0 ,0
Exp/Cntr=0.3,0.1

Type RM Length L Ch R = 1 ,1221    ,224.33,314.52,370.64
XS GIS Cut Line= 6
     1628228.227      718283.896     1628419.782      718040.501
     1628459.863      717856.887      1628462.88      717832.605
      1628428.85      717634.933      1628304.72      717416.177
#Sta/Elev= 30
       0   82.51  136.98   74.03  213.71      71   266.1    69.8  352.72   68.67
  376.78   67.63  404.52      67   416.4   65.48  422.29      65  453.26   65.41
   478.5   65.47  486.79      65  496.96      63  522.89      63  526.49      65
  528.67      66  530.31      67  559.71      69  583.01   70.89  630.58      74
  667.63      76  702.88   78.24  765.53      81  833.27      85  854.73   85.92
  869.78      87  878.34   87.24  912.49      89  964.95   91.24  974.26   91.81
#Mann= 3 , 0 , 0
       0      .1       0   478.5     .04       0  530.31      .1       0
Bank Sta=478.5,530.31
XS Rating Curve= 0 ,0
Exp/Cntr=0.3,0.1

Type RM Length L Ch R = 1 ,906     ,232.49,266.88,286.65
XS GIS Cut Line= 6
     1628334.989      718378.391     1628423.516       718284.56
     1628479.187       718168.58     1628669.139      717980.736
     1628853.795      717829.067     1629089.134       717803.92
#Sta/Elev= 30
       0   82.53   60.76      80  123.74   76.45  137.99   76.11   167.7   73.95
   211.8      72  223.73   71.94  282.49      69  320.94   67.88  355.04    67.6
  391.52    66.3  409.87      64   422.4      64  426.74   64.49  462.72   65.56
   497.4   65.58  504.53      65  509.98      63  519.25   62.27  541.94      63
  545.59      64  560.55      65  642.18   64.97  673.01      66  743.95   70.34
  812.32   73.31  896.92   78.62   908.6      80  961.81   81.19 1000.94   82.78
#Mann= 3 , 0 , 0
       0      .1       0  504.53     .04       0  560.55      .1       0
#XS Ineff= 2 , 0
       0   497.4   65.58               0
Permanent Ineff=
       F       F
Bank Sta=504.53,560.55
XS Rating Curve= 0 ,0
Exp/Cntr=0.3,0.1

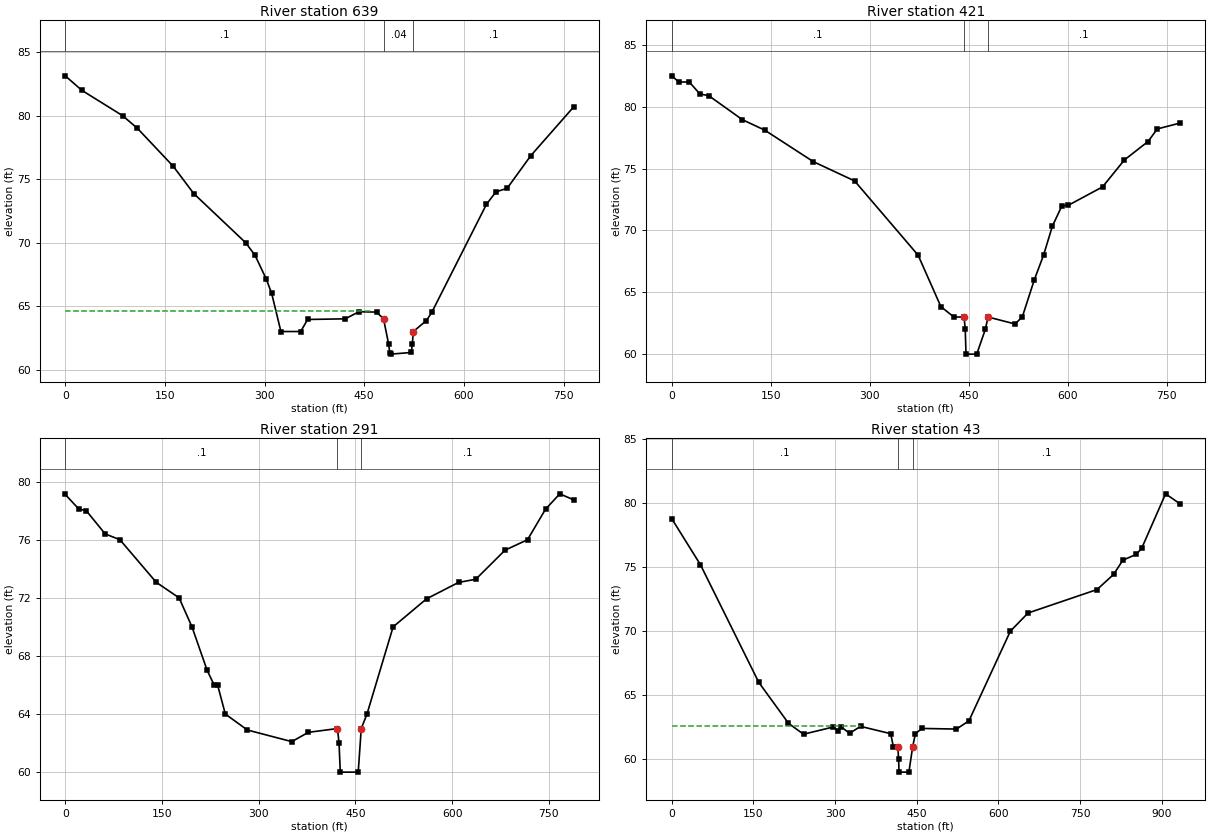
Type RM Length L Ch R = 1 ,639     ,226.49,218.59,179.93
XS GIS Cut Line= 6
      1628430.59      718456.848     1628602.505      718259.758
     1628820.589      718191.355     1628838.835      718168.391
     1628975.867      718127.381     1629058.265      718066.345
#Sta/Elev= 30
       0   83.14   24.98      82   86.43      80  108.75      79  162.83      76
  193.38   73.87  271.69   69.99   285.7      69  302.61   67.13  310.72      66
  324.63      63   354.3      63  364.87   63.95   421.3      64  442.31   64.56
  468.55   64.53  479.03      64  486.79      62  488.45    61.3  490.09   61.22
  520.83   61.35  522.39      62  523.86      63  543.53   63.86  551.56    64.5
  633.96   73.02  648.16      74  665.08   74.28  700.82   76.86     765   80.68
#Mann= 3 , 0 , 0
       0      .1       0  479.03     .04       0  523.86      .1       0
#XS Ineff= 2 , 0
       0  461.21   64.63               0
Permanent Ineff=
       F       F
Bank Sta=479.03,523.86
XS Rating Curve= 0 ,0
Exp/Cntr=0.3,0.1

Type RM Length L Ch R = 1 ,421     ,134.41,129.23,139.8
XS GIS Cut Line= 6
     1628479.503      718560.428     1628571.574      718502.164
     1628887.193      718388.402     1628925.473      718325.215
     1628981.579       718309.39     1629082.282      718150.423
#Sta/Elev= 30
       0    82.5   10.99      82   26.67      82   42.83   81.03   56.08    80.9
   107.3   78.95  140.98   78.11  214.72   75.56   277.3      74  373.47      68
  407.99   63.84  427.68      63  443.14      63   444.9      62  446.07      60
  462.34      60  475.34      62  479.48      63  520.26   62.44  531.35      63
  549.52      66  563.59      68  576.99   70.35  591.54      72  600.67   72.02
  652.99   73.52  686.12    75.7  721.94   77.19  736.09   78.21  770.38   78.68
#Mann= 3 , 0 , 0
       0      .1       0  443.14     .04       0  479.48      .1       0
#XS Ineff= 2 , 0
       0                  479.48       0      63
Permanent Ineff=
       F       F
Bank Sta=443.14,479.48
XS Rating Curve= 0 ,0
Exp/Cntr=0.3,0.1

Type RM Length L Ch R = 1 ,291     ,188.05,248.37,84.43
XS GIS Cut Line= 6
     1628596.516      718674.275     1628833.099      718577.324
     1628965.513      718467.312     1629016.241      718437.924
     1629044.635      718399.779     1629092.588      718151.224
#Sta/Elev= 30
       0   79.12   20.94   78.12   32.64      78   61.96    76.4   84.83      76
  141.11   73.07  176.53      72  196.55      70  220.11      67  230.94      66
  236.27      66  248.23      64  282.43    62.9  351.27    62.1  377.06   62.74
  422.09      63  424.56      62  426.49      60  454.29      60  458.99      63
  467.89      64  508.38      70  560.22   71.93  609.82   73.06   636.6   73.28
  681.89   75.28  716.79      76  744.68    78.1  766.82   79.16  788.12   78.75
#Mann= 3 , 0 , 0
       0      .1       0  422.09     .04       0  458.99      .1       0
#XS Ineff= 2 , 0
       0  422.09      63               0
Permanent Ineff=
       F       F
Bank Sta=422.09,458.99
XS Rating Curve= 0 ,0
Exp/Cntr=0.3,0.1

Type RM Length L Ch R = 1 ,43      ,138.26,42.68,23.78
XS GIS Cut Line= 6
     1628647.782      718773.984     1628789.427      718774.405
     1628949.874      718649.888     1629017.493      718652.241
     1629103.577      718374.204     1629127.953      718148.627
#Sta/Elev= 30
       0   78.79   52.78   75.19  159.85   66.01  214.47   62.81  242.03   61.96
  296.52   62.52  305.52   62.23  310.74   62.55   326.5   62.03  346.85   62.57
  402.14      62  406.91      61  415.18      61  416.58      60  417.44      59
  435.52      59  442.48      61   447.5      62  459.55   62.41  522.83   62.36
  545.68      63  621.76      70  654.32   71.42  780.97   73.25  811.29   74.43
  828.31   75.54  853.12      76  863.08   76.49  906.75   80.72  933.22   79.94
#Mann= 3 , 0 , 0
       0      .1       0  415.18     .04       0  442.48      .1       0
#XS Ineff= 2 , 0
       0  345.72   62.58               0
Permanent Ineff=
       F       F
Bank Sta=415.18,442.48
XS Rating Curve= 0 ,0
Exp/Cntr=0.3,0.1