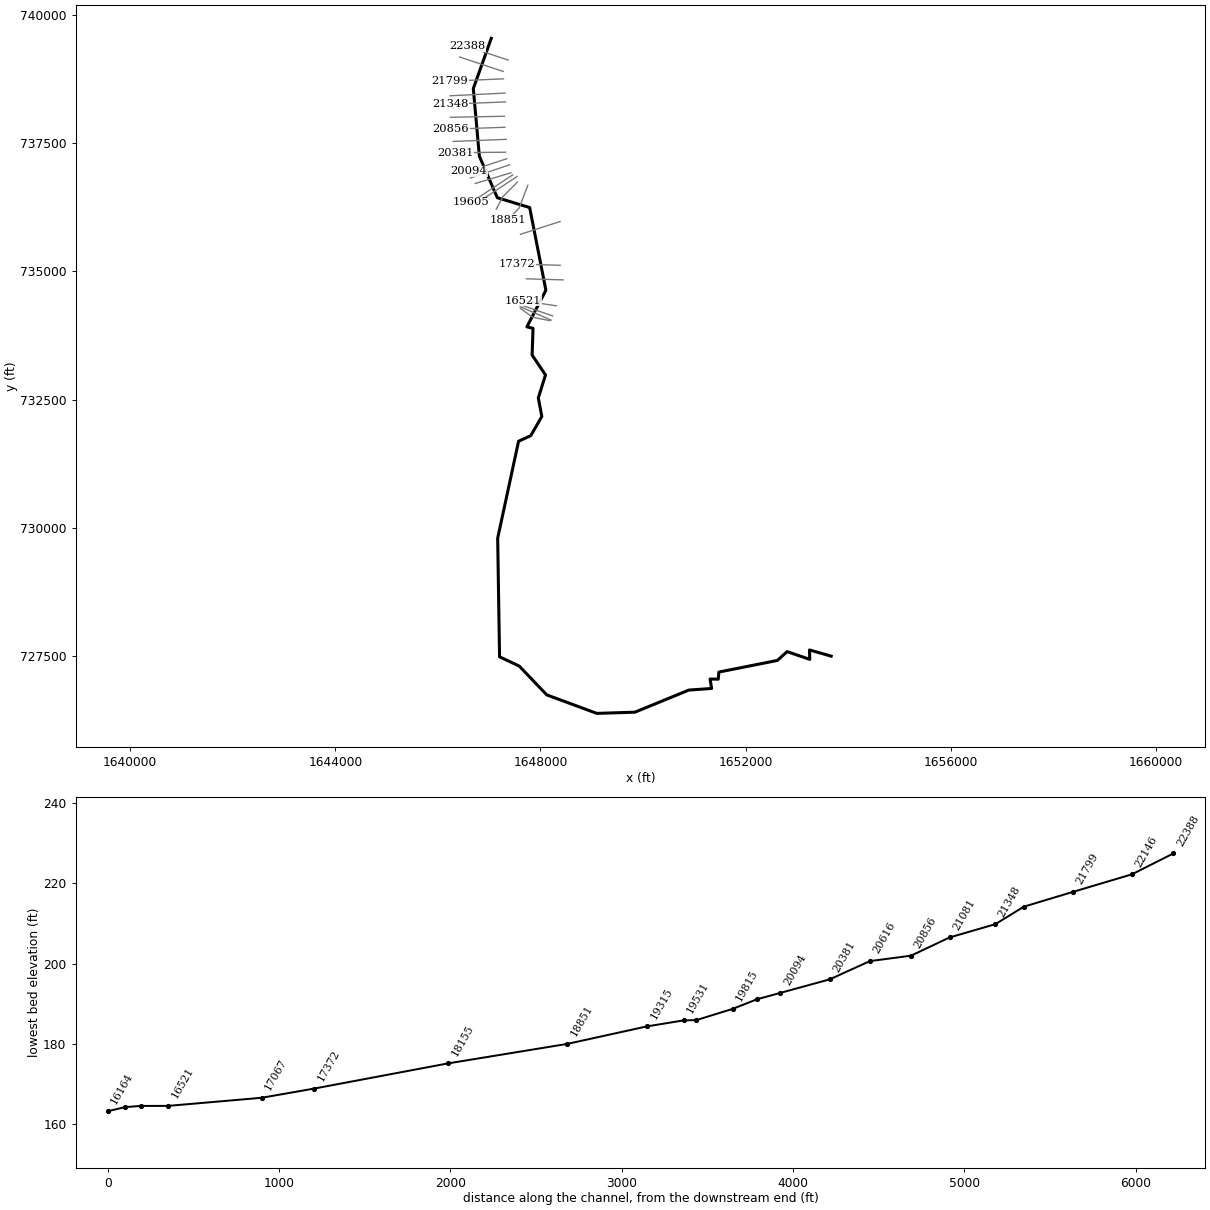
--- WB_Christina.prj (project) ---

Proj Title=WB_Christina
Current Plan=p08
Default Exp/Contr=0.3,0.1
English Units
Geom File=g13
Flow File=f03
Plan File=p08
Y Axis Title=Elevation
X Axis Title(PF)=Main Channel Distance
X Axis Title(XS)=Station
BEGIN DESCRIPTION:
West Branch Christina River, Cecil County, MD. Geo-referenced HEC-RAS model. Vertical datum NAVD1988. Created by Pat Wheeler, USACE, Seattle District. Based on DEM data and existing HEC-2 cross section data.
END DESCRIPTION:
DSS File=dss
DSS Export Rating Curves= 0
DSS Export Rating Curve Sorted= 0
DSS Export Volume Flow Curves= 0
DXF OffsetX= 0
DXF OffsetY= 0
DXF ScaleX= 1
DXF ScaleY= 10

--- WB_Christina.p08 (plan) ---

Plan Title=WB_Christina_FIS_ITR_Submittal
Program Version=4.00
Short Identifier=WB_ITR_Submit
Geom File=g13
Flow File=f03
Subcritical Flow
K Sum by GR= 0
Std Step Tol= 0.01
Critical Tol= 0.01
Num of Std Step Trials= 20
Max Error Tol= 0.3
Flow Tol Ratio= 0.001
Split Flow NTrial= 30
Split Flow Tol= 0.02
Split Flow Ratio= 0.02
Log Output Level= 0
Friction Slope Method= 1
Unsteady Friction Slope Method= 2
Unsteady Bridges Friction Slope Method= 1
Parabolic Critical Depth
Global Vel Dist= 0 , 0 , 0
Global Log Level= 0
CheckData=True
Encroach Param=-1 ,0,0, 2
Encroach River=westbrchristine
Encroach Reach=westbrchristine
Encroach Node=19815
       1     400     435
Encroach Node=19605
       1     438  523.39
Encroach Node=19531
       1  444.78   567.3
Encroach Node=19315
       1  422.03  469.46
Encroach Node=18851
       1     325  354.95
Encroach Node=18155
       1     510  575.44
Encroach Node=17372
       1   430.4     471
Encroach Node=17067
       1  427.36  470.76
Encroach Node=16521
       1  340.11  373.58
Encroach Node=16358
       1     370     432
Encroach Node=16266
       1     410     480
Encroach Node=16164
       1     325     395
Encroach Node=16094
       1  465.08  519.45
Encroach Node=15532
       1  310.76  378.88
Encroach Node=15374
       1  384.01  432.12
Encroach Node=14714
       1  345.02     388
Encroach Node=14427
       1     350  394.28
Encroach Node=14269
       1  279.62  336.02
Encroach Node=13933
       1   433.9  468.71
Encroach Node=13561
       1     229     265
Encroach Node=13077
       1  247.05  323.07
Encroach Node=12601
       1     205     280
Encroach Node=12496
       1     275     330
Encroach Node=12302
       1     303     373
Encroach Node=12261
       1     300     335
Encroach Node=12105
       1     425     476
Encroach Node=11791
       1     425  551.78
Encroach Node=11185
       1     415     670
Encroach Node=10977
       1     600     700
Encroach Node=10867
       1  647.93  696.03
Encroach Node=10684
       1     240     570
Encroach Node=10341
       1     400     670
Encroach Node=10287
       1     405     650
Encroach Node=10064
       1  552.98  605.81
Encroach Node=9942
       1     540     603
Encroach Node=9741
       1     555     608
Encroach Node=9470
       1     525   573.4
Encroach Node=8705
       1     490     550
Encroach Node=8172
       1     548  710.43
Encroach Node=7609
       1     565     650
Encroach Node=7080
       1     415     535
Encroach Node=6604
       1     650     770
Encroach Node=6131
       1     775     900
Encroach Node=5884
       1     685  895.18
Encroach Node=5791
       1     575     685
Encroach Node=5633
       1     790     860
Encroach Node=5324
       1     770     853
Encroach Node=4913
       1     750     840
Encroach Node=4541
       1     650     800
Encroach Node=4317
       1     645     840
Encroach Node=4237
       1     675     840
Encroach Node=4037
       1     600     700
Encroach Node=3399
       1     885     966
Encroach Node=2463
       1     546     645
Encroach Node=1667
       1  811.21  896.21
Encroach Node=1133
       1     412  638.34
Encroach Node=388
       1     500     635
Encroach Node=-25
       1  484.59  628.59
BEGIN DESCRIPTION:
West Branch Christina with ITR comments incorporated
END DESCRIPTION:
Computation Interval=1HOUR
Output Interval=1HOUR
Run HTab= 0
Run UNet= 0
Run PostProcess= 0
Run WQNet= 0
UNET Theta= 1
UNET Theta Warmup= 1
UNET ZTol= 0.02
UNET ZSATol= 0.05
UNET MxIter= 20
UNET MaxInSteps= 0
UNET DtIC= 0
UNET DtMin= 0
UNET MaxCRTS= 20
UNET WFStab= 2
UNET SFStab= 1
UNET WFX= 1
UNET SFX= 1
UNET DSS MLevel= 4
UNET DZMax Abort= 100
UNET Convert EG Bridges= 0
UNET Use Existing IB Tables=-1
UNET Froude Reduction=False
UNET Froude Limit= 1
UNET Froude Power= 10
UNET Time Slicing=0,0, 5
Instantaneous Interval=1HOUR
Write IC File= 0
Echo Input=False
Echo Output=False
Write Detailed= 0
Detailed Automatic Start=False, 10
WQ ULTIMATE=-1
WQ Max Comp Step=1HOUR
WQ Output Interval=15MIN
WQ Output Selected Increments= 0
WQ Output face flow=0
WQ Output face velocity=0
WQ Output face area=0
WQ Output face dispersion=0
WQ Output cell volume=0
WQ Output cell surface area=0
WQ Output cell continuity=0
WQ Output face conc=0
WQ Output face dconc_dx=0
WQ Output face courant=0
WQ Output face peclet=0
WQ Output face adv mass=0
WQ Output face disp mass=0
WQ Output cell mass=0
WQ Output cell source sink temp=0
WQ Output cell source sink nsm=0
WQ Output MaxMinRange=-1
WQ Daily Max Min Mean=-1
WQ Daily Range=0
WQ Daily Time=0
WQ Create Restart=0
WQ Fixed Restart=0
WQ System Summary=False
Sorting and Armoring Iterations= 10
XS Update Threshold= 0.02
Hydraulics Update Threshold= 0.02
Energy Slope Method= 0
Volume Change Method= 0
XS Weighting Method= 0
Number of US Weighted Cross Sections= 1
Number of DS Weighted Cross Sections= 1
Upstream XS Weight=0.25
Main XS Weight=0.5
Downstream XS Weight=0.25
Number of DS XS's Weighted with US Boundary= 1
Upstream Boundary Weight= 1
Weight of XSs Associated with US Boundary= 0
Number of US XS's Weighted with DS Boundary= 1
Downstream Boundary Weight= 0.5
Weight of XSs Associated with DS Boundary= 0.5
Sediment Output Level= 4
Mass or Volume Output= 0
Output Increment Type= 1
Profile and TS Output Increment= 10
XS Output Flag= 0
XS Output Increment= 10
Disregard all LS=0
Disregard all Conn=0
Disregard all Breaches=0
Disregard all Pumps=0

--- WB_Christina.f03 (steady flow) ---

Flow Title=WB_Christina FIS_ITR_Sumittal
Program Version=4.00
Number of Profiles= 6
Profile Names=100-year,Floodway,10-year,50-year,500-year,Hundred Ultimate
River Rch & RM=westbrchristine,westbrchristine ,22388
     637     637     214     470    1230     854
River Rch & RM=westbrchristine,westbrchristine ,20381
     735     735     251     544    1410    1050
River Rch & RM=westbrchristine,westbrchristine ,17372
     919     919     318     684    1750    1340
River Rch & RM=westbrchristine,westbrchristine ,16521
    1190    1190     418     890    2250    1680
River Rch & RM=westbrchristine,westbrchristine ,13077
    1320    1320     466     987    2470    1910
River Rch & RM=westbrchristine,westbrchristine ,12601
    1450    1450     515    1090    2710    2080
River Rch & RM=westbrchristine,westbrchristine ,8172
    1700    1700     607    1280    3160    2470
River Rch & RM=westbrchristine,westbrchristine ,2463
    2480    2480     815    1820    4820    3010
River Rch & RM=westbrchristine,westbrchristine ,1667
    2600    2600     857    1910    5040    3180
River Rch & RM=westbrchristine,westbrchristine ,-25
    2690    2690     875    1970    5270    3390
Boundary for River Rch & Prof#=westbrchristine,westbrchristine , 1
Up Type= 0
Dn Type= 1
Dn Known WS=105.5
Boundary for River Rch & Prof#=westbrchristine,westbrchristine , 2
Up Type= 0
Dn Type= 1
Dn Known WS=105.9
Boundary for River Rch & Prof#=westbrchristine,westbrchristine , 3
Up Type= 0
Dn Type= 1
Dn Known WS=104
Boundary for River Rch & Prof#=westbrchristine,westbrchristine , 4
Up Type= 0
Dn Type= 1
Dn Known WS=104.9
Boundary for River Rch & Prof#=westbrchristine,westbrchristine , 5
Up Type= 0
Dn Type= 1
Dn Known WS=109.5
Boundary for River Rch & Prof#=westbrchristine,westbrchristine , 6
Up Type= 0
Dn Type= 1
Dn Known WS=106.6
DSS Import GetInterval= 0
DSS Import GetPeak= 0
DSS Import FillOption= 0

--- WB_Christina.g13 (geometry) ---

Geom Title=WB_Christina_ITR_Submittal
Program Version=4.00
BEGIN GEOM DESCRIPTION:
stream distance in feet from MD/DE state line
END GEOM DESCRIPTION:

River Reach=westbrchristine ,westbrchristine
Reach XY= 30
1647041.48651168739548.3150035031646690.89528579738567.501917486
1646809.01726031737249.577727575   1647158.94437  736439.2632008
 1647790.1792307  736247.3545486 1648106.3577449  734633.9057847
 1647736.3738377   733920.653825 1647855.8279492  733890.5350592
 1647837.9608896  733369.8886654  1648098.820098  732981.3565174
 1647958.4778508  732532.7215626 1648027.2774032  732171.4062868
 1647811.4155262  731797.5866334 1647573.6303738  731687.8317774
 1647166.1590957  729797.44488441647202.94134079727482.646944094
 1647586.9085215  727302.3837987 1648123.2945169   726740.362551
 1649099.0484762  726379.6248876 1649841.7833646   726402.883813
 1650893.7068124  726833.9491293 1651338.0685755  726865.5099657
 1651308.9707852  727049.0813205 1651468.2429418  727047.2946312
  1651480.494648  727185.63677781652620.43205268727412.120349038
 1652810.7234352  727583.81715751653252.02289208727433.063622728
 1653247.0101259  727616.6997651 1653670.4391461   727495.821193

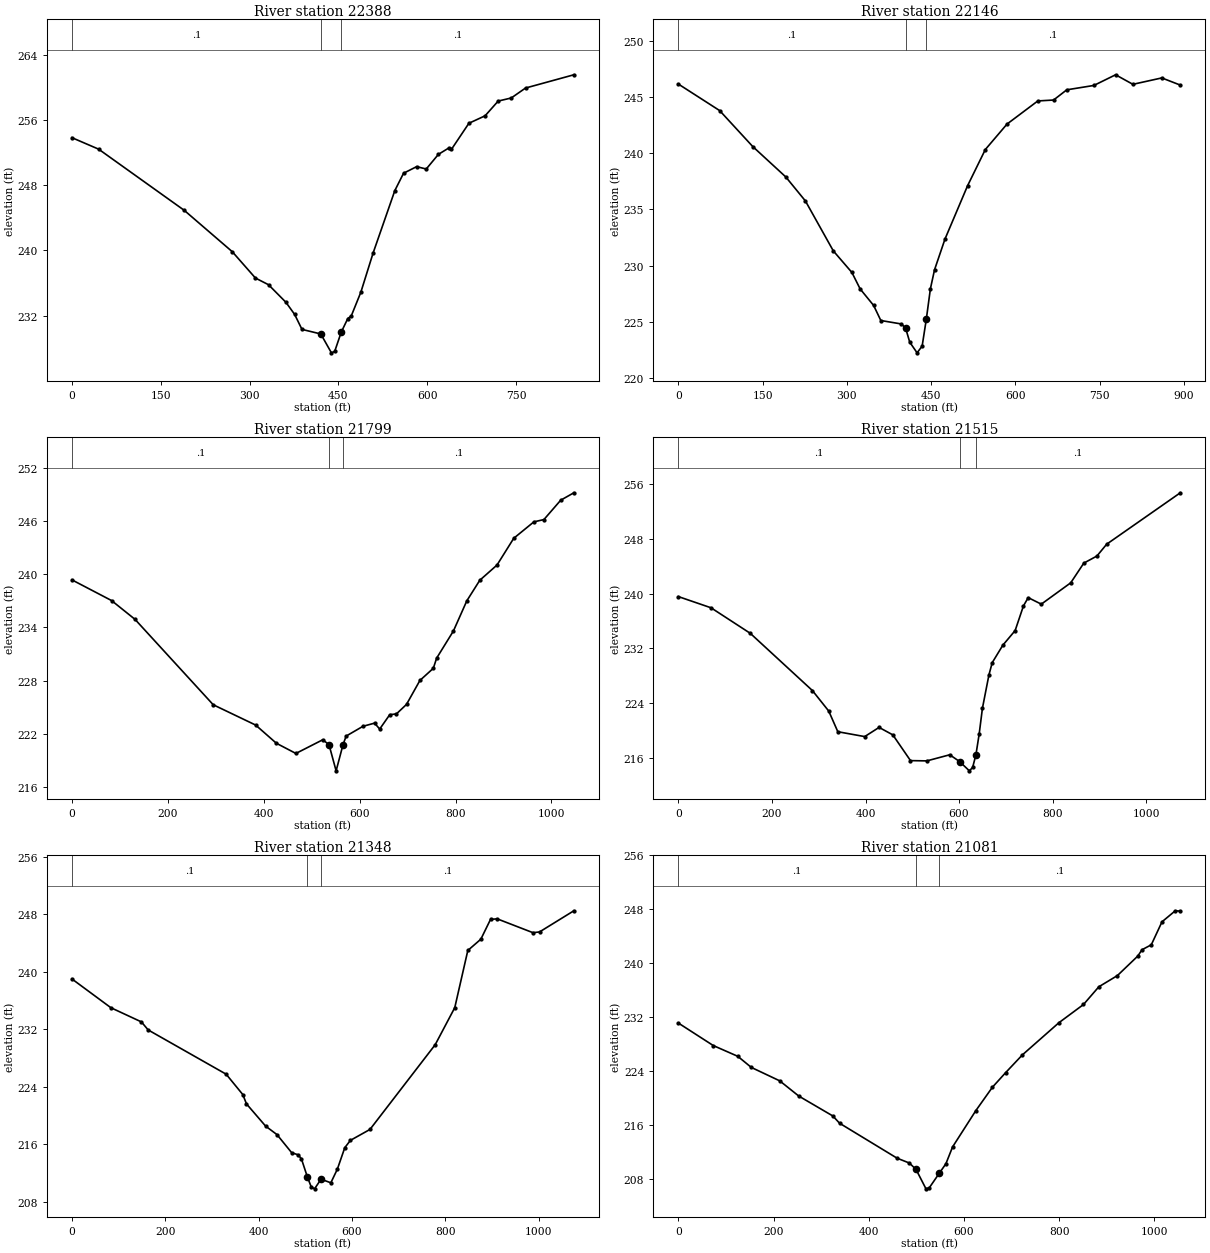
Type RM Length L Ch R = 1 ,22388   ,242.1,242.04,241.74
XS GIS Cut Line= 2
  1647372.783118  739123.5114938 1646568.2267256  739390.7287649
#Sta/Elev= 30
       0  253.86   45.06  252.45  189.71  244.93  270.79  239.85  309.94  236.61
  332.02  235.79  361.45  233.63  376.16  232.14  388.55   230.3  420.31  229.74
  438.27  227.42  443.79  227.59  454.84  229.96  465.88  231.63  471.82  231.96
  487.98  234.87  508.61  239.67  545.39  247.36  560.11  249.49  582.18   250.3
  598.44  250.01  618.97  251.81  637.11  252.62  641.05  252.43  670.48  255.63
  697.87  256.55  719.96  258.36  742.05  258.74  766.13  259.96  847.77  261.59
#Mann= 3 , 0 , 0
       0      .1       0  420.31    .035       0  454.84      .1       0
Bank Sta=420.31,454.84
XS Rating Curve= 0 ,0
Exp/Cntr=0.3,0.1

Type RM Length L Ch R = 1 ,22146   ,320.22,346.99,367.16
XS GIS Cut Line= 2
 1647274.0288983  738901.8954034 1646425.9044594  739183.6353804
#Sta/Elev= 30
       0  246.16   73.44   243.8  132.31   240.6  191.17  237.89  226.13  235.75
  275.84   231.3   308.9  229.38  323.62  227.91  347.64  226.44  360.41   225.1
   397.2  224.79  404.55  224.42  411.91  223.17  424.97  222.22  433.99  222.82
  441.34  225.19   448.7  227.93  456.06  229.62  474.68  232.36  514.92  237.11
  546.48  240.33  585.14   242.6  640.01  244.66  667.99  244.74  691.52  245.65
  739.79  246.04  778.46  246.99  809.25  246.14  860.75  246.71   893.7  246.07
#Mann= 3 , 0 , 0
       0      .1       0  404.55    .035       0  441.34      .1       0
Bank Sta=404.55,441.34
XS Rating Curve= 0 ,0
Exp/Cntr=0.3,0.1

Type RM Length L Ch R = 1 ,21799   ,282.57,284.04,282.69
XS GIS Cut Line= 2
 1647279.8379616   738758.701811 1646234.2051071  738712.2292328
#Sta/Elev= 30
       0  239.35   82.57  237.02   131.5   234.9  294.64  225.27  383.13  222.98
  426.31  220.93  467.01  219.78  522.92  221.32  536.03  220.78  550.88  217.82
  565.29  220.77  571.85  221.74   606.8  222.84  631.12   223.2  641.75  222.53
  662.72  224.15   676.7  224.24  697.67  225.31  725.63  228.01  753.58  229.38
  760.57  230.53  795.52  233.59  823.48  236.99  850.57  239.31  886.39  241.02
  921.34  244.04  963.28  245.89  984.25  246.15 1019.19  248.33 1046.67  249.17
#Mann= 3 , 0 , 0
       0      .1       0  536.03    .035       0  565.29      .1       0
Bank Sta=536.03,565.29
XS Rating Curve= 0 ,0
Exp/Cntr=0.3,0.1

Type RM Length L Ch R = 1 ,21515   ,167.08,166.49,165.6
XS GIS Cut Line= 2
  1647308.883326  738479.8663657 1646237.1096388  738427.5847241
#Sta/Elev= 30
       0  239.56   69.72  237.93  153.61  234.21  286.45  225.87   321.4  222.88
  340.81  219.87   398.3  219.16  429.01   220.5  458.41  219.41  496.18  215.66
  531.14  215.62  580.07  216.51  601.05  215.53  622.02  214.17  629.01  214.66
     636  216.49  642.99  219.52  649.99   223.3  663.97  228.18  670.96  229.94
   693.6  232.48   719.9  234.61  737.69  238.21  747.86  239.41  775.83  238.46
  838.75  241.57  866.71  244.44  894.68  245.47  915.65   247.2 1073.05  254.69
#Mann= 3 , 0 , 0
       0      .1       0  601.05    .035       0     636      .1       0
Bank Sta=601.05,636
XS Rating Curve= 0 ,0
Exp/Cntr=0.3,0.1

Type RM Length L Ch R = 1 ,21348   ,268.31,267.54,266.25
XS GIS Cut Line= 2
 1647318.7587527   738307.336951 1646244.0805338  738266.6734599
#Sta/Elev= 30
       0     239   83.47     235  148.83  233.03  163.36  231.91   330.4  225.76
  366.07  222.93  373.98  221.63  414.99  218.54  439.34  217.36  470.89  214.84
  484.86  214.55  491.85  213.96   504.7  211.43  512.82  210.07   519.8  209.82
  533.75  211.16  554.74  210.66  568.72  212.56  584.59  215.54  596.67  216.56
   638.6  218.08  778.35  229.86  820.28  235.01  848.23  242.96  876.18  244.53
  896.89  247.28  911.12  247.36  987.99  245.43 1001.96  245.54 1075.45  248.48
#Mann= 3 , 0 , 0
       0      .1       0   504.7    .035       0  533.75      .1       0
Bank Sta=504.7,533.75
XS Rating Curve= 0 ,0
Exp/Cntr=0.3,0.1

Type RM Length L Ch R = 1 ,21081   ,224.46,224.58,225.68
XS GIS Cut Line= 2
 1647298.4270072  738028.5015294 1646244.0805338  738008.1697601
#Sta/Elev= 30
       0  231.11   73.16  227.78  124.72  226.18   153.2  224.53  212.84  222.54
   252.9  220.28  324.59  217.32  338.56  216.25  459.43  211.06  485.22  210.34
  499.19   209.4  520.15  206.51  527.13  206.67  548.08  208.82  562.05  210.24
  576.02  212.73  624.91  218.12  659.83   221.6  687.31  223.74  722.69  226.39
  799.51  231.17  851.11  233.87  883.32   236.5  922.32  238.16  965.05  241.05
  974.11     242  993.54  242.73 1016.02  246.14 1043.96  247.78 1054.54  247.73
#Mann= 3 , 0 , 0
       0      .1       0  499.19    .035       0  548.08      .1       0
Bank Sta=499.19,548.08
XS Rating Curve= 0 ,0
Exp/Cntr=0.3,0.1

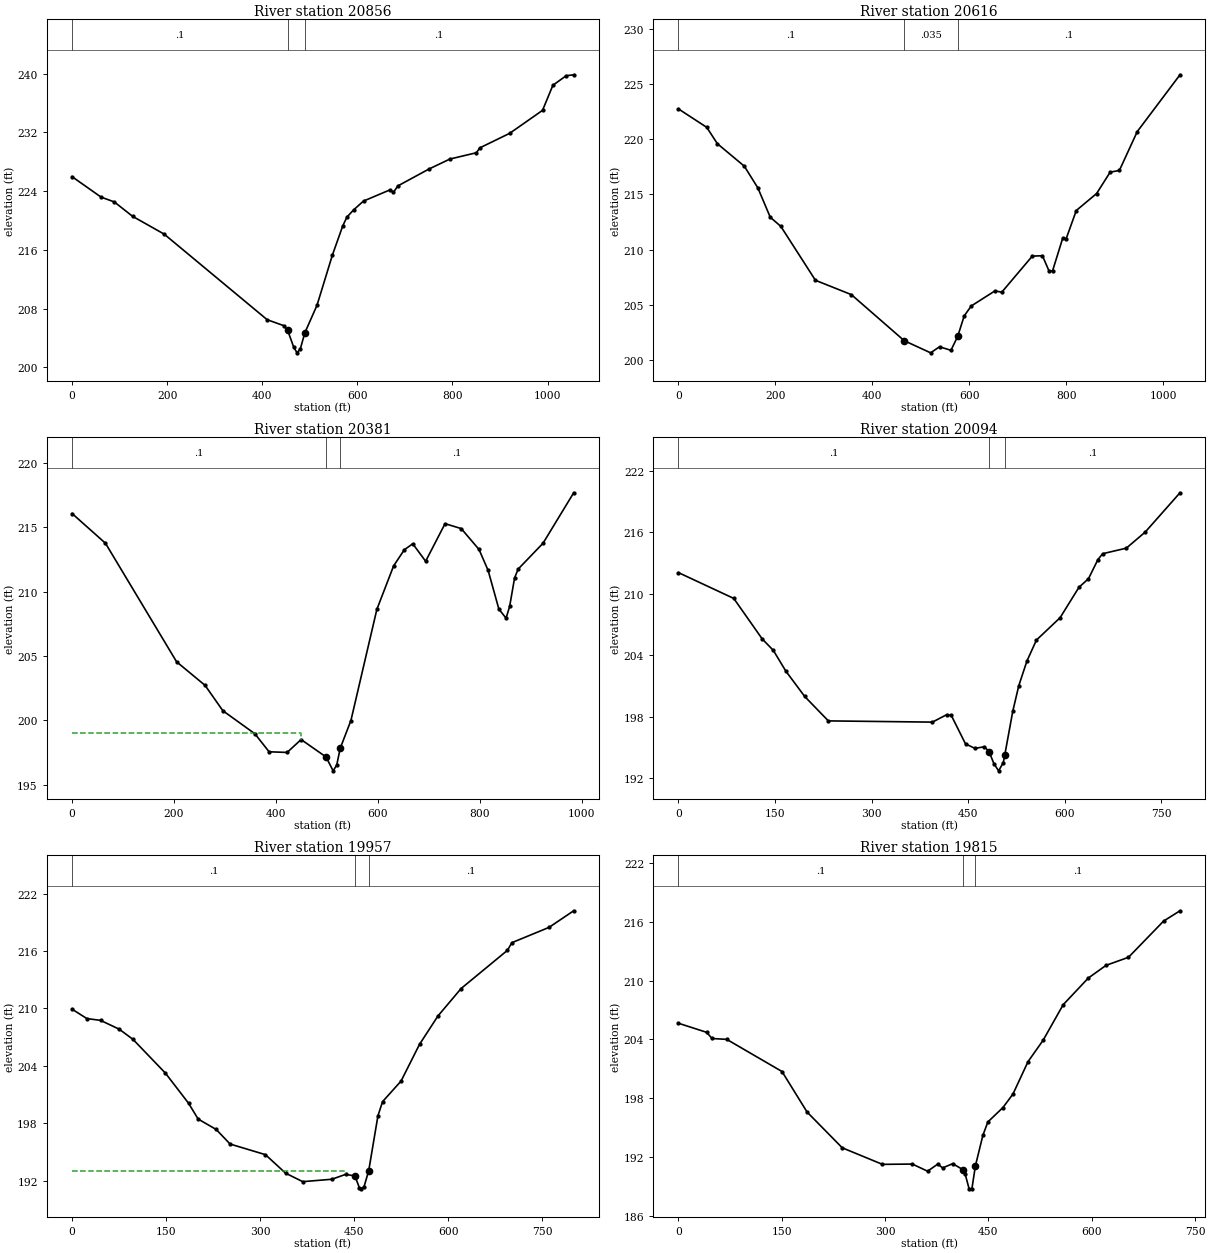
Type RM Length L Ch R = 1 ,20856   ,239.28,240.15,239.25
XS GIS Cut Line= 2
 1647307.1406022  737813.5658762 1646252.7941289  737775.8069168
#Sta/Elev= 30
       0  225.96   60.95  223.18    88.9  222.52  127.12  220.57  193.71  218.14
  410.32  206.49  445.25  205.68  453.23  205.08  466.22  202.74   473.2  201.98
  480.19  202.54  489.46  204.69  515.13  208.45  547.44  215.27  569.18  219.24
  578.01  220.45  591.99  221.43  612.95  222.64  668.85  224.17  675.83  223.82
  685.13   224.7  750.35  226.99  794.62  228.36  850.52  229.22  857.51  229.88
  920.39  231.86  989.49  234.99 1011.23   238.4 1039.18   239.7 1055.02  239.83
#Mann= 3 , 0 , 0
       0      .1       0  453.23    .035       0  489.46      .1       0
Bank Sta=453.23,489.46
XS Rating Curve= 0 ,0
Exp/Cntr=0.3,0.1

Type RM Length L Ch R = 1 ,20616   ,239.13,235.17,233.48
XS GIS Cut Line= 2
 1647333.2814349  737577.7175853 1646299.2667071  737537.0540705
#Sta/Elev= 30
       0  222.76   58.63  221.08   80.46   219.6  136.04  217.56  163.99  215.59
  189.57  212.93  211.39   212.1  282.79  207.21  356.88  205.91  465.99  201.73
  520.39  200.63  538.74  201.18  562.32  200.86   576.3  202.13  589.66  203.98
  604.21  204.88  653.17  206.25  667.14  206.13  730.04   209.4     751  209.44
  764.98  208.02  771.97  208.07  792.93  211.04  799.92  210.97  820.88  213.54
  862.81  215.08  890.77  217.02  909.73  217.17  946.67   220.7 1034.81  225.85
#Mann= 3 , 0 , 0
       0      .1       0  465.99    .035       0   576.3      .1       0
Bank Sta=465.99,576.3
XS Rating Curve= 0 ,0
Exp/Cntr=0.3,0.1

Type RM Length L Ch R = 1 ,20381   ,275.25,287,312.25
BEGIN DESCRIPTION:
Based on aerial photo the depression in the left overbank appears to be some type of detention pond. It does not really extend for a significant longitudial distance. Blocked out the bottom to reduce conveyance.
END DESCRIPTION:
XS GIS Cut Line= 2
 1647318.7587527  737326.7656964 1646334.1211347  737318.0520776
#Sta/Elev= 30
       0  216.07   65.55  213.76  205.21  204.55  261.08  202.72  295.99  200.75
  358.84  198.96  386.77  197.56  422.16  197.51  449.62  198.51   498.5  197.16
  512.47  196.08  519.45  196.52  526.44  197.84  547.38  199.99  598.29  208.62
  631.18     212  652.13  213.25  668.75  213.72  694.03  212.36  732.16  215.28
  763.86   214.9  798.78  213.28   816.7  211.65  837.84  208.64  851.93  207.94
  858.98  208.86  868.61  211.06  875.59  211.75  924.47  213.76  984.68  217.68
#Mann= 3 , 0 , 0
       0      .1       0   498.5    .035       0  526.44      .1       0
#XS Ineff= 2 , 0
       0  449.62     199               0
Permanent Ineff=
       T       F
Bank Sta=498.5,526.44
XS Rating Curve= 0 ,0
Exp/Cntr=0.3,0.1

Type RM Length L Ch R = 1 ,20094   ,134.3,136.25,140.02
XS GIS Cut Line= 2
 1647341.9950299  737198.9661123 1646601.3384296  736957.8896502
#Sta/Elev= 30
       0  212.06   86.03  209.54  130.09   205.6   147.5  204.47   166.8  202.46
  196.18  199.98  232.89   197.6  394.45  197.48  416.48   198.2  423.82  198.13
  445.85  195.36  460.54  194.92  475.23  195.08  482.57  194.59  489.91  193.43
  497.26  192.73   504.6  193.54  506.78  194.26  519.29  198.55  528.55  201.03
  541.32  203.45     556  205.48  592.72  207.66  622.09  210.63  636.78  211.46
  651.47  213.33  658.81   213.9  695.53  214.44   724.9  216.01   778.9  219.84
#Mann= 3 , 0 , 0
       0      .1       0  482.57    .035       0  506.78      .1       0
Bank Sta=482.57,506.78
XS Rating Curve= 0 ,0
Exp/Cntr=0.3,0.1

Type RM Length L Ch R = 1 ,19957   ,145.87,142.55,142.34
BEGIN DESCRIPTION:
Start of Approximate Analyses XS.
END DESCRIPTION:
XS GIS Cut Line= 2
 1647394.2766714  737079.8801471 1646636.1928573  736824.2810028
#Sta/Elev= 30
       0  209.92   23.59  208.94   45.47  208.75   75.18  207.83   97.28  206.76
  148.87  203.24  185.71   200.1  201.11  198.44  229.93  197.35  252.03  195.83
  308.43  194.72  340.46  192.79  367.88   191.9  414.15  192.15  436.26  192.66
     451   192.5  458.37  191.24  461.42  191.15  465.74  191.39  473.11  193.05
  487.84  198.79  495.21  200.26  524.69  202.41  554.17  206.25  583.64  209.22
  620.49  212.08  694.18  216.06  701.55  216.87   760.5  218.46  800.01   220.2
#Mann= 3 , 0 , 0
       0      .1       0     451    .035       0  473.11      .1       0
#XS Ineff= 2 , 0
       0     436     193               0
Permanent Ineff=
       T       F
Bank Sta=451,473.11
XS Rating Curve= 0 ,0
Exp/Cntr=0.3,0.1

Type RM Length L Ch R = 1 ,19815   ,151.4,211.58,242.85
BEGIN DESCRIPTION:
XS 'X' FEMA 29145 HEC2 Adjusted Upper Limit of Detailed Study.
END DESCRIPTION:
XS GIS Cut Line= 2
 1647425.2461353  736925.0468967 1646727.6789034  736716.3904294
#Sta/Elev= 30
       0  205.66   41.08  204.73   48.86   204.1   70.24  204.01  150.41  200.73
  186.85  196.59  237.87  192.94  296.18  191.25  339.63  191.28  361.78  190.55
  376.36  191.27  383.65  190.89  398.22  191.32  412.73  190.72  416.32  190.25
  422.03  188.75  426.05  188.75  431.17   191.1  441.95   194.2  449.24  195.58
  471.11  197.05  485.68  198.43  507.55  201.74  529.42  203.92  558.57  207.55
  595.01  210.27  620.81  211.57  653.32  212.39  704.34  216.09  728.11  217.14
#Mann= 3 , 0 , 0
       0      .1       0  412.73    .035       0  431.17      .1       0
Bank Sta=412.73,431.17
XS Rating Curve= 0 ,0
Exp/Cntr=0.5,0.3

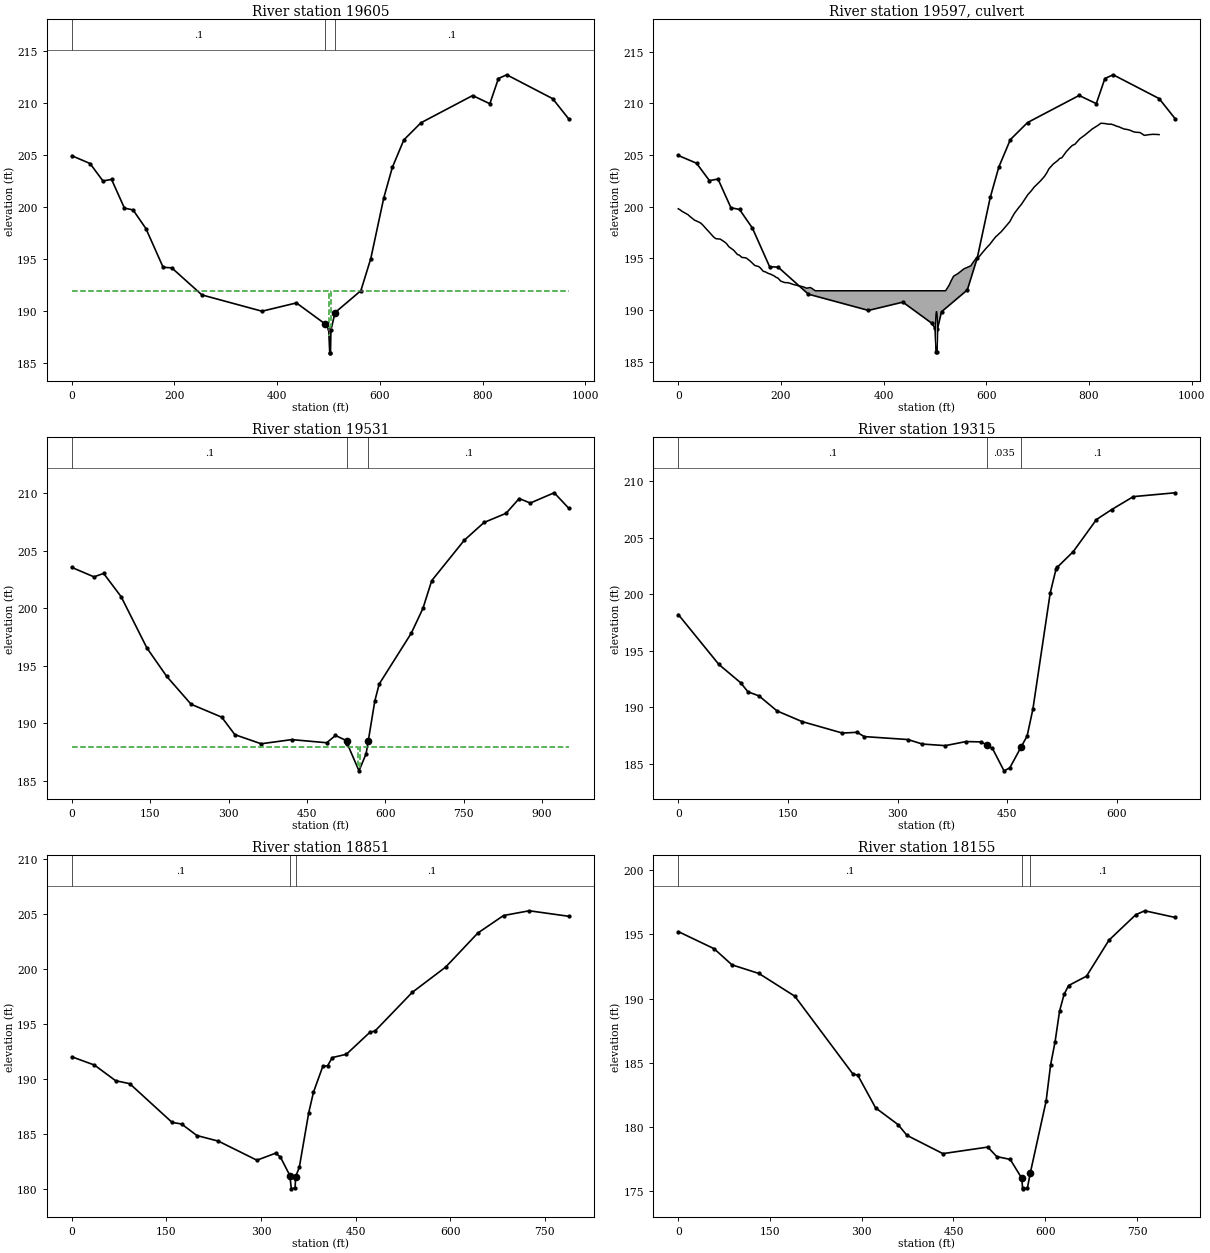
Type RM Length L Ch R = 1 ,19605   ,75.58,74.12,98.78
BEGIN DESCRIPTION:
HEC2 28914
END DESCRIPTION:
XS GIS Cut Line= 2
 1647457.4030497  736883.7930312 1646650.2411153  736349.5731362
#Sta/Elev= 30
       0  204.95   35.52   204.2   60.64  202.52   77.39  202.67  102.51   199.9
  119.26  199.73  144.38  197.93  177.87   194.2  194.62  194.15  253.43  191.54
  370.47  189.97  437.46  190.77  493.82  188.73  500.38  188.23  502.41  185.96
  503.86  185.96  504.73  188.16  512.82  189.84  563.06  191.95  582.38  195.04
  607.68  200.89  624.31  203.82   646.8  206.48   680.3  208.13  780.78  210.75
  814.28  209.96  831.02  212.39  847.18  212.75  936.63  210.45  967.94   208.5
#Mann= 3 , 0 , 0
       0      .1       0  493.82    .035       0  512.82      .1       0
#XS Ineff= 2 , 0
       0     501  191.87     505       0  191.87
Permanent Ineff=
       F       F
Bank Sta=493.82,512.82
XS Rating Curve= 0 ,0
Exp/Cntr=0.5,0.3

Type RM Length L Ch R = 2 ,19597   ,,,
BEGIN DESCRIPTION:
Jackson Hall School Road. Culvert data and embankment width taken from supplied bridge data base. Embankment profile extracted from DEM.
END DESCRIPTION:
Bridge Culvert--1,0,-1,-1, 0
Deck Dist Width WeirC Skew NumUp NumDn MinLoCord MaxHiCord MaxSubmerge Is_Ogee
27.5,18,2.6,0, 165, 165, , , 0.95, 0, 0,0,,
       0   4.646   5.888    6.49  14.308  18.988  22.727  30.448  31.147  31.485
  39.566  43.983  47.986   56.25  56.406  56.481  64.825  68.979  73.245  81.477
  81.665  82.052  90.084  93.975  98.504 106.473 106.923 107.854 115.343 118.971
 123.763 131.468 132.182 133.656 140.602 143.966 149.021 156.464 157.441 159.458
 165.861 168.962  174.28  181.46   182.7  185.26 191.119 193.958 199.539 206.455
 207.959 211.062 216.378 218.953 224.798 231.451 233.217 236.864 241.637 243.949
 250.057 256.447 258.476 262.666 266.896 520.686 527.904   531.4 536.323 543.898
 544.743 546.488 553.163 556.395 561.582 568.893 570.002  572.29 578.421 581.391
 586.841 593.889 595.261 598.092  603.68 606.387   612.1  613.05 618.847 620.541
 624.141 628.986 631.266  637.43 643.684 645.874 650.529 654.319 656.102 662.763
  668.52 671.207 676.918 679.652 680.938 688.096 693.356  696.54 703.306 704.985
 705.774 713.429 718.192 721.873 729.695 730.318 730.611 738.762 743.029 747.206
 755.447 755.651 756.083 764.095 767.865 772.539 780.283 780.984 782.472 789.428
 792.701 797.872 805.119 806.317  808.86 814.761 817.538 823.205 829.956  831.65
 835.249 840.094 842.374 848.538 854.792 856.982 861.638 865.427  867.21 873.871
 879.628 882.315 888.026  890.76 892.046 899.204 904.464 907.648 914.415 916.093
 916.882 924.537 929.301 932.981 936.656
 199.798 199.657 199.592 199.572  199.36 199.223 199.052  198.74 198.708 198.701
 198.523 198.405 198.211 197.753 197.743  197.74 197.278 197.062 196.905 196.868
 196.863 196.854 196.593  196.43  196.13 195.844 195.829 195.792  195.37 195.315
 195.098 195.051 195.034 194.994 194.716 194.557 194.317 194.213 194.172 194.096
 193.737 193.715  193.57 193.441 193.393  193.35 193.154 193.104 192.805 192.682
 192.654 192.664 192.616 192.567 192.467 192.398 192.351 192.331  192.27 192.242
 192.118 192.185 192.154 192.019  191.87  191.87 192.435 192.826 193.283 193.509
 193.534 193.599 193.868  193.99   194.1 194.257 194.287  194.47  194.89 195.056
 195.218 195.641 195.735 195.891 196.198 196.326 196.705 196.764 197.121 197.175
 197.352 197.573 197.704 198.043 198.419 198.557 198.992 199.317 199.445 199.886
 200.235 200.431 200.861 201.069  201.16 201.561 201.902  202.05 202.389 202.462
 202.502 202.934 203.299 203.652 204.083 204.122 204.132 204.445 204.663 204.732
 205.291 205.309 205.334 205.759  205.93 206.029 206.474   206.5 206.575 206.833
 206.949 207.163 207.453  207.51 207.588  207.78  207.86 208.068 208.041 208.033
 207.994 207.969 207.986 207.895 207.754 207.751 207.644 207.571 207.522 207.466
 207.398 207.333 207.221 207.197 207.194 207.169 207.007 206.894 206.947 206.956
 206.961 206.994  206.99 206.981 206.965
                                                                                
                                                                                
                                                                                
                                                                                
                                                                                
                                                                                
                                                                                
                                                                                
                                                                                
                                                                                
                                                                                
                                                                                
                                                                                
                                                                                
                                                                                
                                                                                
                                        
      3640.6457741.8880542.4897750.3076554.9876358.7272666.4477967.1468767.48548
75.5664779.9833483.9860892.2498192.4056992.48119100.8253 104.979109.2449117.4769
117.6645118.0518126.0841129.9747134.5037142.4726142.9233143.8539151.3429154.9705
159.7625167.4683168.1821169.6559176.6018179.9662185.0214 192.464 193.441195.4579
201.8606204.9619210.2802217.4597218.6998221.2599227.1194229.9576 235.539242.4554
243.9586247.0619252.3782254.9533260.7978267.4511269.2174 272.864 277.637 279.949
286.0566292.4469294.4763 298.666302.8958556.6862563.9037567.3997572.3233579.8975
580.7429582.4882589.1625592.3953597.5821604.8932606.0017608.2902614.4213617.3911
622.8409629.8889631.2605634.0922639.6801642.3868648.0997649.0503654.8474656.5413
660.1407664.9856667.2655673.4299679.6837681.8743686.5293690.3186692.1018698.7629
704.5199707.2072712.9178715.6516 716.938724.0959729.3561732.5402739.3063740.9846
741.7743749.4289754.1924757.8732765.6948766.3175766.6105774.7618779.0287783.2062
791.4468791.6505792.0834800.0948803.8649808.5392816.2831816.9835818.4719825.4278
828.7012833.8721841.1193842.3165844.8604850.7608853.5375859.2051865.9556867.6495
 871.249876.0938878.3737884.5381890.7918892.9824897.6375901.4268  903.21909.8711
915.6281918.3154 924.026926.7598928.0462 935.204940.4644943.6484950.4145952.0927
952.8824 960.537965.3006968.9814972.6556
199.7983199.6568199.5918199.5715199.3595199.2231199.0522198.7404198.7081198.7006
198.5225 198.405198.2113197.7526197.7432197.7395197.2783 197.062196.9054196.8676
196.8631196.8541196.5931196.4303196.1296195.8444 195.829195.7919195.3696195.3148
 195.098195.0508195.0341194.9943194.7164194.5574194.3165194.2125194.1719194.0956
193.7365193.7149193.5703 193.441193.3932  193.35193.1541193.1039192.8045192.6823
192.6538192.6636192.6162192.5668192.4672192.3976192.3506192.3309192.2697 192.242
192.1175192.1852192.1544192.0188  191.87  191.87192.4348192.8262193.2834193.5089
193.5343193.5986 193.868193.9898194.0996194.2574194.2872194.4695194.8904195.0563
195.2177195.6414195.7351195.8913196.1975196.3257196.7054 196.764197.1212197.1754
197.3516197.5729197.7035198.0431198.4191198.5569198.9922199.3166199.4445199.8863
200.2354200.4307200.8605201.0692  201.16201.5611201.9021202.0497202.3892202.4615
202.5015202.9336203.2986203.6516 204.083204.1216 204.132204.4448204.6625204.7321
205.2909205.3093205.3344205.7587205.9299206.0288 206.474206.4998206.5754206.8325
206.9485207.1626207.4532207.5099207.5879207.7795207.8599208.0683208.0411208.0327
207.9942207.9691207.9858207.8949207.7535207.7513207.6438207.5713207.5223207.4656
207.3977207.3331207.2208207.1965207.1939207.1693207.0065 206.894206.9466206.9562
206.9611206.9942  206.99206.9812206.9647
                                                                                
                                                                                
                                                                                
                                                                                
                                                                                
                                                                                
                                                                                
                                                                                
                                                                                
                                                                                
                                                                                
                                                                                
                                                                                
                                                                                
                                                                                
                                                                                
                                        
BR Coef=-1 , 0 , 0 ,, 0 ,,,0.8,0,,1,
WSPro=,,,, 1 ,,,, 0 ,,,, 0 ,,,,-1 ,-1 ,-1 , 0 , 0 , 0 , 0 , 0
Culvert=1,4,,30,0.013,0.2,1,1,3,185.87,503,185.87,549.69,Culvert #1  , 0 ,21.5
Culvert Bottom n=0.013
BC Design=,, 0 ,, 0 ,,,,,,
BC Use User HTab Curves=0
BC User HTab FreeFlow(D)= 0

Type RM Length L Ch R = 1 ,19531   ,162.99,215.28,226.05
BEGIN DESCRIPTION:
HEC 2 28883
END DESCRIPTION:
XS GIS Cut Line= 2
 1647541.3852194  736851.1332933 1646748.2203053  736326.2447689
#Sta/Elev= 30
       0  203.55   42.43  202.73   60.87  203.03   94.36  201.01  143.66  196.56
  181.62  194.09  228.33  191.67  286.95  190.55  312.07  189.03  362.31  188.24
  420.92   188.6  487.91  188.33  504.65  188.96  527.16  188.48  527.16  188.26
  549.69  185.89  563.27  187.37   567.3  188.45  580.02  191.97  588.39  193.43
  649.78  197.84  672.12     200  688.87   202.4  751.01   205.9  788.97  207.45
  831.22  208.25  856.34  209.53  877.54  209.14  923.32  210.03  951.11  208.69
#Mann= 3 , 0 , 0
       0      .1       0  527.16    .035       0   567.3      .1       0
#XS Ineff= 2 , 0
       0     547     188     552       0     188
Permanent Ineff=
       F       F
Bank Sta=527.16,567.3
XS Rating Curve= 0 ,0
Exp/Cntr=0.5,0.3

Type RM Length L Ch R = 1 ,19315   ,401,464,338
XS GIS Cut Line= 3
     1647552.649      736745.798      1647262.98       736454.08
1647137.67135436736213.722597838
#Sta/Elev= 30
       0  198.22   55.57   193.8   85.41  192.18   95.36  191.38  110.51  191.02
  135.14  189.69  169.34  188.75  224.65  187.73  244.54   187.8  254.48  187.42
  314.16  187.16  334.05  186.76  365.47  186.62  393.72  186.98  414.13  186.95
  422.03   186.7  429.94  186.37  445.75  184.39  453.65  184.65  469.46  186.54
  477.36  187.47  485.27  189.85  508.98  200.13  516.88  202.22  518.45  202.39
   540.6  203.79  572.22  206.62  592.95   207.5  622.76  208.65  679.99  208.99
#Mann= 3 , 0 , 0
       0      .1       0  422.03    .035       0  469.46      .1       0
Bank Sta=422.03,469.46
XS Rating Curve= 0 ,0
Exp/Cntr=0.3,0.1

Type RM Length L Ch R = 1 ,18851   ,758,696.12,594.6
BEGIN DESCRIPTION:
HEC2 28212 Adjusted
END DESCRIPTION:
XS GIS Cut Line= 3
  1647754.755033  736683.1336153 1647586.8421929  736241.0774065
  1647370.954293  736011.4823025
#Sta/Elev= 30
       0  192.03   35.89  191.28   69.43  189.86   91.84  189.59  159.06  186.07
     174  185.93  198.37  184.88  232.54  184.37  293.52  182.64  323.39  183.28
  330.87  182.92   345.8  181.25  348.11  180.04   354.1  180.13  354.95  181.15
  360.74  181.98  375.68  186.94  383.15   188.8  398.09  191.17  405.56  191.21
  413.03  191.96  435.44  192.26  472.79  194.26  480.81  194.37  539.86  197.88
  592.94  200.18  643.91  203.27  684.68  204.86  725.46  205.29  788.03  204.79
#Mann= 3 , 0 , 0
       0      .1       0   345.8    .035       0  354.95      .1       0
Bank Sta=345.8,354.95
XS Rating Curve= 0 ,0
Exp/Cntr=0.3,0.1

Type RM Length L Ch R = 1 ,18155   ,729.36,783.58,724.55
BEGIN DESCRIPTION:
FEMA V HEC2 27405
END DESCRIPTION:
XS GIS Cut Line= 2
 1648384.2476453  735974.8416845 1647610.9913141  735725.2721919
#Sta/Elev= 30
       0  195.21   58.51  193.88   87.86  192.62  131.88  191.95  190.58  190.18
  285.97   184.1  293.31  184.05  322.66  181.49  359.35  180.19  374.02  179.35
  432.72  177.93   506.1  178.44  520.77   177.7  542.78  177.48   561.6  176.02
  563.02  175.25  564.45  175.19  570.88  175.25  575.44  176.39  601.48  182.02
  608.82  184.84  616.16  186.64   623.5  189.03  630.83  190.32  638.17  191.01
  667.52  191.74  704.21  194.54  748.24  196.53  762.91  196.83  812.53  196.31
#Mann= 3 , 0 , 0
       0      .1       0   561.6    .035       0  575.44      .1       0
Bank Sta=561.6,575.44
XS Rating Curve= 0 ,0
Exp/Cntr=0.3,0.1

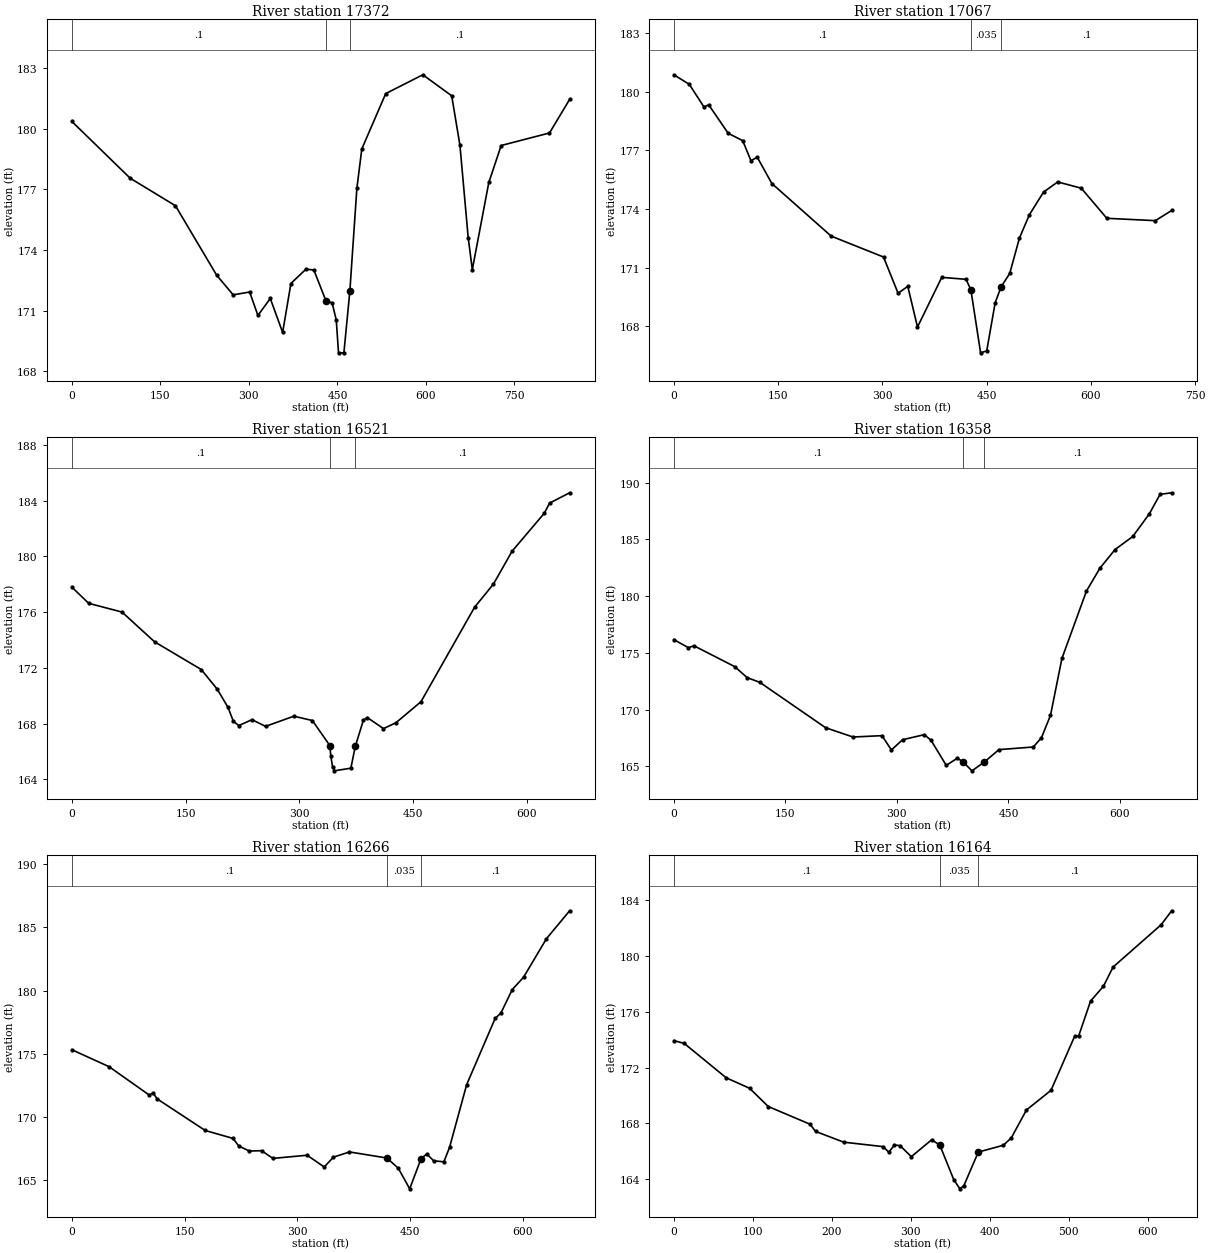
Type RM Length L Ch R = 1 ,17372   ,285.93,304.21,288.82
BEGIN DESCRIPTION:
HEC2 26627 Not a great match new terrain to old XS
END DESCRIPTION:
XS GIS Cut Line= 2
 1648385.2848049  735120.5163184 1647542.2939044  735147.9306553
#Sta/Elev= 30
       0  180.36   98.84  177.55  175.52  176.19  245.38  172.75  273.33  171.78
  301.27  171.92  315.25  170.76  336.21   171.6  357.17  169.92  371.14  172.34
  396.57  173.05   410.1  173.01   430.4  171.49  441.01  171.38  447.99  170.54
  451.83  168.91  460.94  168.91     471  171.95  482.92  177.05   491.3     179
  531.83  181.74  594.71  182.67  643.61  181.63  657.59  179.18  671.56  174.61
  678.55  173.03  706.49  177.34  727.45  179.17  809.32  179.79  843.44  181.45
#Mann= 3 , 0 , 0
       0      .1       0   430.4    .035       0     471      .1       0
Bank Sta=430.4,471
XS Rating Curve= 0 ,0
Exp/Cntr=0.3,0.1

Type RM Length L Ch R = 1 ,17067   ,495.57,546.23,480.43
BEGIN DESCRIPTION:
FEMA U Hec2 26298
END DESCRIPTION:
XS GIS Cut Line= 2
 1648441.5259141  734836.6410883 1647725.5478041   734857.097601
#Sta/Elev= 30
       0  180.86   22.19  180.37   43.15  179.22   50.13  179.32   78.08  177.87
   99.03  177.49   110.8  176.47  119.99  176.64  140.95   175.3  226.26  172.61
  301.62  171.54  322.57  169.69  336.55  170.04  350.52  167.96  385.45   170.5
  420.37   170.4  427.36  169.86  441.33  166.64  450.15  166.74  462.29   169.2
  470.76  170.01  483.25   170.7  497.22  172.51  511.51   173.7  531.89  174.86
  552.26  175.38  586.22  175.06  622.96  173.52  692.82   173.4  716.27  173.92
#Mann= 3 , 0 , 0
       0      .1       0  427.36    .035       0  470.76      .1       0
Bank Sta=427.36,470.76
XS Rating Curve= 0 ,0
Exp/Cntr=0.3,0.1

Type RM Length L Ch R = 1 ,16521   ,165,160,155
BEGIN DESCRIPTION:
FEMA T HEC2 25707
END DESCRIPTION:
XS GIS Cut Line= 2
 1648308.5585461   734330.137728 1647660.0869493  734430.3746568
#Sta/Elev= 30
       0   177.8   22.15  176.64   66.14  176.01  108.98  173.88  170.53  171.89
  191.73  170.47  205.86  169.17  212.92  168.17  219.99  167.87   237.5  168.29
  255.32  167.81  292.58  168.54  317.06  168.23  340.11  166.43  341.34  165.68
  343.61  164.93  345.88  164.62  367.79  164.81  373.58  166.37  384.37  168.27
  389.57  168.44  410.76  167.65  427.21  168.07  460.22  169.58  530.88  176.36
  555.73  178.02  580.34  180.38  622.74   183.1   629.8  183.83  656.17  184.57
#Mann= 3 , 0 , 0
       0      .1       0  340.11    .035       0  373.58      .1       0
Bank Sta=340.11,373.58
XS Rating Curve= 0 ,0
Exp/Cntr=0.3,0.1

Type RM Length L Ch R = 1 ,16358   ,71,91.4,56
XS GIS Cut Line= 2
        1648238.         734134.        1647602.         734353.
#Sta/Elev= 30
       0  176.17   19.57  175.46   26.94  175.63   81.86  173.79   98.37  172.83
  115.49  172.41  204.03  168.41  240.92  167.59  279.89  167.71  292.57  166.45
  307.57  167.35  336.84   167.8  345.89   167.3  366.36  165.09  381.12  165.72
  388.49  165.43   400.9  164.61   417.4  165.38  437.24  166.48  483.41  166.71
  494.41  167.53  506.55   169.5  521.92  174.51  554.92  180.45  572.96  182.46
  593.42  184.11  617.23  185.26  639.37  187.24  653.93  188.97  669.54  189.11
#Mann= 3 , 0 , 0
       0      .1       0  388.49    .035       0   417.4      .1       0
Bank Sta=388.49,417.4
XS Rating Curve= 0 ,0
Exp/Cntr=0.3,0.1

Type RM Length L Ch R = 1 ,16266   ,85,101.6,75
XS GIS Cut Line= 2
      1648211.88         734051.      1647604.25       734312.95
#Sta/Elev= 30
       0  175.32   49.46  173.98  102.76  171.74  108.09   171.9  113.42  171.43
  177.38  168.93   214.4   168.3  221.98   167.7  236.02   167.3   252.3  167.33
  267.45  166.72  312.93  166.97  335.66  166.04  347.95  166.82  369.27  167.23
  419.03  166.75  434.19  165.94  449.35  164.31   464.5   166.7  472.08  167.07
   481.2  166.53  494.82  166.45   502.4   167.6  525.13  172.56  563.03   177.8
  570.61  178.22  585.76  180.08  600.92  181.07  631.24  184.11  662.08  186.32
#Mann= 3 , 0 , 0
       0      .1       0  419.03    .035       0   464.5      .1       0
Bank Sta=419.03,464.5
XS Rating Curve= 0 ,0
Exp/Cntr=0.3,0.1

Type RM Length L Ch R = 1 ,16164   ,54,70,51
XS GIS Cut Line= 3
        1648179.         734041.        1647849.         734108.
        1647609.         734280.
#Sta/Elev= 30
       0  173.93   13.05  173.73   66.26  171.26   95.82  170.51  119.47   169.2
  172.32  167.93  179.45  167.41   215.1  166.64     265  166.32  272.13  165.92
  279.26  166.44  286.39  166.39  300.65   165.6   326.4  166.81  336.75  166.43
  354.39  163.95  362.18  163.29  367.19  163.52   385.5  165.93  417.34  166.42
  427.37  166.96  446.44  168.95  477.51  170.36  507.38  174.23  512.61  174.27
  527.65  176.77  543.94  177.83  556.13  179.21  617.07  182.25  630.33  183.25
#Mann= 3 , 0 , 0
       0      .1       0  336.75    .035       0   385.5      .1       0
Bank Sta=336.75,385.5
XS Rating Curve= 0 ,0
Exp/Cntr=0.3,0.1