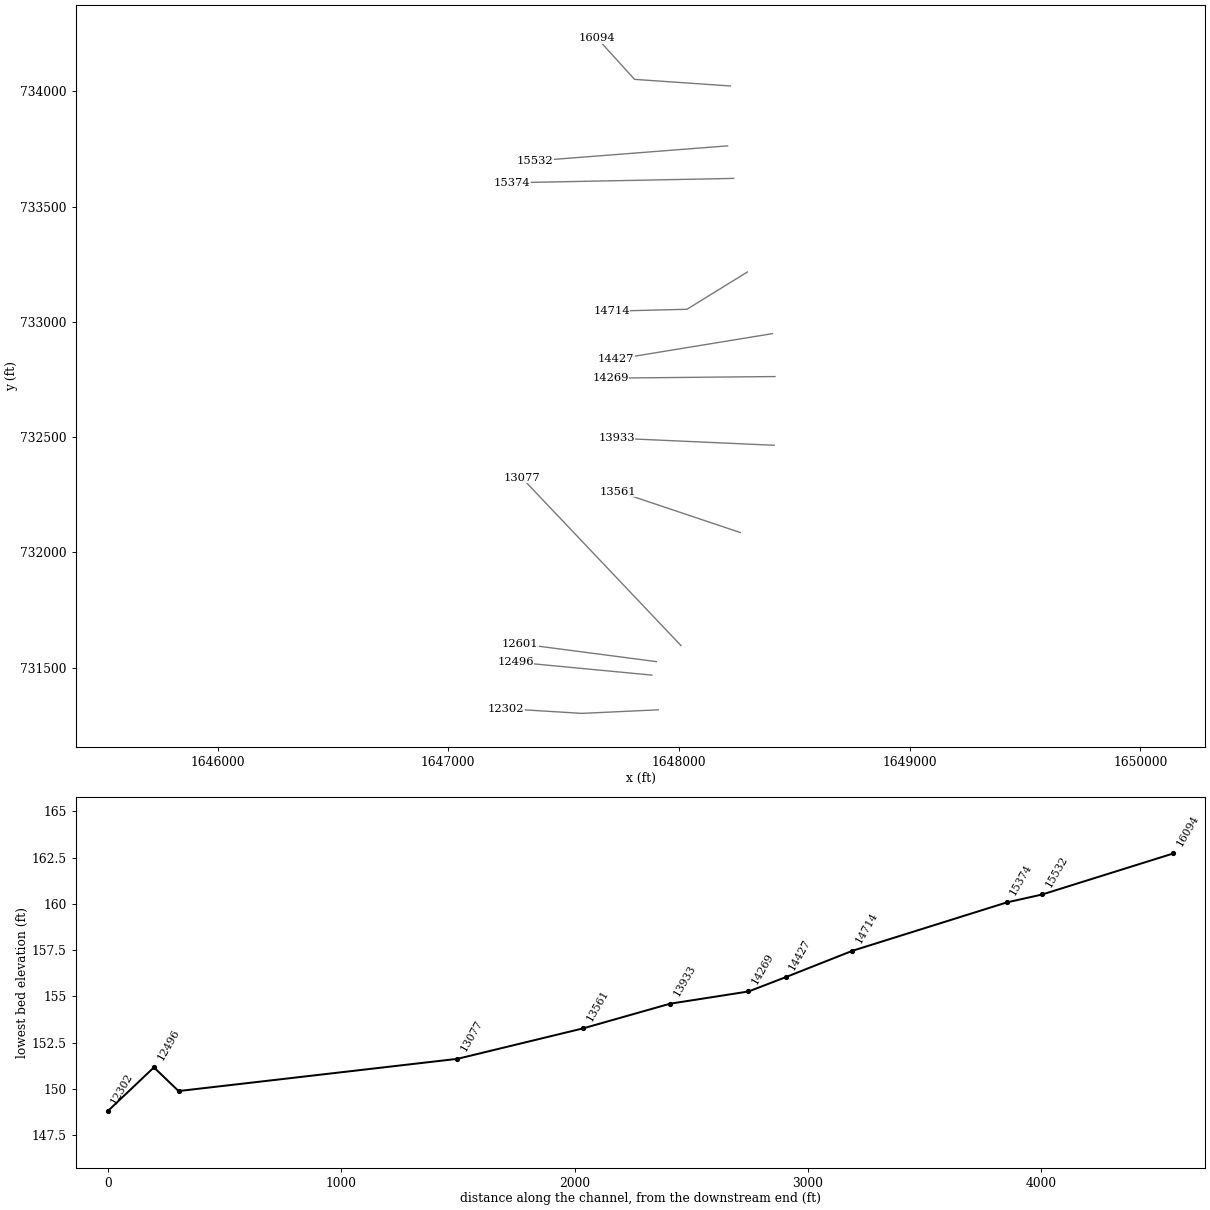
HEC-RAS study WB_Christina.prj: WB_Christina

--- WB_Christina.g13 (geometry) --- (continued)

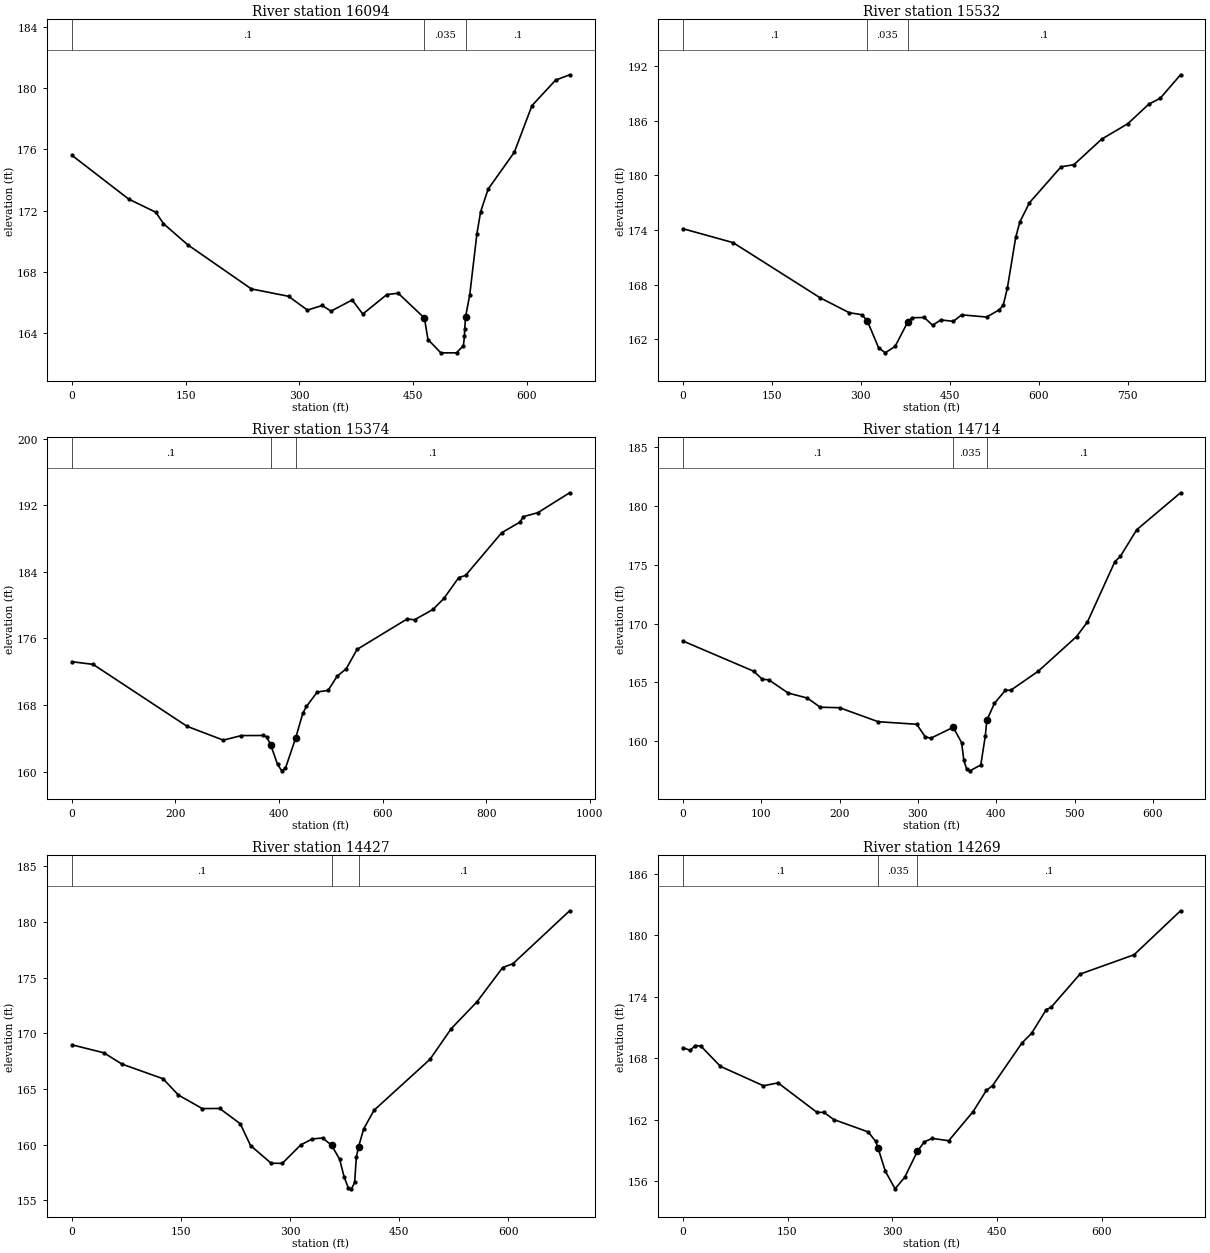
Type RM Length L Ch R = 1 ,16094   ,312.87,562.39,418.4
BEGIN DESCRIPTION:
FEMA S HEC2 25226
END DESCRIPTION:
XS GIS Cut Line= 3
 1648222.6411786  734023.2899904 1647807.3738786  734051.9291129
 1647645.7673881  734229.9007993
#Sta/Elev= 30
       0  175.62   74.96  172.76   110.8   171.9  120.79  171.16   152.8  169.78
  236.79   166.9  285.79  166.42  310.68  165.52  330.32  165.82  341.78  165.45
  369.78  166.18  383.78  165.26  415.44  166.53  430.47  166.62  465.08     165
  469.76   163.6  486.75  162.73  507.43  162.73  516.49   163.2  517.91   163.8
  518.19  164.27  519.45  165.09  524.87  166.51   534.3  170.49  539.23  171.93
  549.11  173.41  583.72  175.82  606.97  178.86  638.13  180.52  656.65  180.87
#Mann= 3 , 0 , 0
       0      .1       0  465.08    .035       0  519.45      .1       0
Bank Sta=465.08,519.45
XS Rating Curve= 0 ,0
Exp/Cntr=0.3,0.1

Type RM Length L Ch R = 1 ,15532   ,125,152,120
BEGIN DESCRIPTION:
Additional XS New
END DESCRIPTION:
XS GIS Cut Line= 2
 1648210.5183984  733763.5065599 1647374.3810881  733698.3975009
#Sta/Elev= 30
       0  174.14   84.71  172.61  231.79  166.54  280.38  164.92  301.83  164.69
  310.76  164.05  329.85  161.08  341.14  160.51  357.86  161.23  378.88  163.87
  385.88  164.36  406.89  164.39   420.9  163.54  434.91  164.12  455.92  163.97
  469.93  164.68  511.95  164.44  532.96  165.22  539.97  165.73  546.97  167.64
  560.98  173.19  567.98  174.88   584.2  176.99  637.37  180.93  659.03  181.16
  705.72  183.96  750.09  185.67  785.11   187.8  804.46  188.45  838.67  191.03
#Mann= 3 , 0 , 0
       0      .1       0  310.76    .035       0  378.88      .1       0
Bank Sta=310.76,378.88
XS Rating Curve= 0 ,0
Exp/Cntr=0.3,0.1

Type RM Length L Ch R = 1 ,15374   ,553.48,660.4,592.2
BEGIN DESCRIPTION:
HEC2 24500
END DESCRIPTION:
XS GIS Cut Line= 2
 1648236.8958847  733622.3289194 1647275.6738046  733603.5733513
#Sta/Elev= 30
       0   173.2   41.01  172.88   222.6  165.43  292.44  163.77  327.36  164.32
  369.27  164.33  376.25  164.18  384.01   163.2   397.2  160.87  405.38  160.08
   412.5  160.39  432.12     164  446.09  167.01  453.08  167.82  474.03  169.56
  494.98  169.75  512.22  171.45   529.9  172.35  550.85  174.68  647.56  178.34
  661.81  178.24  697.43  179.48   718.8  180.83  747.29  183.32  760.38  183.57
  830.22  188.71  865.14  189.97  872.13  190.64  900.06  191.12  961.41  193.51
#Mann= 3 , 0 , 0
       0      .1       0  384.01    .035       0  432.12      .1       0
Bank Sta=384.01,432.12
XS Rating Curve= 0 ,0
Exp/Cntr=0.3,0.1

Type RM Length L Ch R = 1 ,14714   ,189,286.7,185
BEGIN DESCRIPTION:
FEMA R HEC2 23784
END DESCRIPTION:
XS GIS Cut Line= 3
 1648296.2846432  733216.2803907 1648034.4412239  733054.6739002
 1647707.1369498  733046.4912903
#Sta/Elev= 30
       0  168.52   90.58  165.94  101.56  165.26  109.77  165.21  134.38  164.09
     159  163.66  175.41  162.88  200.03  162.84  249.26  161.65   298.5  161.43
   309.2  160.38  316.36  160.24  345.02  161.17  355.75  159.88  358.68  158.35
  362.12  157.64  366.32  157.47  380.27  157.97     386  160.43     388  161.78
  397.66  163.21  411.63  164.32  418.61  164.33  453.54  165.94  502.43  168.89
   516.4  170.14  551.33  175.26  558.31  175.71  579.27  177.98  635.11  181.12
#Mann= 3 , 0 , 0
       0      .1       0  345.02    .035       0     388      .1       0
Bank Sta=345.02,388
XS Rating Curve= 0 ,0
Exp/Cntr=0.3,0.1

Type RM Length L Ch R = 1 ,14427   ,142,158.68,134
XS GIS Cut Line= 2
        1648405.         732949.        1647727.         732838.
#Sta/Elev= 30
       0  168.98   43.97  168.26   68.79  167.25   125.4  165.93  146.62  164.46
  179.37  163.25  203.23  163.26  231.54  161.89  245.69  159.93  273.99  158.34
  289.38  158.33  314.77  159.99   330.6  160.52  344.75  160.61  357.08  159.96
  368.19   158.7  374.34  157.11  380.18  156.12   384.5  156.04  388.82  156.61
   391.2  158.92  394.28  159.84  401.36  161.44  415.51   163.1  492.48  167.68
  521.65  170.43  557.03  172.84  592.41  175.92  606.56  176.27  684.45  181.02
#Mann= 3 , 0 , 0
       0      .1       0  357.08    .035       0  394.28      .1       0
Bank Sta=357.08,394.28
XS Rating Curve= 0 ,0
Exp/Cntr=0.3,0.1

Type RM Length L Ch R = 1 ,14269   ,296.8,335.83,317.63
BEGIN DESCRIPTION:
HEC2 23306
END DESCRIPTION:
XS GIS Cut Line= 2
 1648416.1259369  732762.8831808 1647703.3531306  732756.0296144
#Sta/Elev= 30
       0  169.04   10.75  168.77   17.73  169.24   25.78   169.2   53.99  167.21
  115.49  165.32  136.44   165.6  192.31  162.72  202.06  162.73  216.16  162.03
  265.52  160.82  276.11  159.91  279.62  159.26  290.07  156.99  304.04  155.27
  318.01  156.41  336.02  158.94  345.94  159.85  357.18  160.19  380.85  159.96
  415.77   162.8  434.74  164.86   443.7  165.34   485.6  169.48  499.57  170.44
  520.52  172.74   527.5  172.97  568.71   176.2  646.27  178.09  712.81  182.38
#Mann= 3 , 0 , 0
       0      .1       0  279.62    .035       0  336.02      .1       0
Bank Sta=279.62,336.02
XS Rating Curve= 0 ,0
Exp/Cntr=0.3,0.1

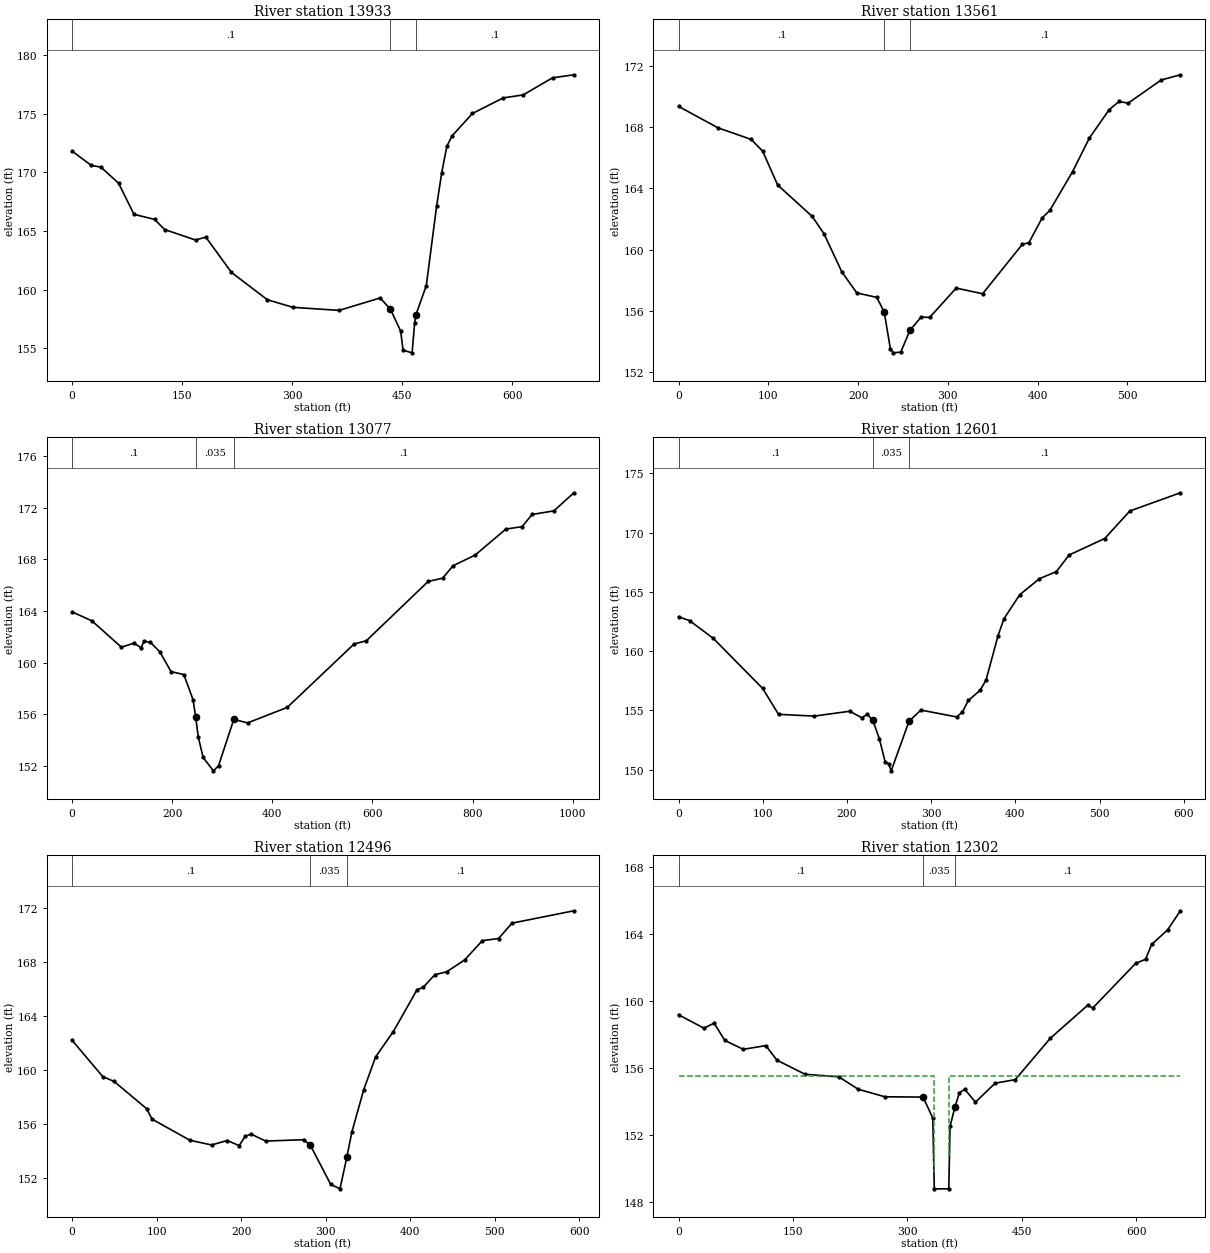
Type RM Length L Ch R = 1 ,13933   ,324.51,371.73,297.44
BEGIN DESCRIPTION:
FEMA Q HEC2 22987
END DESCRIPTION:
XS GIS Cut Line= 2
 1648412.8867678  732464.7079482 1647729.6391209  732495.3927291
#Sta/Elev= 30
       0  171.81   26.05   170.6   39.43  170.44   63.43  169.07    84.4  166.42
  112.36  165.99  126.34  165.12  168.28  164.23  182.26  164.48  217.21  161.47
  266.14  159.14  301.09  158.49     364  158.23  419.92  159.29   433.9  158.33
  447.88  156.46  451.19  154.83  463.45  154.61  466.96  157.19  468.71  157.87
  482.83  160.34  496.81  167.09   503.8  169.96  510.79  172.21  517.78   173.1
  545.74  175.02  587.67  176.35  614.72   176.6  654.86  178.06  683.94  178.32
#Mann= 3 , 0 , 0
       0      .1       0   433.9    .035       0  468.71      .1       0
Bank Sta=433.9,468.71
XS Rating Curve= 0 ,0
Exp/Cntr=0.3,0.1

Type RM Length L Ch R = 1 ,13561   ,519.56,539.64,364.62
BEGIN DESCRIPTION:
FEMA P HEC2 22584
END DESCRIPTION:
XS GIS Cut Line= 2
 1648265.5998623  732086.2624043 1647735.7760723  732264.2340907
#Sta/Elev= 30
       0  169.34   44.07  167.94    80.9  167.19   93.73  166.42  110.36  164.22
  148.87  162.17  161.93  161.05  181.95  158.55  198.49  157.19  220.86  156.89
   229.1  155.94  235.96  153.54  239.28  153.28  247.57  153.33  257.69  154.74
  270.18  155.61  279.79  155.59  309.25   157.5  338.72  157.13  382.92  160.35
  390.28  160.46  405.01  162.07  413.54  162.56  438.93  165.09  457.65  167.28
  479.71  169.13  490.74  169.66  500.78  169.55  537.61  171.06  558.92   171.4
#Mann= 3 , 0 , 0
       0      .1       0   229.1    .035       0  257.69      .1       0
Bank Sta=229.1,257.69
XS Rating Curve= 0 ,0
Exp/Cntr=0.3,0.1

Type RM Length L Ch R = 1 ,13077   ,616.6,1194.05,1125.46
BEGIN DESCRIPTION:
FEMA O HEC2 21991
END DESCRIPTION:
XS GIS Cut Line= 2
      1648008.78       731595.74      1647317.73       732324.84
#Sta/Elev= 30
       0  163.93   39.58  163.24   98.52   161.2  123.55  161.51  138.37  161.15
  143.31  161.66  156.12  161.59  175.32  160.84  197.65  159.31  223.32  159.08
  241.67  157.13  247.05  155.76  251.98  154.28  261.72  152.67  282.37  151.63
  292.54  152.02  323.07  155.61  350.78  155.34  429.81  156.54  563.19  161.44
  587.88   161.7  711.38  166.29  740.26  166.54  760.93   167.5  805.23  168.33
  866.53  170.34  899.09  170.53  918.84  171.47  962.53  171.75 1002.38  173.15
#Mann= 3 , 0 , 0
       0      .1       0  247.05    .035       0  323.07      .1       0
Bank Sta=247.05,323.07
XS Rating Curve= 0 ,0
Exp/Cntr=0.3,0.1

Type RM Length L Ch R = 1 ,12601   ,69.29,105.36,72.4
XS GIS Cut Line= 2
 1647901.6403785  731526.3958971 1647310.8404829  731603.7625322
#Sta/Elev= 30
       0  162.89    13.1  162.57   41.27  161.07   99.96  156.84  118.74  154.66
  160.99  154.51  203.25  154.92  217.33  154.38  224.38  154.65  230.73  154.14
  238.46   152.6   245.5   150.6  249.41   150.5  252.55  149.89  273.67  154.07
  287.76  155.02  330.36  154.44  337.05  154.86   344.1  155.83  358.18  156.69
  365.22  157.57  379.31  161.28  386.35  162.72  405.09  164.75  428.61  166.11
  448.68  166.71  463.82  168.11  506.07   169.5  535.85  171.82  595.84  173.36
#Mann= 3 , 0 , 0
       0      .1       0  230.73    .035       0  273.67      .1       0
Bank Sta=230.73,273.67
XS Rating Curve= 0 ,0
Exp/Cntr=0.3,0.1

Type RM Length L Ch R = 1 ,12496   ,187.09,198.37,196.37
BEGIN DESCRIPTION:
Cross Section '4' for Bridge 12700.
END DESCRIPTION:
XS GIS Cut Line= 2
 1647882.8848341  731467.7847825 1647292.0849148  731524.0514392
#Sta/Elev= 30
       0  162.21    36.3  159.51    49.7  159.15   88.13  157.13   94.54  156.35
  139.37  154.78  164.99  154.43   183.6  154.76  197.63  154.38  204.64  155.07
  211.66  155.24  229.03  154.72  273.86  154.82   281.8  154.41  305.88   151.5
  316.87  151.17   325.1  153.56   330.9  155.39  344.93  158.53  358.96  160.97
     380  162.86  408.06  165.97  415.08  166.13   429.1  167.08  443.13   167.3
  464.18  168.17  485.21  169.61  504.42  169.77  520.29  170.91  593.47  171.83
#Mann= 3 , 0 , 0
       0      .1       0   281.8    .035       0   325.1      .1       0
Bank Sta=281.8,325.1
XS Rating Curve= 0 ,0
Exp/Cntr=0.5,0.3

Type RM Length L Ch R = 1 ,12302   ,35,35,35
BEGIN DESCRIPTION:
XS  '3' for Bridge 12700
END DESCRIPTION:
XS GIS Cut Line= 3
        1647910.        731317.3      1647578.93       731301.87
      1647250.53       731321.98
#Sta/Elev= 30
       0  159.18   33.33  158.38   46.66  158.68   60.65  157.65   84.89  157.12
  114.36  157.34  129.09  156.47  165.92  155.63  210.11  155.48  235.44  154.74
   270.4  154.29   320.6  154.27  333.33  153.02  335.33   148.8  354.31   148.8
  355.94  152.52  362.52   153.7   368.3  154.54   375.3  154.73   389.3  153.97
  415.12   155.1  441.43  155.31  487.46  157.78  536.24  159.74  543.23  159.59
  599.21  162.24  612.39  162.49   620.2  163.37  641.19  164.24  657.87  165.38
#Mann= 3 , 0 , 0
       0      .1       0   320.6    .035       0  362.52      .1       0
#XS Ineff= 2 , 0
       0  334.87   155.5  355.16       0   155.5
Permanent Ineff=
       F       F
Bank Sta=320.6,362.52
XS Rating Curve= 0 ,0
Exp/Cntr=0.5,0.3