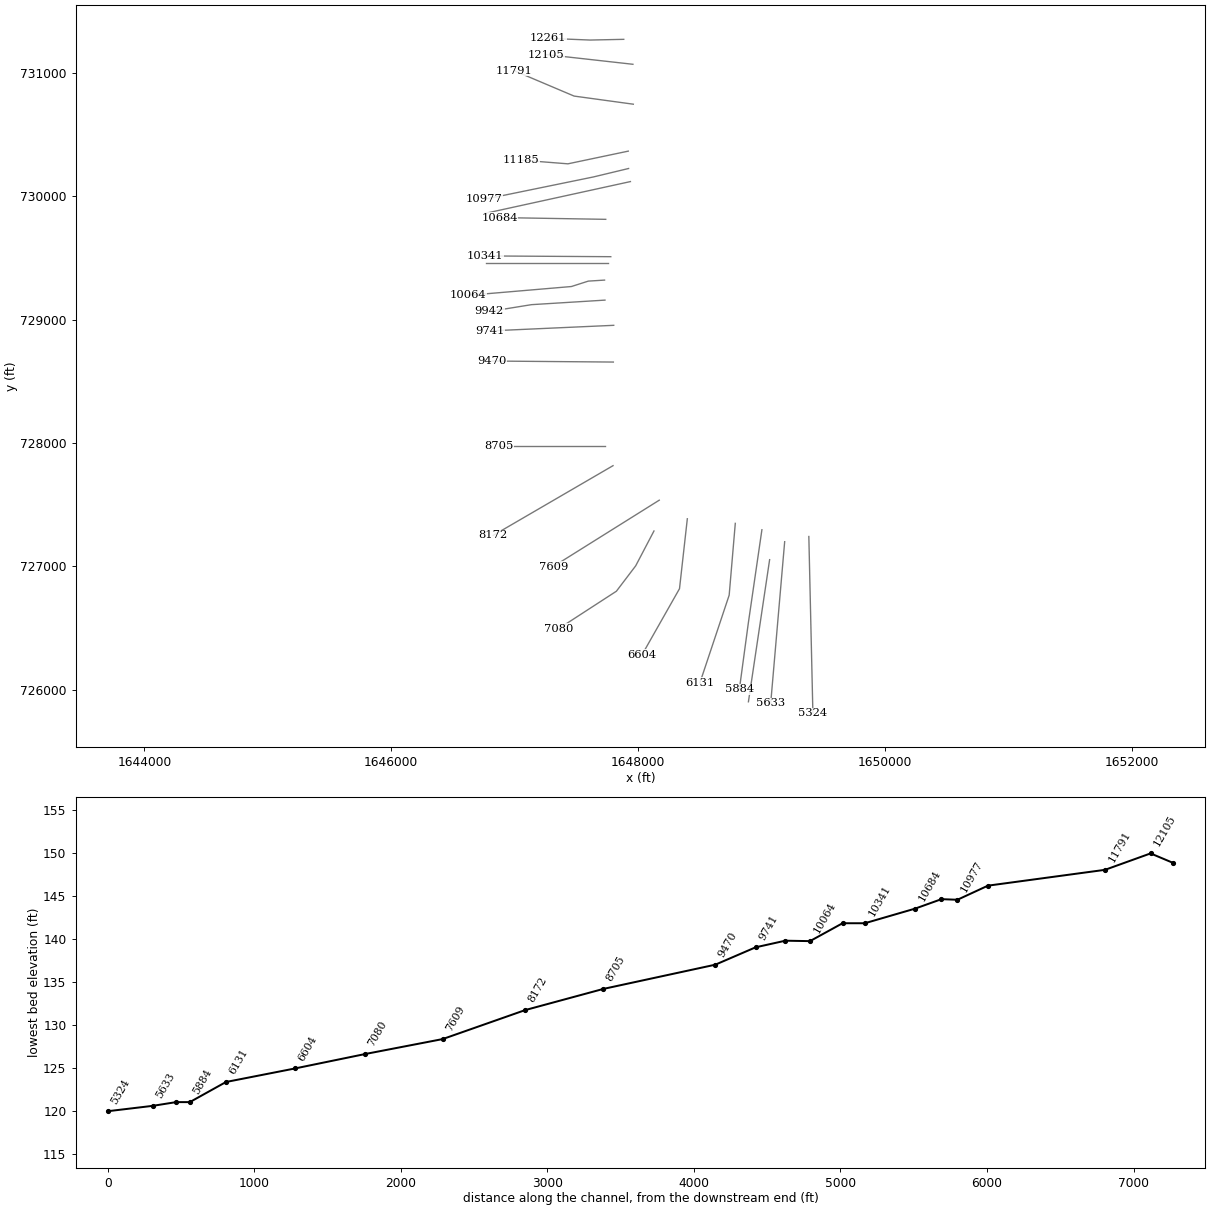
HEC-RAS study WB_Christina.prj: WB_Christina

--- WB_Christina.g13 (geometry) --- (continued)

Type RM Length L Ch R = 3 ,12297   ,,,
BEGIN DESCRIPTION:
Brewster Bridge Road
END DESCRIPTION:
Bridge Culvert--1,0,-1,-1, 0
Deck Dist Width WeirC Skew NumUp NumDn MinLoCord MaxHiCord MaxSubmerge Is_Ogee
5,25,2.6,0, 179, 182, , , 0.95, 0, 0,0,,
       0     1.3    5.69    8.29   12.88   15.27   20.08   22.26   27.27   29.24
   34.47   36.23   41.66   43.21   48.85    50.2   56.05   57.19   63.24   64.17
   70.44   71.16   77.63   78.14   84.83   85.13   92.02   92.11   95.29    99.1
   99.21  106.09  106.41  113.07   113.6  120.06   120.8  127.04  127.99  134.03
  135.19  141.02  142.38     148  149.57  154.99  156.77  161.97  163.96  168.96
  171.16  175.94  178.35  182.93  185.55  189.92  192.74   196.9  199.93  203.89
  207.13  210.87  214.32  217.86  221.52  224.84  228.71  231.83  235.91  238.82
   243.1   245.8  250.29  252.79  257.49  259.77  264.68  266.76  271.88  273.74
  279.07  280.73  286.27  287.72  293.46   294.7  300.65  301.69  307.85  308.67
  315.04  315.66  322.24  322.65     330     330     335     355  363.22  364.59
  369.82  371.59  376.42  378.59  383.02  385.58  389.62  392.58  396.22  399.57
  402.82  406.57  409.42  413.56  416.02  420.56  422.62  427.55  429.22  434.55
  435.83  441.54  442.43  448.54  449.03  455.53  455.63  457.17  462.23  462.53
  468.83  469.52  475.43  476.52  482.03  483.52  488.63  490.51  495.23  497.51
  501.83   504.5  508.43   511.5  515.03  518.49  521.63  525.49  528.23  532.48
  534.83  539.48  541.43  546.47  548.03  553.47  554.63  560.46  561.23  567.46
  567.83  574.09  574.43  574.45  581.03  581.45  587.64  588.45  594.24  595.44
  600.84  602.44  607.44  609.43  614.04  616.43  620.64  623.42  626.73
  159.03  158.95  158.84   158.8   158.7  158.66  158.68  158.61  158.51  158.45
  158.37  158.33   158.1  158.04  158.03  158.02  157.95  157.91  157.74  157.71
  157.63  157.62  157.56  157.54  157.47  157.47  157.19  157.19  157.12  157.03
  157.03  156.94  156.93  156.73  156.73  156.65  156.63   156.7  156.72  156.53
  156.51  156.44  156.44  156.45  156.42  156.24  156.21  156.14  156.09  155.95
     156  156.09  155.98  155.79  155.83  155.79  155.76  155.82  155.67  155.56
  155.61  155.54  155.52  155.54  155.48  155.47  155.46  155.44  155.49  155.41
  155.55  155.58  155.52  155.49  155.45  155.43  155.43  155.48  155.45  155.47
  155.39  155.41  155.56  155.52  155.49   155.5  155.43  155.42  155.22  155.21
  155.32  155.33  155.54  155.54   155.5   155.5   155.5   155.5  155.58  155.62
  155.62  155.64  155.83  155.82  155.94  155.95  155.83  155.87   155.8  155.77
  155.85  155.95   156.1  156.24  156.32   156.4  156.45  156.68  156.76  156.63
  156.64  156.91  156.93  157.24  157.24  157.44  157.44  157.48  157.57  157.58
   157.8  157.83     158  158.03  158.05  158.09  158.21  158.33  158.78   158.9
  159.06  159.13   159.3  159.44  159.47  159.48   159.7  159.86  159.92  160.23
  160.29  160.59  160.68  160.77  160.89  161.18  161.18  161.17  161.18  161.43
  161.42  161.75  161.77  161.77  162.31  162.34   162.5  162.54  162.85  162.92
  163.34  163.46  163.62  163.73  163.94  164.07  164.22  164.43  164.57
                                                                                
                                                                                
                                                                                
                                                                                
                                                                                
                                                                                
                                                                                
                                                                                
                                                                                
                                                   153.5   153.5
                                                                                
                                                                                
                                                                                
                                                                                
                                                                                
                                                                                
                                                                                
                                                                        
       0     1.3    5.69    8.29   12.88   15.27   20.08   22.26   27.27   29.24
   34.47   36.23   41.66   43.21   48.85    50.2   56.05   57.19   63.24   64.17
   70.44   71.16   77.63   78.14   84.83   85.13   92.02   92.11   95.29    99.1
   99.21  106.09  106.41  113.07   113.6  120.06   120.8  127.04  127.99  134.03
  135.19  141.02  142.38     148  149.57  154.99  156.77  161.97  163.96  168.96
  171.16  175.94  178.35  182.93  185.55  189.92  192.74   196.9  199.93  203.89
  207.13  210.87  214.32  217.86  221.52  224.84  228.71  231.83  235.91  238.82
   243.1   245.8  250.29  252.79  257.49  259.77  264.68  266.76  271.88  273.74
  279.07  280.73  286.27  287.72  293.46   294.7     311     311     331     331
   336.3  336.62  336.63  338.96  340.25  343.42  343.61  350.02   350.6  356.62
   357.6  363.22  364.59  369.82  371.59  376.42  378.59  383.02  385.58  389.62
  392.58  396.22  399.57  402.82  406.57  409.42  413.56  416.02  420.56  422.62
  427.55  429.22  434.55  435.83  441.54  442.43  448.54  449.03  455.53  455.63
  457.17  462.23  462.53  468.83  469.52  475.43  476.52  482.03  483.52  488.63
  490.51  495.23  497.51  501.83   504.5  508.43   511.5  515.03  518.49  521.63
  525.49  528.23  532.48  534.83  539.48  541.43  546.47  548.03  553.47  554.63
  560.46  561.23  567.46  567.83  574.09  574.43  574.45  581.03  581.45  587.64
  588.45  594.24  595.44  600.84  602.44  607.44  609.43  614.04  616.43  620.64
  623.42  626.73
  159.03  158.95  158.84   158.8   158.7  158.66  158.68  158.61  158.51  158.45
  158.37  158.33   158.1  158.04  158.03  158.02  157.95  157.91  157.74  157.71
  157.63  157.62  157.56  157.54  157.47  157.47  157.19  157.19  157.12  157.03
  157.03  156.94  156.93  156.73  156.73  156.65  156.63   156.7  156.72  156.53
  156.51  156.44  156.44  156.45  156.42  156.24  156.21  156.14  156.09  155.95
     156  156.09  155.98  155.79  155.83  155.79  155.76  155.82  155.67  155.56
  155.61  155.54  155.52  155.54  155.48  155.47  155.46  155.44  155.49  155.41
  155.55  155.58  155.52  155.49  155.45  155.43  155.43  155.48  155.45  155.47
  155.39  155.41  155.56  155.52  155.49   155.5   155.5   155.5   155.5   155.5
  155.54  155.52  155.53   155.5   155.5  155.47  155.47  155.47  155.47  155.44
  155.45  155.58  155.62  155.62  155.64  155.83  155.82  155.94  155.95  155.83
  155.87   155.8  155.77  155.85  155.95   156.1  156.24  156.32   156.4  156.45
  156.68  156.76  156.63  156.64  156.91  156.93  157.24  157.24  157.44  157.44
  157.48  157.57  157.58   157.8  157.83     158  158.03  158.05  158.09  158.21
  158.33  158.78   158.9  159.06  159.13   159.3  159.44  159.47  159.48   159.7
  159.86  159.92  160.23  160.29  160.59  160.68  160.77  160.89  161.18  161.18
  161.17  161.18  161.43  161.42  161.75  161.77  161.77  162.31  162.34   162.5
  162.54  162.85  162.92  163.34  163.46  163.62  163.73  163.94  164.07  164.22
  164.43  164.57
                                                                                
                                                                                
                                                                                
                                                                                
                                                                                
                                                                                
                                                                                
                                                                                
                                                           153.5   153.5
                                                                                
                                                                                
                                                                                
                                                                                
                                                                                
                                                                                
                                                                                
                                                                                
                                                                                
                
BR Coef=-1 , 0 , 0 ,, 0 ,,,0.8,0,,1,
WSPro=,,,, 1 ,,,, 0 ,,,, 0 ,,,,-1 ,-1 ,-1 , 0 , 0 , 0 , 0 , 0
BC Design=,, 0 ,, 0 ,,,,,,
BC Use User HTab Curves=0
BC User HTab FreeFlow(D)= 0

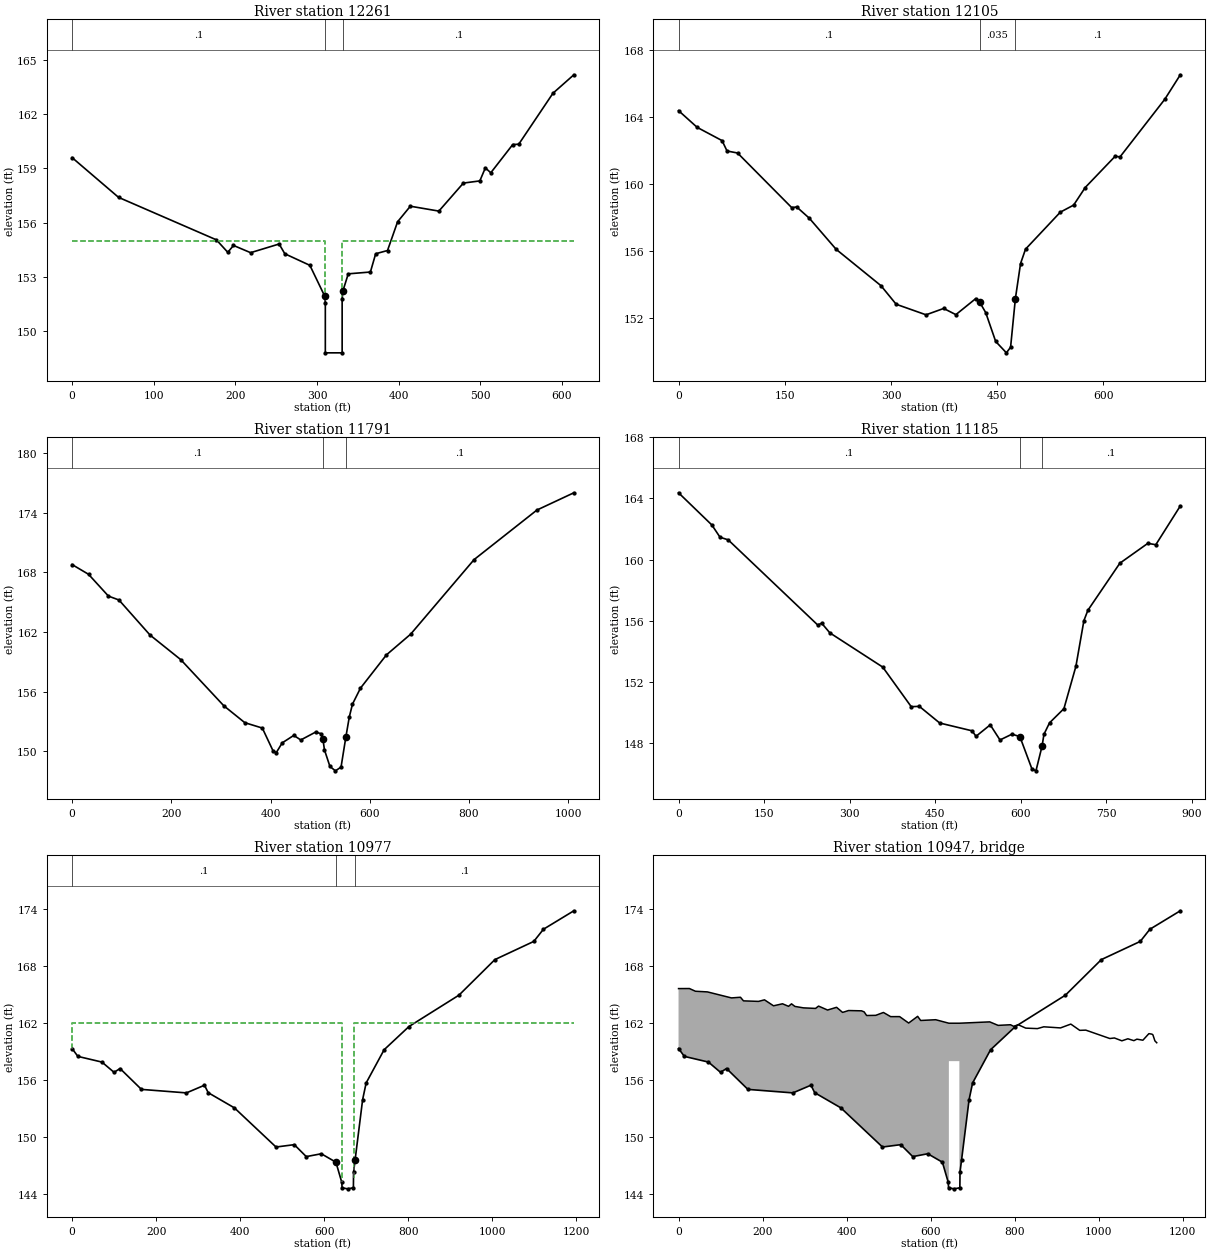
Type RM Length L Ch R = 1 ,12261   ,154.16,156,162.74
BEGIN DESCRIPTION:
HEC2 21203. XS '2' for Bridge 12700.
END DESCRIPTION:
XS GIS Cut Line= 3
  1647883.827242  731271.6828609 1647610.8188265  731265.8987747
 1647269.5583369  731279.7805578
#Sta/Elev= 30
       0   159.6   56.94   157.4  176.77  155.05  190.74  154.36  197.72  154.74
  218.68  154.34   253.6  154.82  260.58  154.28  291.27  153.64   309.5  151.93
  310.19  151.56  310.19   148.8  330.79   148.8  330.79  151.78  331.56   152.2
  338.28  153.17  365.41  153.27  371.86  154.28  386.37  154.46  398.72  156.05
  414.33  156.91  449.27  156.64   479.3  158.19  499.45  158.31  506.17  159.03
  512.88  158.76  539.74  160.32  547.11  160.34  589.04  163.16  614.61  164.18
#Mann= 3 , 0 , 0
       0      .1       0   309.5    .035       0  331.56      .1       0
#XS Ineff= 2 , 0
       0     310     155     331       0     155
Permanent Ineff=
       F       F
Bank Sta=309.5,331.56
XS Rating Curve= 0 ,0
Exp/Cntr=0.5,0.3

Type RM Length L Ch R = 1 ,12105   ,294,311,317
BEGIN DESCRIPTION:
Additional Cross Section at location of fully expanded flow downstream of Bridge 12700. XS '1'.
END DESCRIPTION:
XS GIS Cut Line= 2
      1647958.14       731069.48      1647252.39       731148.52
#Sta/Elev= 30
       0  164.38   26.34  163.38   61.47  162.59   68.49  161.97   83.36  161.85
  159.82  158.59  166.84  158.63  184.61  157.96  222.57   156.1  285.85  153.93
  307.35  152.82   349.5  152.19  374.44  152.57  391.65   152.2  419.75  153.16
  425.06  152.96   433.8  152.32  447.85   150.6  463.02  149.92  468.92  150.26
  475.68  153.16  482.97  155.25     490  156.11  539.18  158.32  557.94  158.74
   574.3  159.79  616.45  161.65  623.48  161.62   686.7  165.06   708.6  166.52
#Mann= 3 , 0 , 0
       0      .1       0  425.06    .035       0  475.68      .1       0
Bank Sta=425.06,475.68
XS Rating Curve= 0 ,0
Exp/Cntr=0.3,0.1

Type RM Length L Ch R = 1 ,11791   ,714.29,798.65,783.91
BEGIN DESCRIPTION:
HEC2 20671
END DESCRIPTION:
XS GIS Cut Line= 3
  1647961.333854  730746.0603017 1647481.4697533  730811.8702193
 1646996.1214829  731017.5262625
#Sta/Elev= 30
       0  168.79   33.17  167.81   73.36  165.61   94.51  165.22  157.14  161.69
  219.12  159.21  305.96  154.56  348.24  152.86  383.49  152.32  405.06  150.03
  411.68  149.85  423.66  150.83  446.92  151.58  461.02  151.12  490.79  151.91
  501.44  151.76  505.69  151.19  508.71  150.13  519.79  148.45  530.88  148.01
  542.21  148.39  551.78  151.38  558.84  153.44  565.23  154.73  581.34  156.34
  633.67  159.69  682.55  161.78  810.39  169.29  937.02  174.28 1011.48  176.02
#Mann= 3 , 0 , 0
       0      .1       0  505.69    .035       0  551.78      .1       0
Bank Sta=505.69,551.78
XS Rating Curve= 0 ,0
Exp/Cntr=0.3,0.1

Type RM Length L Ch R = 1 ,11185   ,165.72,208.19,200.5
BEGIN DESCRIPTION:
Cross Section '4' for Bridge 11350.
END DESCRIPTION:
XS GIS Cut Line= 3
       1647920.5       730365.77      1647431.18       730262.89
      1647049.76         730293.
#Sta/Elev= 30
       0  164.37   58.49  162.26   72.75  161.46   87.02  161.29   243.9  155.72
  251.03  155.83   265.3   155.2     358  152.96  407.92  150.37  422.18  150.39
  457.84   149.3  514.53  148.79  521.53  148.43  546.45  149.18  563.56  148.19
  584.57  148.57  598.41  148.41  619.59  146.29   626.6  146.17  637.38   147.8
   640.6  148.56  650.37  149.31  675.63  150.24  696.64  153.01  710.65     156
  717.65  156.68  773.69  159.76  822.72  161.06  836.72  160.97   879.7  163.51
#Mann= 3 , 0 , 0
       0      .1       0  598.41    .035       0  637.38      .1       0
Bank Sta=598.41,637.38
XS Rating Curve= 0 ,0
Exp/Cntr=0.5,0.3

Type RM Length L Ch R = 1 ,10977   ,110,109,107
BEGIN DESCRIPTION:
HEC2 19842. XS '3'.
END DESCRIPTION:
XS GIS Cut Line= 3
 1647922.9447374  730225.0649876 1647637.7683404  730156.5129732
 1646754.8183961  729975.5356581
#Sta/Elev= 30
       0  159.33   13.86   158.5   71.18   157.9   99.91  156.82  114.27  157.22
  165.13  155.02  272.27  154.65   315.2  155.46  324.17  154.67  386.48  153.07
  485.55  148.94  529.04  149.19  557.55  147.93  593.37  148.23  628.15  147.34
   642.2   145.2   642.8  144.64  655.87  144.53  669.75  144.64  670.15  146.31
  673.83  147.58  691.76  153.95  700.11   155.7  742.88   159.2  802.03  161.65
  921.08  164.96 1006.61  168.71 1099.28  170.63 1122.12  171.91 1194.61  173.86
#Mann= 3 , 0 , 0
       0      .1       0  628.15    .035       0  673.83      .1       0
#XS Ineff= 2 , 0
       0     642     162     670       0     162
Permanent Ineff=
       F       F
Bank Sta=628.15,673.83
XS Rating Curve= 0 ,0
Exp/Cntr=0.5,0.3

Type RM Length L Ch R = 3 ,10947   ,,,
BEGIN DESCRIPTION:
CSX Railroad Bridge. Bridge data taken from supplied bridge database. Top of embankment profile extracted from DEM.
END DESCRIPTION:
Bridge Culvert--1,0,-1,-1, 0
Deck Dist Width WeirC Skew NumUp NumDn MinLoCord MaxHiCord MaxSubmerge Is_Ogee
40,33,2.6,0, 60, 60, 162.2, , 0.95, 0, 0,0,,
       0  25.901    40.2  68.798 125.995 147.444 154.594 190.342 204.641  226.09
 247.539 261.838 268.988     277 297.586 326.185 333.334 354.783 376.232 390.531
  404.83 435.673 441.961 447.728 469.454 487.783 504.925 526.374 547.823 569.271
 576.421 612.169  643.58  643.58  668.58  668.58 740.862 760.865 790.212 798.059
 808.541 826.657 854.364 869.555 909.351 933.902 955.173  969.651026.8471037.654
1055.4451069.7441084.0431091.1931105.4921119.7921126.9411129.2991134.0911138.463
 165.654 165.659 165.373 165.304  164.67 164.739 164.359 164.302 164.467 163.837
  164.05 163.782 164.045 163.773 163.619 163.561 163.807 163.391 163.679 163.141
 163.338 163.307 163.193 162.813  162.83 163.134 162.695 162.696 162.019 162.726
 162.288  162.37     162     162     162     162 162.142 161.772  161.84  161.67
 161.842 161.482 161.431 161.622 161.504 161.908 161.247  161.27 160.385 160.445
 160.143 160.358 160.161 160.319 160.207   160.9 160.849 160.778 160.136 159.939
                                                                                
                                                                                
                                                                                
                             158     158
                                                                                
                                                                                
      25    40.2  68.798 125.995 147.444 154.594 190.342 204.641  226.09 247.539
 261.838 268.988     277 297.586 326.185 333.334 354.783 376.232 390.531  404.83
 435.673 441.961 447.728 469.454 487.783 504.925 526.374 547.823 569.271 576.421
 612.169  643.58     665     665     690     690 740.862 760.865 790.212 798.059
 808.541 826.657 854.364 869.555 909.351 933.902 955.173  969.651026.8471037.654
1055.4451069.7441084.0431091.1931105.4921119.7921126.9411129.2991134.0911138.463
 165.654 165.373 165.304  164.67 164.739 164.359 164.302 164.467 163.837  164.05
 163.782 164.045 163.773 163.619 163.561 163.807 163.391 163.679 163.141 163.338
 163.307 163.193 162.813  162.83 163.134 162.695 162.696 162.019 162.726 162.288
  162.37     162     162     162     162     162 162.142 161.772  161.84  161.67
 161.842 161.482 161.431 161.622 161.504 161.908 161.247  161.27 160.385 160.445
 160.143 160.358 160.161 160.319 160.207   160.9 160.849 160.778 160.136 159.939
                                                                                
                                                                                
                                                                                
                             158     158
                                                                                
                                                                                
BR Coef=-1 , 0 , 0 ,, 0 ,,,0.8,0,,1,
WSPro=,,,, 1 ,,,, 0 ,,,, 0 ,,,,-1 ,-1 ,-1 , 0 , 0 , 0 , 0 , 0
BC Design=,, 0 ,, 0 ,,,,,,
BC Use User HTab Curves=0
BC User HTab FreeFlow(D)= 0

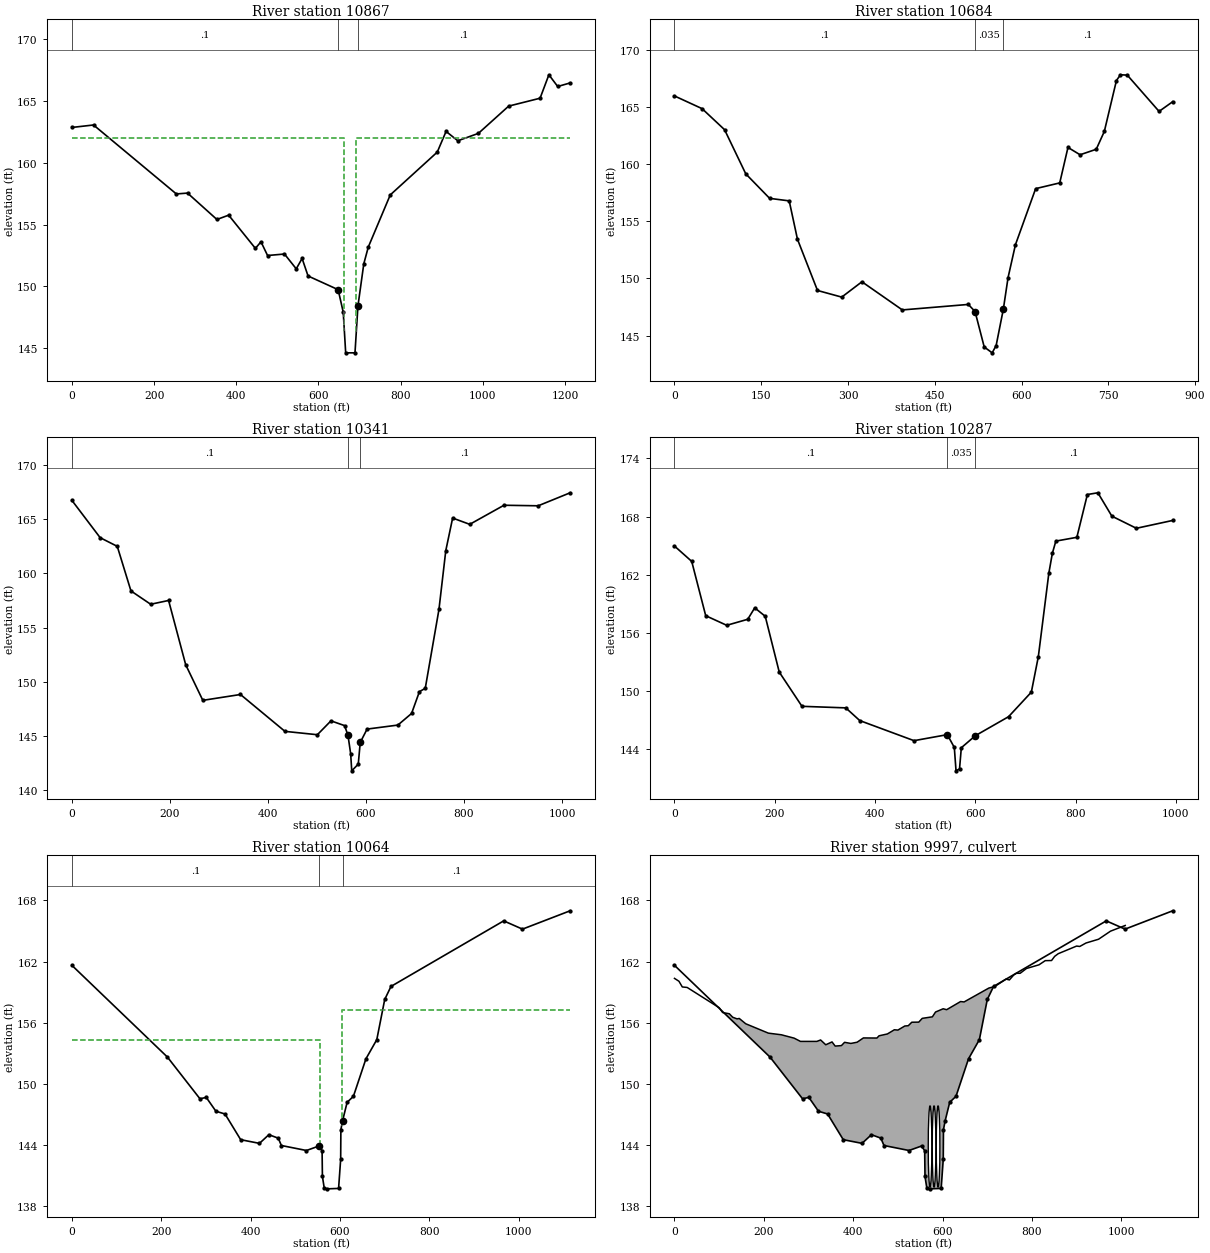
Type RM Length L Ch R = 1 ,10867   ,172.48,179.86,138.36
BEGIN DESCRIPTION:
XS '2' for Bridge 11350
END DESCRIPTION:
XS GIS Cut Line= 2
      1647937.85       730119.06      1646751.17       729859.33
#Sta/Elev= 30
       0  162.87   52.64  163.07  254.17  157.48   281.4  157.55  352.89  155.41
  381.48  155.76  446.47  153.07  460.12   153.6  476.12  152.49  517.31  152.61
  545.91  151.41   560.2  152.25  574.67  150.83  647.93  149.72  660.29  147.89
  666.24   144.6  688.88   144.6  696.03  148.39  710.33  151.82  721.18  153.17
  774.67   157.4  889.05  160.87   910.5  162.55  939.09  161.79  989.13  162.39
 1062.84   164.6 1139.26  165.24  1160.7  167.14 1182.15  166.19 1212.45  166.48
#Mann= 3 , 0 , 0
       0      .1       0  647.93    .035       0  696.03      .1       0
#XS Ineff= 2 , 0
       0     663     162     692       0     162
Permanent Ineff=
       F       F
Bank Sta=647.93,696.03
XS Rating Curve= 0 ,0
Exp/Cntr=0.5,0.3

Type RM Length L Ch R = 1 ,10684   ,306.87,343.12,314.36
BEGIN DESCRIPTION:
FEMA L HEC2 19573. Cross Section'1'
END DESCRIPTION:
XS GIS Cut Line= 2
 1647737.8217307  729813.1342225 1646876.6023499  729827.4537838
#Sta/Elev= 30
       0  165.95   47.72  164.84    86.6     163  123.28  159.14   164.5     157
  198.34  156.78  212.59  153.43  247.23  148.95  289.13  148.37  324.05  149.71
  393.89  147.25  507.98  147.73   519.6  147.11  535.46  144.01   549.2   143.5
  556.07  144.14  568.48  147.31  576.68  150.08  589.43  152.95  624.35  157.85
  665.98  158.35  680.22  161.45  701.18  160.81  729.11  161.29  743.08  162.85
  764.03   167.3  771.01   167.8  782.76  167.77  837.72   164.6  861.34  165.45
#Mann= 3 , 0 , 0
       0      .1       0   519.6    .035       0  568.48      .1       0
Bank Sta=519.6,568.48
XS Rating Curve= 0 ,0
Exp/Cntr=0.3,0.1

Type RM Length L Ch R = 1 ,10341   ,148.61,151.85,150.08
BEGIN DESCRIPTION:
FEMA K   HEC2 19223
END DESCRIPTION:
XS GIS Cut Line= 2
 1647778.7347561  729510.3777779 1646762.0458599  729516.5147294
#Sta/Elev= 30
       0  166.74   57.67   163.3   92.59   162.5  120.52  158.39  160.77  157.16
  197.33  157.51  232.25  151.58  267.16   148.3  343.98  148.84  434.75  145.44
  500.89  145.13  528.65  146.41  556.41  145.97  563.35  145.08  568.86  143.37
  571.03   141.8  584.35  142.42  588.38  144.42  602.35  145.65  665.19  146.02
  693.12  147.09  709.12   149.1  721.06  149.41  748.99  156.68  762.95  162.11
  776.92  165.11  811.83  164.53  881.66  166.29  951.49  166.24 1016.71  167.44
#Mann= 3 , 0 , 0
       0      .1       0  563.35    .035       0  588.38      .1       0
Bank Sta=563.35,588.38
XS Rating Curve= 0 ,0
Exp/Cntr=0.3,0.1

Type RM Length L Ch R = 1 ,10287   ,224.18,222.28,221.34
BEGIN DESCRIPTION:
XS '4' for Bridge 10400
END DESCRIPTION:
XS GIS Cut Line= 2
       1647759.9       729457.39      1646768.72       729457.39
#Sta/Elev= 30
       0  164.97   34.37  163.39    62.3  157.79   104.2   156.8  146.09  157.42
  160.06   158.6  181.01  157.73  208.94  151.98  254.27  148.45  341.61  148.29
  369.54  146.98  477.72  144.91  544.12  145.53  558.08  144.21  561.51   141.8
  568.49     142  572.05  144.18  599.98  145.42  666.25  147.38   711.7  149.91
  725.67  153.58  746.62  162.18   753.6  164.22  760.58  165.48  802.48  165.87
  823.43  170.28  844.38  170.46  872.31  168.05  921.19   166.8  993.69  167.61
#Mann= 3 , 0 , 0
       0      .1       0  544.12    .035       0  599.98      .1       0
Bank Sta=544.12,599.98
XS Rating Curve= 0 ,0
Exp/Cntr=0.5,0.3

Type RM Length L Ch R = 1 ,10064   ,213,168,170
BEGIN DESCRIPTION:
HEC2 18936 XS '3' for Bridge 10400
END DESCRIPTION:
XS GIS Cut Line= 4
 1647728.2570099   729320.726817  1647596.637127  729312.5005743
 1647459.5330983  729268.6272642  1646623.198537  729197.3331769
#Sta/Elev= 30
       0  161.64  213.85  152.64  286.67  148.55  300.69  148.69  322.34  147.33
  342.74  147.06  377.78  144.54  419.83  144.18  440.85  145.03  461.88  144.69
  468.88  143.97  524.95  143.48  552.98  143.92  559.99  143.46  560.69  140.94
  564.93  139.76   571.8  139.72  596.91  139.76  601.57  142.62  602.04  145.53
  605.81  146.39  616.05  148.21  630.07  148.79   658.1  152.47  682.42  154.35
  700.15  158.29  714.17  159.57  966.46     166 1008.51  165.19  1115.2  166.99
#Mann= 3 , 0 , 0
       0      .1       0  552.98    .035       0  605.81      .1       0
#XS Ineff= 2 , 0
       0  555.22  154.27  603.44       0   157.3
Permanent Ineff=
       F       F
Bank Sta=552.98,605.81
XS Rating Curve= 0 ,0
Exp/Cntr=0.5,0.3

Type RM Length L Ch R = 2 ,9997    ,,,
BEGIN DESCRIPTION:
Gore Inc Driveway Culvert. No data in bridge/culvert inventory. Used  invert, length and diameter data from HEC2 model.
END DESCRIPTION:
Bridge Culvert--1,0,-1,-1, 0
Deck Dist Width WeirC Skew NumUp NumDn MinLoCord MaxHiCord MaxSubmerge Is_Ogee
50,50,2.6,0, 60, 60, , , 0.95, 0, 0,0,,
       0    9.97   17.49   28.43  100.22  107.74  122.78   130.3     140  144.97
  159.46  210.19  239.18   267.8  281.96  318.61   327.1  338.59  352.65  359.67
   373.7  380.72  394.76  408.79  422.83  453.09  457.92   476.5  492.11  500.03
  515.52  523.32  531.13  546.73  554.54  577.23  584.25  601.36  609.16  640.37
  648.18  703.55  717.59  741.82  749.62   759.7  765.23  773.73  787.77  815.84
  829.88  843.92  850.93  858.87  900.06  907.08  921.11  949.19  975.92 1008.82
  160.36  160.08  159.52  159.47  157.48  157.01  156.89  156.55  156.39  156.43
  155.91  154.99  154.83   154.5  154.18  154.18  154.32  153.85  154.13  153.72
  153.77  154.09  153.98   154.1  154.52  154.51  154.73  154.91  155.32  155.29
  155.69  155.72  156.06  156.07  156.44  156.59  157.06  157.38  157.29  158.09
  158.05  159.41  159.58  160.29  160.21  160.71  160.86  160.86  161.33  161.69
   162.1  162.11  162.52  162.78  163.53  163.49  163.83   164.2  164.99  165.55
                                                                                
                                                                                
                                                                                
                                                                                
                                                                                
                                                                                
       0    9.97   17.49   28.43  100.22  107.74  122.78   130.3     140  144.97
  159.46  210.19  239.18   267.8  281.96  318.61   327.1  338.59  352.65  359.67
   373.7  380.72  394.76  408.79  422.83  453.09  457.92   476.5  492.11  500.03
  515.52  523.32  531.13  546.73  554.54  577.23  584.25  601.36  609.16  640.37
  648.18  703.55  717.59  741.82  749.62   759.7  765.23  773.73  787.77  815.84
  829.88  843.92  850.93  858.87  900.06  907.08  921.11  949.19  975.92 1008.82
  160.36  160.08  159.52  159.47  157.48  157.01  156.89  156.55  156.39  156.43
  155.91  154.99  154.83   154.5  154.18  154.18  154.32  153.85  154.13  153.72
  153.77  154.09  153.98   154.1  154.52  154.51  154.73  154.91  155.32  155.29
  155.69  155.72  156.06  156.07  156.44  156.59  157.06  157.38  157.29  158.09
  158.05  159.41  159.58  160.29  160.21  160.71  160.86  160.86  161.33  161.69
   162.1  162.11  162.52  162.78  163.53  163.49  163.83   164.2  164.99  165.55
                                                                                
                                                                                
                                                                                
                                                                                
                                                                                
                                                                                
BR Coef=-1 , 0 , 0 ,, 0 ,,,0.8,0,,1,
WSPro=,,,, 1 ,,,, 0 ,,,, 0 ,,,,-1 ,-1 ,-1 , 0 , 0 , 0 , 0 , 0
Multiple Barrel Culv=1,8,,78,0.013,0.5,1,1,1,139.87,139.77, 3,Culvert #1  , 0 ,35
     572     565     581     574     590     583
Culvert Bottom n=0.013
BC Design=,, 0 ,, 0 ,,,,,,
BC Use User HTab Curves=0
BC User HTab FreeFlow(D)= 0

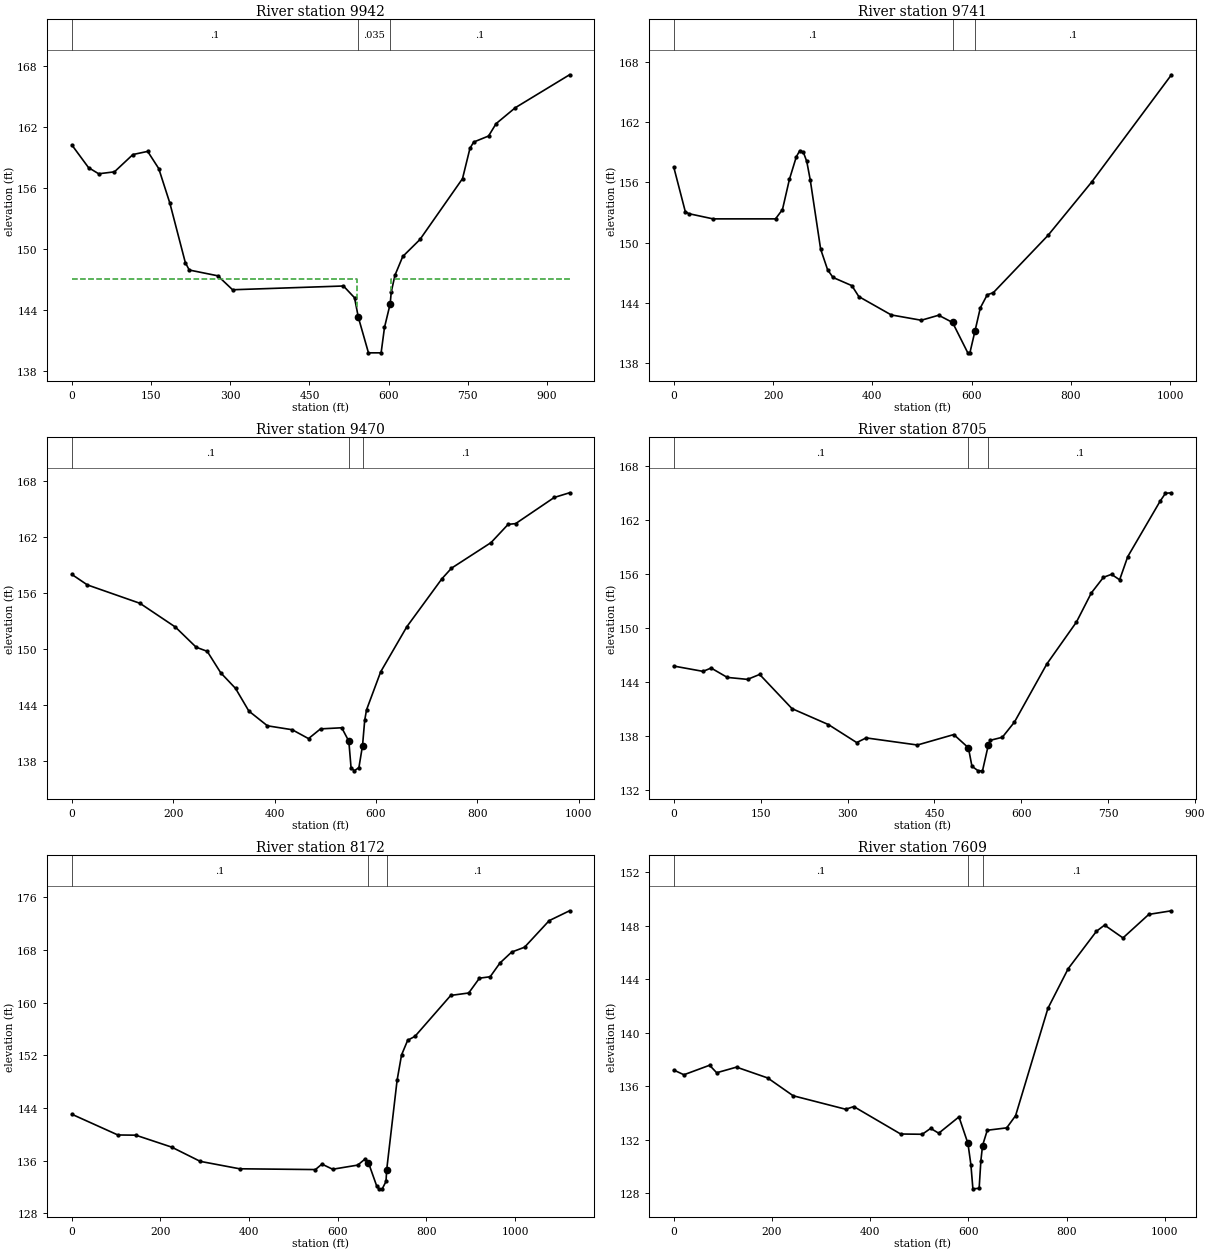
Type RM Length L Ch R = 1 ,9942    ,217,203,199
BEGIN DESCRIPTION:
FEMA J HEC2 18823
END DESCRIPTION:
XS GIS Cut Line= 3
 1647731.6847556  729158.5256981 1647136.4001345  729121.7039658
 1646794.7762992  729066.4713555
#Sta/Elev= 30
       0   160.2   31.63  157.97   50.81  157.37   80.64  157.56  115.59  159.26
  143.57  159.57  164.56  157.88  185.55  154.49  214.87  148.64  222.33  147.91
   276.5  147.34  304.36  145.97  514.37  146.34  535.36  145.18  542.54  143.26
  561.71  139.77  585.68  139.77  592.07  142.27  602.85  144.59  604.85  145.75
  611.92   147.4  626.64  149.24  659.22  150.91  739.81  156.89  753.96  159.88
  761.04  160.49  789.11  161.08  803.48   162.3  839.73  163.86  942.48   167.1
#Mann= 3 , 0 , 0
       0      .1       0  542.54    .035       0  602.85      .1       0
#XS Ineff= 2 , 0
       0     540     147     605       0     147
Permanent Ineff=
       F       F
Bank Sta=542.54,602.85
XS Rating Curve= 0 ,0
Exp/Cntr=0.5,0.3

Type RM Length L Ch R = 1 ,9741    ,269,275,275
BEGIN DESCRIPTION:
XS '1' for Bridge 10400
END DESCRIPTION:
XS GIS Cut Line= 2
      1647802.56       728954.27      1646798.83        728909.1
#Sta/Elev= 30
       0  157.51   23.15  153.09   30.15  152.88   79.08  152.36  204.91  152.36
   218.9  153.29  232.88   156.3  246.86  158.56  253.85  159.17  260.84  159.02
  267.83  158.09  274.82  156.25  295.79  149.34  309.78  147.29  320.59  146.52
  358.71   145.7  372.69  144.61  438.03  142.78  498.53  142.25  533.48  142.75
  561.44  142.03  592.18     139   596.4     139  606.86  141.22  617.37  143.48
  631.35  144.79  643.56     145  753.66  150.71  841.75  156.04 1002.36  166.73
#Mann= 3 , 0 , 0
       0      .1       0  561.44    .035       0  606.86      .1       0
Bank Sta=561.44,606.86
XS Rating Curve= 0 ,0
Exp/Cntr=0.3,0.1

Type RM Length L Ch R = 1 ,9470    ,682.4,764.62,690.37
BEGIN DESCRIPTION:
HEC2 18290 Intermdiate DS XS for Br 10400
END DESCRIPTION:
XS GIS Cut Line= 2
 1647799.5510972  728656.5948994 1646817.8862645   728664.821142
#Sta/Elev= 30
       0     158   30.56  156.88  134.36  154.91  204.19  152.37  245.23  150.21
  267.04  149.77  293.71  147.47   322.9   145.8  349.11  143.38  385.75   141.8
  434.63  141.38  466.83  140.43  490.49  141.47  532.39  141.59  546.36  140.15
  550.72  137.33  557.08  136.98  566.23  137.33   573.4  139.69  577.64  142.38
  581.27  143.51  609.21  147.58  660.74   152.4  729.99  157.54  748.87  158.67
  826.94  161.41   860.6  163.36  875.41  163.44  951.59  166.24   981.7  166.74
#Mann= 3 , 0 , 0
       0      .1       0  546.36    .035       0   573.4      .1       0
Bank Sta=546.36,573.4
XS Rating Curve= 0 ,0
Exp/Cntr=0.3,0.1

Type RM Length L Ch R = 1 ,8705    ,442.59,532.91,530.99
BEGIN DESCRIPTION:
FEMA I HEC2 17523
END DESCRIPTION:
XS GIS Cut Line= 2
 1647729.6391209  727978.1846768 1646870.4653985  727978.1846768
#Sta/Elev= 30
       0   145.8   50.47  145.21   64.44  145.58   92.37  144.54  127.29  144.32
  148.23  144.87   204.1  141.07  266.94   139.3  315.82   137.3  332.06  137.82
  420.57  137.03  483.41  138.19  508.65  136.72  514.73  134.67  525.55  134.16
  532.95  134.16  543.01  137.02  546.26  137.55   567.2  137.89  588.15  139.58
  644.02  146.03  695.17  150.69  720.83  153.92  741.78  155.66  755.74  155.99
  769.71  155.38  783.67  157.95  839.54  164.11  848.79  164.99  859.17  165.05
#Mann= 3 , 0 , 0
       0      .1       0  508.65    .035       0  543.01      .1       0
Bank Sta=508.65,543.01
XS Rating Curve= 0 ,0
Exp/Cntr=0.3,0.1

Type RM Length L Ch R = 1 ,8172    ,489.67,562.84,501.48
BEGIN DESCRIPTION:
HEC2 16933
END DESCRIPTION:
XS GIS Cut Line= 2
 1647796.8090242  727816.9698125 1646826.1124834  727252.1012121
#Sta/Elev= 30
       0  143.04   103.8  139.89  144.19  139.86  224.98  138.05  289.62  135.88
  378.49  134.75   549.6  134.63  564.31  135.46  588.54  134.68   645.1  135.31
  660.67  136.18  669.33  135.67  688.09   132.1  693.09   131.7  700.43   131.7
  708.96  132.83  710.43  134.57  733.97  148.21  743.97  152.05  757.85  154.29
  774.36  154.89  855.04  161.11  895.55  161.48  919.79  163.73  944.02  163.95
  966.11  166.04   992.5   167.7 1021.64  168.44 1077.17  172.48 1123.09  173.98
#Mann= 3 , 0 , 0
       0      .1       0  669.33    .035       0  710.43      .1       0
Bank Sta=669.33,710.43
XS Rating Curve= 0 ,0
Exp/Cntr=0.3,0.1

Type RM Length L Ch R = 1 ,7609    ,354.05,529.22,423.59
BEGIN DESCRIPTION:
FEMA H HEC2 16317
END DESCRIPTION:
XS GIS Cut Line= 2
  1648171.499885  727537.3467182 1647312.3261625  726999.3403421
#Sta/Elev= 30
       0  137.21   20.65  136.86   72.92  137.57   87.37  137.01  127.76  137.43
  191.34  136.62   243.1  135.29  350.21  134.28  366.68  134.48  462.06  132.43
  506.14  132.41  523.22  132.85   539.7  132.49   580.9  133.71  599.21  131.72
  605.22  130.13  609.28  128.33  622.01  128.37  625.52  130.43  628.96  131.57
  638.57  132.71  678.15  132.89  696.24   133.8  762.15  141.83  803.35  144.79
  861.02  147.59   877.5  148.05  914.98  147.09  967.61  148.85 1013.72  149.12
#Mann= 3 , 0 , 0
       0      .1       0  599.21    .035       0  628.96      .1       0
Bank Sta=599.21,628.96
XS Rating Curve= 0 ,0
Exp/Cntr=0.3,0.1

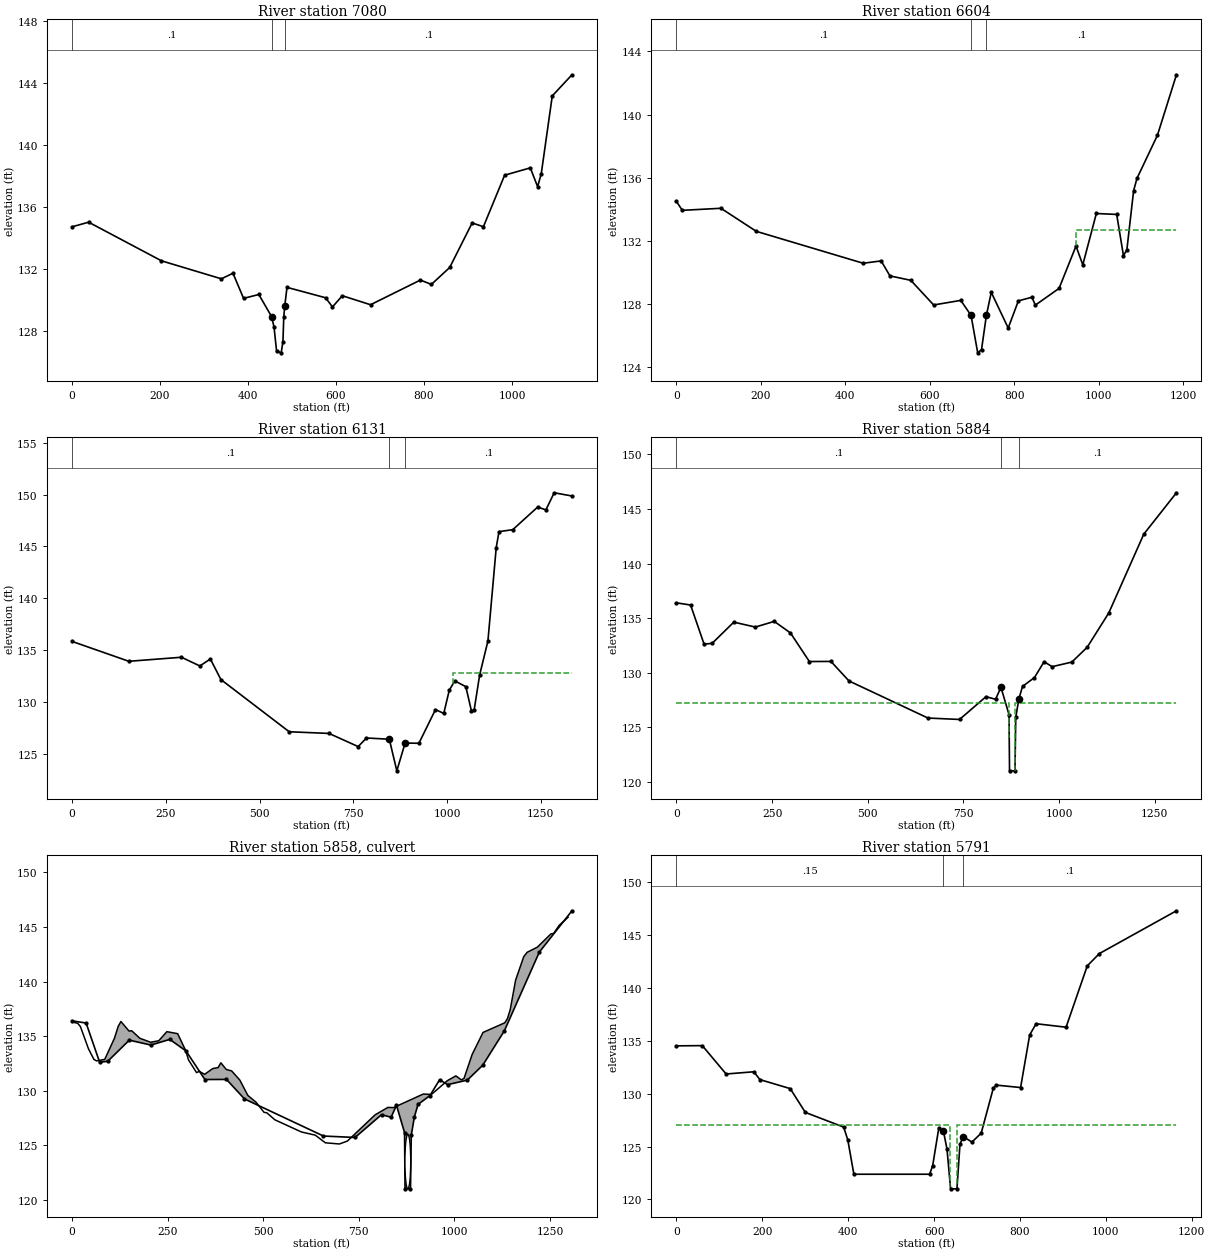
Type RM Length L Ch R = 1 ,7080    ,404.14,476.38,430.14
BEGIN DESCRIPTION:
HEC2 15789
END DESCRIPTION:
XS GIS Cut Line= 4
 1648128.6007805  727287.7482558 1647980.5284123  727005.3139555
 1647824.2298253  726799.6579124 1647355.3340402  726495.2869809
#Sta/Elev= 30
       0  134.71   37.83  135.01   203.4  132.52  339.51  131.36  365.83  131.72
  389.96   130.1  424.58  130.35  453.53  128.93   459.2  128.25  464.92  126.71
  475.43  126.59  479.37   127.3  481.34  128.93  483.64  129.63  488.62  130.81
  576.32  130.14  591.98  129.55  614.39  130.27  678.51  129.69  791.78  131.28
  816.75     131  858.38  132.09  909.36  134.96  935.01  134.72  983.25  138.04
 1041.53  138.51 1058.18   137.3  1066.5  138.14 1091.48  143.15 1136.23  144.51
#Mann= 3 , 0 , 0
       0      .1       0  453.53    .035       0  483.64      .1       0
Bank Sta=453.53,483.64
XS Rating Curve= 0 ,0
Exp/Cntr=0.3,0.1

Type RM Length L Ch R = 1 ,6604    ,375,472.53,450
BEGIN DESCRIPTION:
FEMA G HEC2 15261. Ineefective flow areas added to right side flood plain feature. See comments for downstream XS's
END DESCRIPTION:
XS GIS Cut Line= 3
 1648398.9763478  727386.7867544 1648335.5611513  726820.1412322
  1648032.804683  726286.2261492
#Sta/Elev= 30
       0   134.5   13.92  133.94  105.26  134.07  189.08  132.61  442.26  130.59
  484.69  130.74  505.55  129.79  554.95  129.51  608.98  127.95   673.2  128.24
  697.61  127.29  713.33  124.92  722.41  125.13  733.92  127.29  745.44  128.75
  785.58  126.49  809.66  128.21  841.77  128.44   849.8  127.94  905.99     129
  946.13  131.68  962.18  130.49  994.29  133.74 1042.45  133.68 1058.51  131.07
 1066.54  131.44 1082.59  135.19 1090.62  135.97 1138.78  138.68 1183.96  142.52
#Mann= 3 , 0 , 0
       0      .1       0  697.61    .035       0  733.92      .1       0
#XS Ineff= 2 , 0
       0                  946.13       0  132.68
Permanent Ineff=
       F       F
Bank Sta=697.61,733.92
XS Rating Curve= 0 ,0
Exp/Cntr=0.3,0.1

Type RM Length L Ch R = 1 ,6131    ,231.32,246.99,249.47
BEGIN DESCRIPTION:
XS '4' Br 6261. Ineffective flow area not related to bridge.
END DESCRIPTION:
XS GIS Cut Line= 3
      1648787.62       727349.55      1648738.05       726767.75
      1648500.81       726057.11
#Sta/Elev= 30
       0  135.83  151.71  133.91  291.88   134.3  340.94  133.46  368.97  134.13
     397  132.15  579.22  127.11   685.3  126.95  763.05  125.68  785.13  126.51
  846.08  126.39   866.1  123.34  888.18  126.02  924.98     126  969.14  129.25
  991.23  128.88 1005.95  131.12 1020.67  132.02 1050.11  131.46 1064.83  129.15
 1072.19  129.19 1086.91  132.59 1108.99  135.87 1131.08  144.87 1138.44  146.42
 1175.24  146.61 1241.48  148.79 1263.57  148.52 1285.65  150.17 1333.05  149.86
#Mann= 3 , 0 , 0
       0      .1       0  846.08    .035       0  888.18      .1       0
#XS Ineff= 2 , 0
       0                 1016.53       0   132.8
Permanent Ineff=
       F       F
Bank Sta=846.08,888.18
XS Rating Curve= 0 ,0
Exp/Cntr=0.5,0.3

Type RM Length L Ch R = 1 ,5884    ,103.43,93.51,93.06
BEGIN DESCRIPTION:
HEC2 14522 XS '3' BR 6262
END DESCRIPTION:
XS GIS Cut Line= 3
 1649003.3244822  727297.8025629 1648893.6412544  726544.6444369
 1648820.5191026  726003.5405323
#Sta/Elev= 30
       0   136.4   36.96   136.2   72.24  132.61   93.41  132.69  149.86  134.63
  206.32  134.18  255.71   134.7  298.05  133.64  347.45  131.02   403.9  131.03
  451.02  129.24   657.5  125.84  740.09  125.71  809.24   127.8  834.24  127.56
  848.33  128.66  869.47  126.15  870.73     121     885     121  887.03  125.91
  895.18  127.59   904.7  128.74  935.91  129.55  961.07     131  982.21  130.55
 1033.68  130.97 1073.81  132.33 1130.18  135.47 1221.78   142.7 1307.12  146.49
#Mann= 3 , 0 , 0
       0      .1       0  848.33    .035       0  895.18      .1       0
#XS Ineff= 2 , 0
       0     870   127.2     885       0   127.2
Permanent Ineff=
       F       F
Bank Sta=848.33,895.18
XS Rating Curve= 0 ,0
Exp/Cntr=0.5,0.3

Type RM Length L Ch R = 2 ,5858    ,,,
BEGIN DESCRIPTION:
Winchester Road Bridge. Use Energy only. Perched Br. Dimensional data from bridge database. Top of embankment elevations from DEM
END DESCRIPTION:
Bridge Culvert--1,0,-1,-1, 0
Deck Dist Width WeirC Skew NumUp NumDn MinLoCord MaxHiCord MaxSubmerge Is_Ogee
10,37,2.6,0, 60, 60, , , 0.95, 0, 0,0,,
       0  15.004  22.065  43.247  57.369   64.43  85.613  110.97 120.918 127.979
 149.162 156.223 177.406  205.65 226.832 248.015 276.259 297.442 304.503 325.686
 332.747 346.869 368.052 382.173 389.234 403.356 417.478 438.661 459.864 481.027
  502.21 509.271 530.454 599.882  636.04 662.455 699.215 720.273  792.47 826.049
 840.446 918.458 939.756 981.3441003.6481017.8471024.9461046.2441074.6411131.434
1138.5341145.6331159.8311181.1291189.9741216.6251252.121 1259.221273.4191296.965
 136.308 136.171 135.873 133.827 132.861 132.728 132.869 134.799 135.896 136.341
 135.464  135.49 134.802 134.438 134.576 135.409 135.226 133.662  132.83 131.652
 131.774   131.5 132.026 132.119 132.554 131.943 131.808 130.979 129.559 128.947
 128.011 127.974 127.327 126.213 125.922  125.22 125.112 125.386 127.784 128.466
 128.447 129.691 129.653 130.916 131.357 130.986 131.127 133.327 135.338  136.22
 136.617 137.419 140.136 142.291 142.685 143.155 144.371 144.408 145.145 145.898
                                                                                
                                                                                
                                                                                
                                                                                
                                                                                
                                                                                
  11.853  23.047   44.23  65.413  72.474  93.657 100.718 107.779  114.84 136.023
 143.084 150.144 157.205 171.327 185.449 206.632 220.754 227.835 248.998 270.181
 277.242 298.425 319.607  352.21 367.853 404.011 430.426 438.248 467.186 488.244
 493.282 551.862 560.441  594.02 608.417 615.486 636.734 650.933 665.131 686.429
 707.727 729.024 749.315 771.619 785.818 792.917 807.116 814.215 828.413 842.612
 899.405 906.505 913.604 927.802 931.866   949.1 957.945 984.5961020.0921027.191
 135.296 135.436 135.226 133.662  132.83 131.652 131.774 131.507   131.5 132.026
 131.971 132.119 132.554 131.943 131.808 130.979 129.938 129.559 128.947 128.011
 127.974 127.327 126.859 126.529 126.213 125.922  125.22 125.289 125.112 125.386
  125.66 127.384 127.784 128.466 128.447 128.673 128.894 129.244 129.322 129.691
 129.653 130.202 130.916 131.357 130.986 131.127 132.685 133.327 134.445 135.338
  136.22 136.617 137.419 140.136 140.652 142.291 142.685 143.155 144.371 144.408
                                                                                
                                                                                
                                                                                
                                                                                
                                                                                
                                                                                
BR Coef=-1 , 0 , 0 ,, 0 ,,,0.8,0,,0,
WSPro=,,,, 1 ,,,, 0 ,,,, 0 ,,,,-1 ,-1 ,-1 , 0 , 0 , 0 , 0 , 0
Culvert=5,5,15,67,0.024,0.7,1,41,2,121,878,121,645,Culvert #1  , 0 ,10
Culvert Bottom n=0.032
Culvert Bottom Depth=5
BC Design=,, 0 ,, 0 ,,,,,,
BC Use User HTab Curves=0
BC User HTab FreeFlow(D)= 0

Type RM Length L Ch R = 1 ,5791    ,199,158,161
BEGIN DESCRIPTION:
FEMA E HEC2 14424. XS '2' for BR 6261 Bathtub area in left overbank appears to be some type of stormwater retention pond-not a typical cross section. Applied a higher roughness value to this spot because conveyance may be overstated.
END DESCRIPTION:
XS GIS Cut Line= 2
 1649065.8587988  727055.3911873 1648894.0240638  725903.6892885
#Sta/Elev= 30
       0  134.51   60.17  134.53  115.65  131.85  180.19  132.06  194.31  131.32
  264.91  130.47  300.21  128.22  389.49  126.83  399.06  125.62  413.18  122.38
  589.68  122.38  596.74   123.2  610.86  126.72  621.84  126.43  630.14  124.74
  638.44     121  653.22     121  660.28  125.19  667.34  125.94  688.22  125.42
   709.7  126.26  737.94  130.51     745   130.8  801.48  130.57  822.66  135.54
  837.59   136.6  907.38  136.27  956.81  142.07  985.05  143.23 1164.45  147.27
#Mann= 3 , 0 , 0
       0     .15       0  621.84    .035       0  667.34      .1       0
#XS Ineff= 2 , 0
       0     638     127     654       0     127
Permanent Ineff=
       F       F
Bank Sta=621.84,667.34
XS Rating Curve= 0 ,0
Exp/Cntr=0.5,0.3

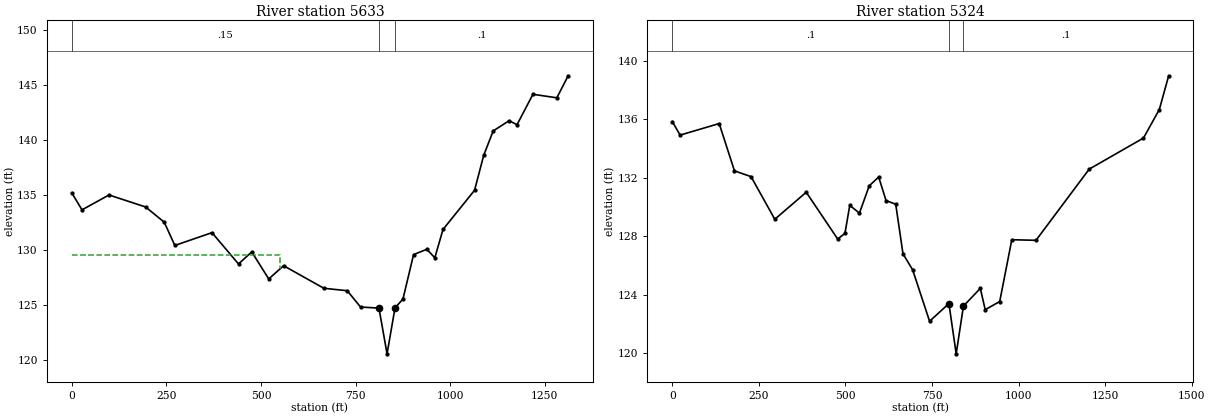
Type RM Length L Ch R = 1 ,5633    ,271,309,286
BEGIN DESCRIPTION:
XS '1"  For BR 6261. Ineffective flow area added because feature in left floodplain does not appear to be connected enought to provide meaningful conveyance.
END DESCRIPTION:
XS GIS Cut Line= 2
      1649187.75       727200.83      1649074.44       725890.68
#Sta/Elev= 30
       0  135.18   26.94  133.64   98.25  134.99  195.15   133.9  244.22  132.52
  272.25  130.41  370.38  131.57  440.47  128.73  475.51  129.82  520.35  127.37
  559.62  128.57  666.17  126.52  727.84   126.3  762.89  124.82  811.58  124.72
  832.98  120.57     854  124.74  875.03  125.55  903.07  129.58  938.11  130.06
  959.14  129.29  980.82  131.86 1064.27  135.42 1088.27  138.58 1113.34   140.8
 1155.39  141.73 1176.42  141.37 1218.47  144.13 1281.55  143.81 1311.51  145.81
#Mann= 3 , 0 , 0
       0     .15       0  811.58    .035       0     854      .1       0
#XS Ineff= 2 , 0
       0  551.02   129.5               0
Permanent Ineff=
       F       F
Bank Sta=811.58,854
XS Rating Curve= 0 ,0
Exp/Cntr=0.3,0.1

Type RM Length L Ch R = 1 ,5324    ,417.14,411.27,392.01
BEGIN DESCRIPTION:
HEC2 13945
END DESCRIPTION:
XS GIS Cut Line= 2
 1649383.5596385  727242.9609609 1649416.4646092   725809.766837
#Sta/Elev= 30
       0  135.84   22.54  134.91  135.39   135.7  179.58  132.46  227.37  132.07
  296.04  129.15  386.84     131  477.64   127.8  498.59  128.18  512.56   130.1
   540.5  129.57  568.77  131.44  596.08  132.04  617.33  130.43  645.27  130.18
  666.23  126.79  694.16  125.69  743.06  122.17  798.93  123.38  819.89  119.94
  840.84  123.21  889.68  124.42   903.7  122.96  945.61  123.52  980.54  127.75
 1050.38  127.71 1204.05  132.58 1360.81  134.71  1406.6  136.66 1433.57  138.97
#Mann= 3 , 0 , 0
       0      .1       0  798.93    .035       0  840.84      .1       0
Bank Sta=798.93,840.84
XS Rating Curve= 0 ,0
Exp/Cntr=0.3,0.1