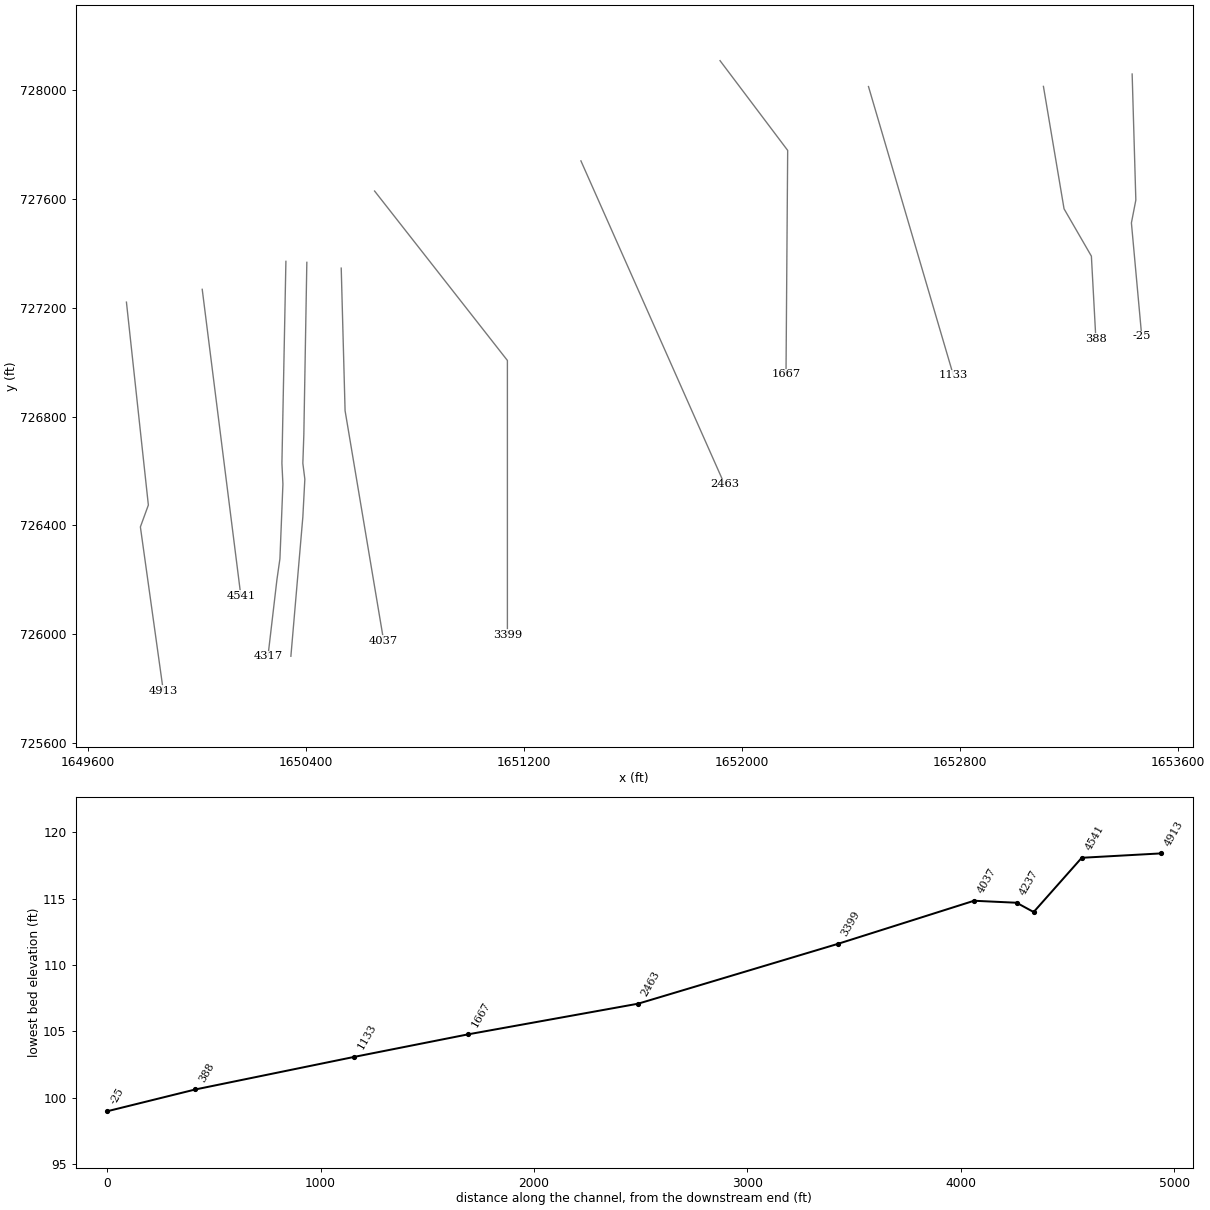
HEC-RAS study WB_Christina.prj: WB_Christina

--- WB_Christina.g13 (geometry) --- (continued)

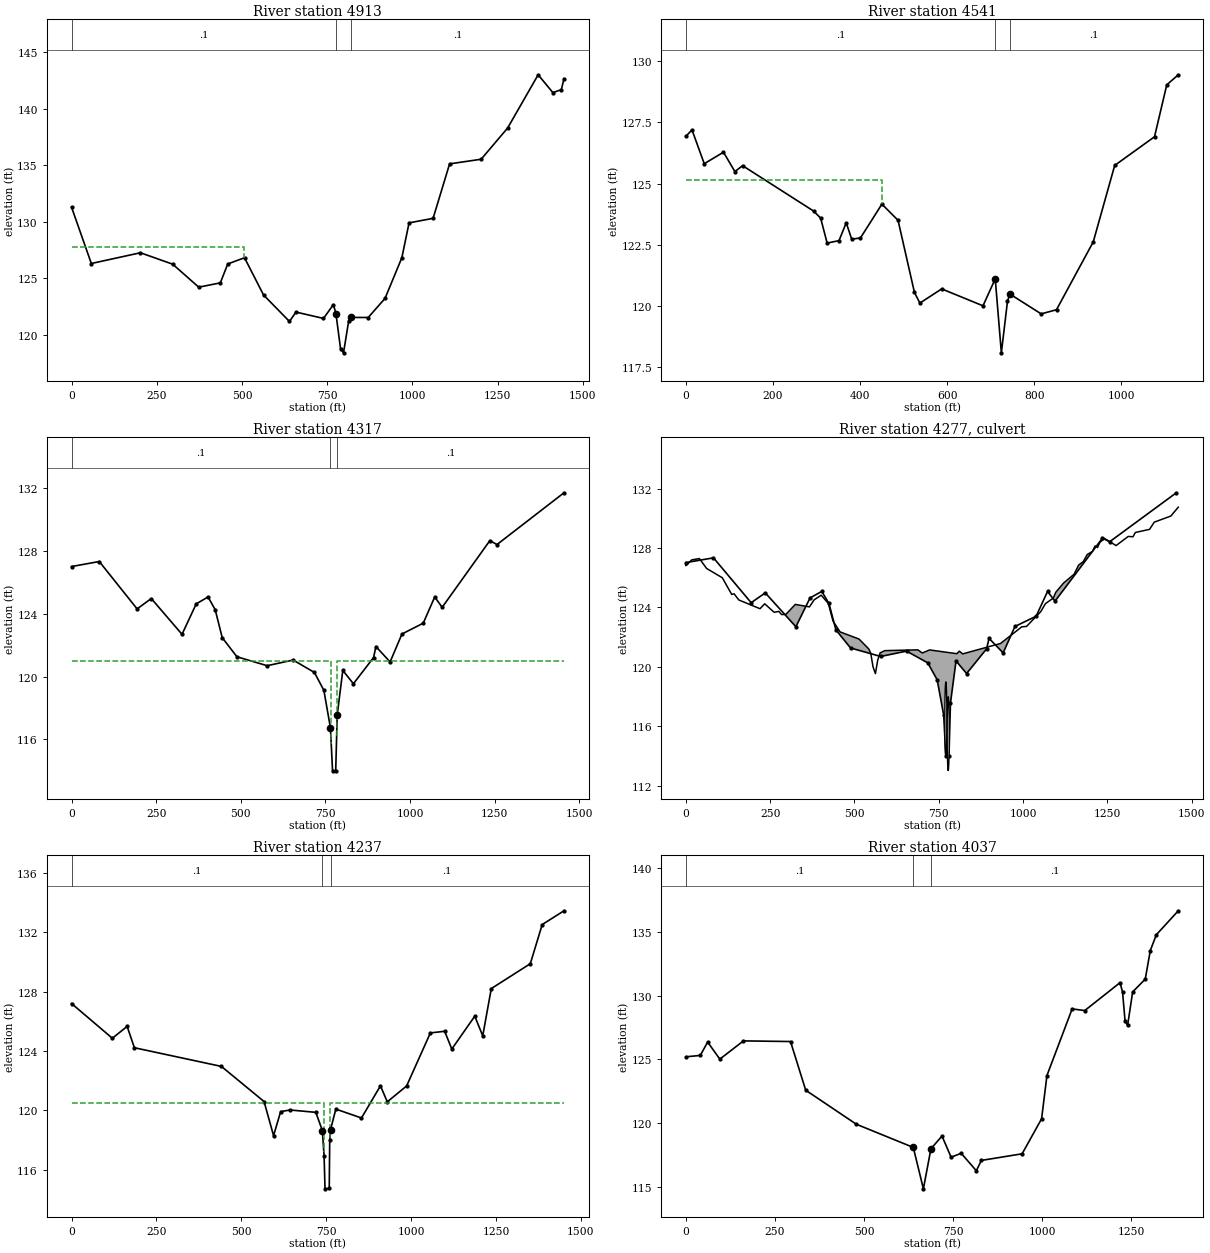
Type RM Length L Ch R = 1 ,4913    ,290,371,336
BEGIN DESCRIPTION:
HEC2 13465. Ineffective flow area added because depressed feature to the left of ineffective flow area does not appear to be long enough or connected enough to the rest of the floodplain to provide meaningful conveyance.
END DESCRIPTION:
XS GIS Cut Line= 4
 1649741.8581636  727221.0243059 1649822.2925496  726475.1783903
 1649793.0436841   726394.744028 1649877.1341516  725791.4862872
#Sta/Elev= 30
       0  131.27   57.89  126.31   201.9  127.26  296.68  126.25  373.07  124.22
  436.47   124.6  458.22  126.27  507.38  126.82  563.26  123.53  639.34  121.19
  658.36  122.02  739.15  121.46  768.23  122.68  775.66  121.89  789.27  118.77
  797.95  118.42  812.82   121.2  820.25  121.55  870.39  121.54  919.74  123.23
   969.1  126.82  990.25   129.9 1060.75   130.3 1109.18  135.11 1201.76  135.52
 1279.31  138.27 1369.07  142.98 1412.38   141.4 1437.13  141.67 1444.85  142.63
#Mann= 3 , 0 , 0
       0      .1       0  775.66    .035       0  820.25      .1       0
#XS Ineff= 2 , 0
       0  506.21   127.8               0
Permanent Ineff=
       F       F
Bank Sta=775.66,820.25
XS Rating Curve= 0 ,0
Exp/Cntr=0.3,0.1

Type RM Length L Ch R = 1 ,4541    ,222.72,225.32,201.31
BEGIN DESCRIPTION:
XS '4' BR 4680. Added ineffective flow area to left side of floodplain. Based on contours, it appears this depression feature to the left of the ineffective flow marker is not long enough to generate real conveyance.
END DESCRIPTION:
XS GIS Cut Line= 2
      1650019.87       727268.11       1650161.5       726142.09
#Sta/Elev= 30
       0  126.93   13.96  127.19   42.11  125.81   86.31  126.28  112.46  125.49
  130.16  125.73  293.05  123.88  309.45  123.59  324.37  122.57  351.67  122.67
  368.22   123.4  380.75  122.73  400.92  122.78  450.16  124.16  487.25   123.5
  524.84  120.56  537.37  120.12  587.49   120.7  682.33  120.01  710.48  121.11
  724.55  118.09  738.62   120.2  744.11  120.49  816.01  119.68  851.19  119.85
  935.61  122.62  984.86  125.74 1076.32  126.91 1104.46  129.03 1130.94  129.44
#Mann= 3 , 0 , 0
       0      .1       0  710.48    .035       0  744.11      .1       0
#XS Ineff= 2 , 0
       0  449.66  125.16               0
Permanent Ineff=
       F       F
Bank Sta=710.48,744.11
XS Rating Curve= 0 ,0
Exp/Cntr=0.5,0.3

Type RM Length L Ch R = 1 ,4317    ,80.24,79.96,81.35
BEGIN DESCRIPTION:
HEC2 12877 XS '3' BR 4680
END DESCRIPTION:
XS GIS Cut Line= 6
 1650326.8353546  727370.9247148 1650312.2109337  726628.7349044
 1650315.8670389  726551.9566474 1650304.8987233  726277.7485898
 1650293.9304076  726200.9703327 1650261.0254369  725919.4500648
#Sta/Elev= 30
       0  127.02   81.78  127.34  193.53  124.32  235.43  124.98  326.23   122.7
  368.13  124.64  403.05  125.08   424.2  124.27  444.96  122.49  488.33  121.27
  577.66   120.7  654.48  121.06  717.34  120.27  745.28  119.13  764.67  116.74
  770.93     114  780.24     114  784.69  117.56  801.21   120.4  832.51  119.55
  892.06  121.22  899.05  121.92  940.98  120.94  975.92  122.72 1038.82  123.41
 1072.74  125.08 1094.74  124.42  1235.6  128.67 1256.69  128.42 1454.62  131.72
#Mann= 3 , 0 , 0
       0      .1       0  764.67    .035       0  784.69      .1       0
#XS Ineff= 2 , 0
       0     767     121     783       0     121
Permanent Ineff=
       F       F
Bank Sta=764.67,784.69
XS Rating Curve= 0 ,0
Exp/Cntr=0.5,0.3

Type RM Length L Ch R = 2 ,4277    ,,,
BEGIN DESCRIPTION:
Chestnut Drive. Modified Rise/Span dimentions to work with pipe arch dimensions available in model. Energy only. Perched Br.
END DESCRIPTION:
Bridge Culvert--1,0,-1,-1, 0
Deck Dist Width WeirC Skew NumUp NumDn MinLoCord MaxHiCord MaxSubmerge Is_Ogee
10,36,2.6,0, 60, 60, 121.1, , 0.95, 0, 0,0,,
       017.1634339.9614361.48752107.9722135.9133142.8986156.8692219.7368233.7073
261.6485 275.619283.9238296.5749324.5161366.4278380.3984401.3542422.3101436.2807
457.2365513.5354542.2177548.0529555.0469562.0409569.0349576.0289590.0169687.8431
701.0817722.9032803.3882811.0483820.9971933.1595996.2986 1010.331052.4221066.453
1089.3971097.1641120.4651151.533 1164.671178.7011190.3691205.903 1213.671220.793
1227.809 1241.841275.8071311.9941326.0251333.0411375.1331389.1641438.2731460.461
126.8197127.2027127.2908126.6231125.9988124.8741124.9187124.5047123.9144124.2451
123.6739123.7348  123.52123.5356124.2058124.0385124.5148 124.825124.2731123.0843
122.3541121.8721121.2108120.9387119.9949119.5438120.4642120.9424121.0929121.1463
120.9337121.1413120.8874121.0561120.8749121.5747122.6982122.7224123.7147124.2581
124.6243 125.024125.6493126.2414126.8473127.0902127.5633127.7745128.1415128.0329
128.3852128.6438128.1646128.7811128.7578129.0466129.2572 129.743130.1525130.7516
                                                                                
                                                                                
                                                                                
                                                                                
                                                                                
                                                                                
       017.1634339.9614361.48752107.9722135.9133142.8986156.8692219.7368233.7073
261.6485 275.619283.9238296.5749324.5161366.4278380.3984401.3542422.3101436.2807
457.2365513.5354542.2177548.0529555.0469562.0409569.0349576.0289590.0169687.8431
701.0817722.9032803.3882811.0483820.9971933.1595996.2986 1010.331052.4221066.453
1089.3971097.1641120.4651151.533 1164.671178.7011190.3691205.903 1213.671220.793
1227.809 1241.841275.8071311.9941326.0251333.0411375.1331389.1641438.2731460.461
126.8197127.2027127.2908126.6231125.9988124.8741124.9187124.5047123.9144124.2451
123.6739123.7348  123.52123.5356124.2058124.0385124.5148 124.825124.2731123.0843
122.3541121.8721121.2108120.9387119.9949119.5438120.4642120.9424121.0929121.1463
120.9337121.1413120.8874121.0561120.8749121.5747122.6982122.7224123.7147124.2581
124.6243 125.024125.6493126.2414126.8473127.0902127.5633127.7745128.1415128.0329
128.3852128.6438128.1646128.7811128.7578129.0466129.2572 129.743130.1525130.7516
                                                                                
                                                                                
                                                                                
                                                                                
                                                                                
                                                                                
BR Coef=-1 , 0 , 0 ,, 0 ,,,0.8,0,,0,
WSPro=,,,, 1 ,,,, 0 ,,,, 0 ,,,,-1 ,-1 ,-1 , 0 , 0 , 0 , 0 , 0
Culvert=5,5,6,60,0.024,0.5,1,41,1,114,771,114,749,Culvert #1  , 0 ,10
Culvert Bottom n=0.024
Culvert Bottom Depth=1
Culvert=5,5,6,60,0.024,0.5,1,41,1,113,778,113,756,Culvert #2  , 0 ,10
Culvert Bottom n=0.03
Culvert Bottom Depth=1
Culvert Depth Blocked=1
BC Design=,, 0 ,, 0 ,,,,,,
BC Use User HTab Curves=0
BC User HTab FreeFlow(D)= 0

Type RM Length L Ch R = 1 ,4237    ,171.08,199.48,195.54
BEGIN DESCRIPTION:
HEC2 12816 XS '2' BR 4680
END DESCRIPTION:
XS GIS Cut Line= 6
 1650403.6136116  727367.2686096  1650392.645296   726734.762027
 1650388.9891908  726628.7349044 1650396.3014012  726570.2371734
 1650388.9891908  726431.3051039 1650345.1159044  725919.4500648
#Sta/Elev= 30
       0   127.2  120.02  124.86  163.62  125.66  184.94  124.22  441.28  122.96
  566.99  120.59  594.93  118.29  615.88  119.91  643.82  120.02  719.53  119.86
  738.69  118.63  743.75  116.94  746.58   114.7     759  114.73  760.36  117.97
  762.77  118.69  778.43  120.08   853.9  119.48  909.84  121.65  929.97  120.57
  986.87  121.64 1056.95  125.22    1099  125.33 1120.03  124.13 1187.73  126.35
 1211.14  125.02 1236.33  128.21 1351.31  129.89 1386.35  132.53  1450.5  133.46
#Mann= 3 , 0 , 0
       0      .1       0  738.69    .035       0  762.77      .1       0
#XS Ineff= 2 , 0
       0     743   120.5     761       0   120.5
Permanent Ineff=
       F       F
Bank Sta=738.69,762.77
XS Rating Curve= 0 ,0
Exp/Cntr=0.5,0.3

Type RM Length L Ch R = 1 ,4037    ,628,638,613
BEGIN DESCRIPTION:
XS '1' BR 4680
END DESCRIPTION:
XS GIS Cut Line= 3
      1650529.76       727346.01      1650543.92       726821.95
      1650685.56       725975.66
#Sta/Elev= 30
       0  125.21   40.45  125.32   60.97  126.37   95.18  125.03  161.62  126.46
   293.6  126.41  336.23  122.59  478.32  119.92  638.23   118.1  666.54  114.85
  687.77     118  718.85  118.99  744.39  117.33  772.69  117.64  815.15  116.27
  829.31  117.08  943.69   117.6  998.37  120.35 1013.31  123.74 1084.07  128.97
 1119.46  128.84 1218.53  131.03 1225.61  130.28 1232.69     128 1239.76  127.68
 1253.92   130.3  1289.3  131.31 1303.45  133.55 1320.43  134.79 1382.03  136.67
#Mann= 3 , 0 , 0
       0      .1       0  638.23    .035       0  687.77      .1       0
Bank Sta=638.23,687.77
XS Rating Curve= 0 ,0
Exp/Cntr=0.3,0.1

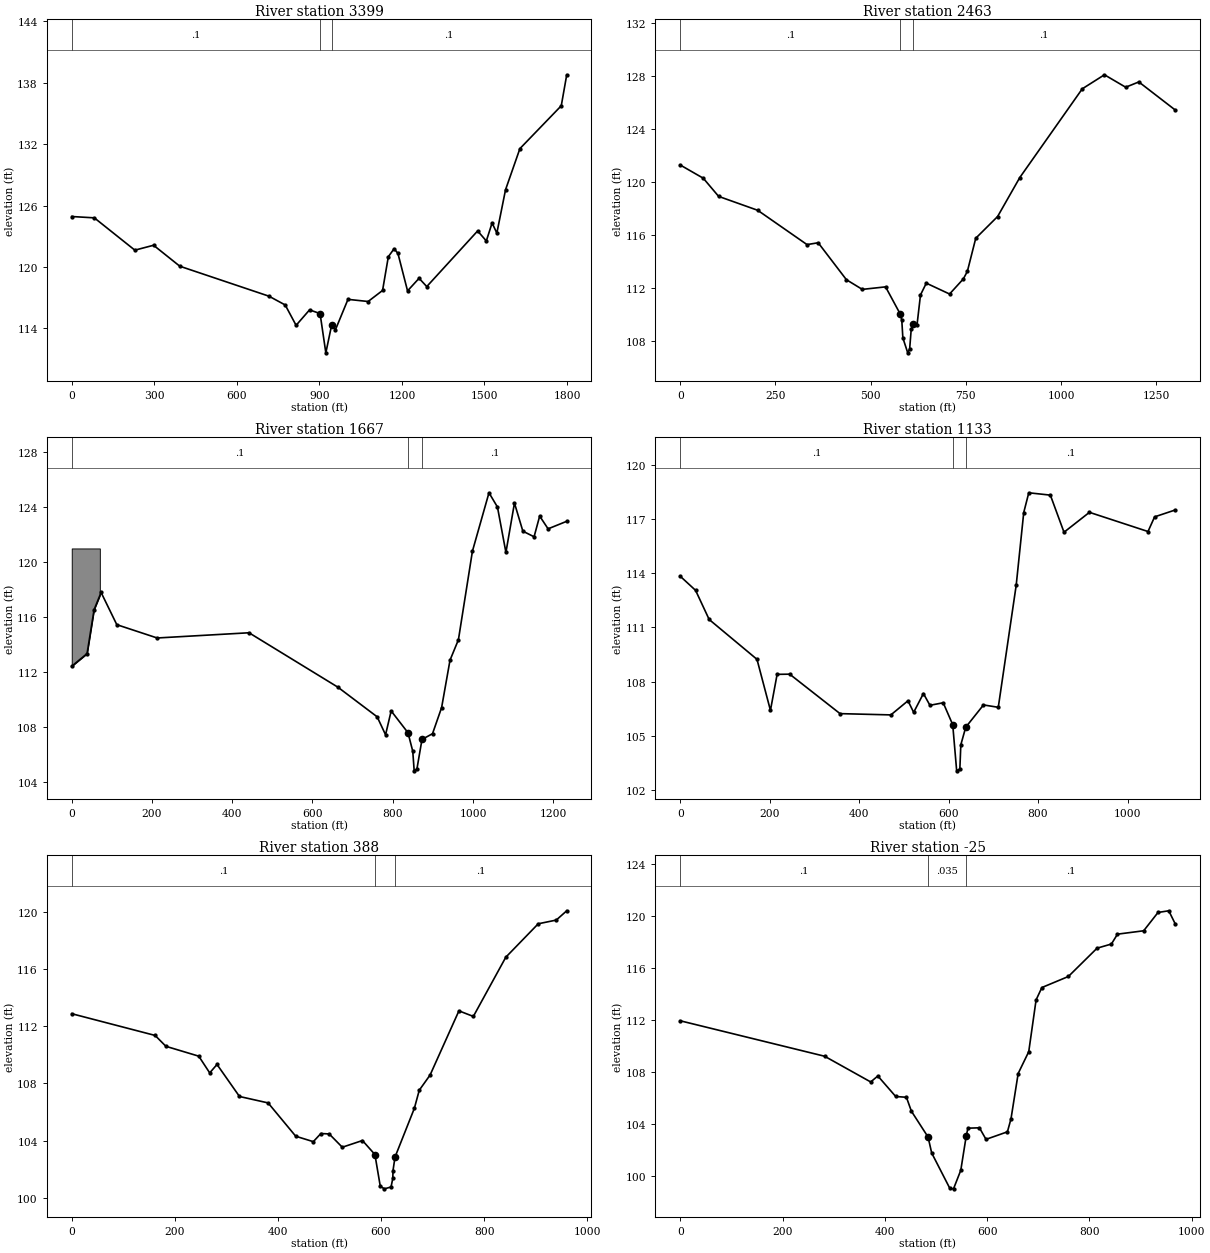
Type RM Length L Ch R = 1 ,3399    ,618,936,688
BEGIN DESCRIPTION:
FEMA C HEC2 11957. Based on DEM, the elevated point in right floodplain appears to be a small 'island' the cross section was drawn through. Does not appear appropriate to code with a levee or ineffective flow area.
END DESCRIPTION:
XS GIS Cut Line= 3
      1650652.16       727629.37      1651139.33       727006.64
      1651139.33       725998.41
#Sta/Elev= 30
       0  124.93   82.07   124.8   229.4  121.64  297.39  122.12  392.78  120.07
  716.71  117.14  775.81  116.28  815.37  114.29  864.25   115.8  902.49  115.44
  923.43   111.6  944.38   114.3  958.35  113.86 1003.91  116.83 1077.06  116.62
  1129.6   117.7 1150.55     121  1171.5  121.78 1185.46  121.32 1220.38  117.66
 1262.28  118.89 1290.21  118.08 1475.08  123.52 1506.67  122.54 1527.62   124.3
 1544.91  123.31  1576.5  127.55  1628.7  131.57 1779.01  135.76 1798.88  138.79
#Mann= 3 , 0 , 0
       0      .1       0  902.49    .035       0  944.38      .1       0
Bank Sta=902.49,944.38
XS Rating Curve= 0 ,0
Exp/Cntr=0.3,0.1

Type RM Length L Ch R = 1 ,2463    ,578.4,796.34,536.96
BEGIN DESCRIPTION:
HEC2 10897
END DESCRIPTION:
XS GIS Cut Line= 2
 1651409.0431639  727740.1915555 1651935.5226477  726551.9566474
#Sta/Elev= 30
       0  121.27   60.56  120.27  100.85   118.9  203.46  117.85  332.93  115.26
  362.23   115.4  436.33  112.61  478.05  111.88  539.15  112.07  578.18  109.99
  581.72  109.55  584.52  108.22  597.35  107.09  602.39  107.39  606.43  108.86
  610.98  109.24  621.57  109.16   630.8  111.46  646.07  112.35  707.17  111.53
   743.3  112.67  753.88  113.24  775.91  115.74  833.27  117.38  891.49  120.32
 1055.56  127.02 1113.78  128.08 1169.58  127.14 1204.05  127.54 1299.65  125.42
#Mann= 3 , 0 , 0
       0      .1       0  578.18    .035       0  610.98      .1       0
Bank Sta=578.18,610.98
XS Rating Curve= 0 ,0
Exp/Cntr=0.3,0.1

Type RM Length L Ch R = 1 ,1667    ,466,533.56,503.25
BEGIN DESCRIPTION:
FEMA B HEC2 10100. Cross section extended to the left for mapping purposes-to expand the bounding polygon. Left portion blocked because flow could not reach this topography.
END DESCRIPTION:
XS GIS Cut Line= 3
      1651919.37       728108.59  1652167.475898  727778.7336247
 1652161.3389469  726956.3816346
#Sta/Elev= 30
       0  112.41   38.24  113.33   55.71  116.53   73.18  117.79  112.33  115.44
  212.95  114.47   441.8  114.85  663.37  110.88  761.14  108.72  782.09  107.41
  796.05  109.15  837.95  107.56  849.86  106.21  853.42  104.78  860.22  104.91
  872.87  107.07  899.11  107.49  921.75  109.39   942.7  112.85  963.64  114.34
  998.56   120.8 1039.82  125.06 1060.93  124.02 1082.03  120.71 1103.31  124.31
 1124.25  122.26 1152.19  121.85 1166.15  123.36  1187.1  122.43 1233.59  122.98
#Mann= 3 , 0 , 0
       0      .1       0  837.95    .035       0  872.87      .1       0
#Block Obstruct= 2 , 0
       0   70.03     121               0
Bank Sta=837.95,872.87
XS Rating Curve= 0 ,0
Exp/Cntr=0.3,0.1

Type RM Length L Ch R = 1 ,1133    ,623.86,745.84,652.46
BEGIN DESCRIPTION:
HEC2 9590
END DESCRIPTION:
XS GIS Cut Line= 2
 1652463.9271816  728013.4060387 1652775.4725569  726951.4426617
#Sta/Elev= 30
       0  113.83   34.33  113.05   64.71  111.44  171.61  109.24  201.71  106.42
  216.62  108.41  244.76  108.42  357.29  106.24  470.96  106.17   509.2  106.95
   521.9  106.31  543.73  107.35  558.29   106.7  587.97  106.84  609.23  105.63
  618.07  103.08  625.18  103.18  627.36  104.52  638.34  105.49     678  106.72
  711.11  106.59  751.14  113.33  768.02  117.35  779.27  118.44  827.54  118.31
  858.04  116.26  914.87  117.36 1045.85   116.3  1060.6  117.11 1106.72  117.49
#Mann= 3 , 0 , 0
       0      .1       0  609.23    .035       0  638.34      .1       0
Bank Sta=609.23,638.34
XS Rating Curve= 0 ,0
Exp/Cntr=0.3,0.1

Type RM Length L Ch R = 1 ,388     ,334.92,412.33,373.6
BEGIN DESCRIPTION:
FEMA Cross Section A HEC2 9079
END DESCRIPTION:
XS GIS Cut Line= 4
 1653105.6117545  728013.9835799 1653181.3008775   727563.940206
 1653281.5378063  727390.0598126 1653297.9030259  727087.3033443
#Sta/Elev= 30
       0  112.87  161.77  111.35  182.69  110.59  246.42   109.9  267.66  108.73
  281.83  109.32  325.43  107.08  380.96  106.63  434.54   104.3  468.63  103.92
  483.37  104.49  499.49  104.46  524.87  103.53  563.97     104  588.15  103.02
  598.55   100.8  606.67  100.62  619.43  100.75  622.84  101.35  623.27   101.9
  627.13  102.84  664.65  106.25   674.2  107.52  695.18  108.58  751.12  113.07
  779.09  112.68  842.03  116.82  904.97  119.16  939.93  119.42  960.27  120.07
#Mann= 3 , 0 , 0
       0      .1       0  588.15    .035       0  627.13      .1       0
Bank Sta=588.15,627.13
XS Rating Curve= 0 ,0
Exp/Cntr=0.3,0.1

Type RM Length L Ch R = 1 ,-25     ,0,0,0
BEGIN DESCRIPTION:
HEC2 9590 XS is just in Delaware
END DESCRIPTION:
XS GIS Cut Line= 4
 1653431.0723979  728059.4605638 1653444.6178562  727596.2061313
  1653428.363311  727512.2243419 1653466.2905753  727095.0244345
#Sta/Elev= 30
       0  111.92   282.3  109.19  372.44  107.21  386.41  107.67  421.34  106.09
   442.3  106.03  451.99  104.96  484.59  102.97   491.7  101.74  527.26   99.01
  534.37   98.98   548.6  100.41  559.35  103.08  562.63  103.65  585.06  103.68
  597.92  102.79  639.76  103.37  646.77  104.37  660.79  107.86  681.47  109.54
  695.85  113.53  707.18  114.48  758.95  115.33  815.05  117.51  843.09  117.83
  855.01  118.59   906.2  118.85  934.24  120.26  955.28  120.39  967.91  119.38
#Mann= 3 , 0 , 0
       0      .1       0  484.59    .035       0  559.35      .1       0
Bank Sta=484.59,559.35
XS Rating Curve= 0 ,0
Exp/Cntr=0.3,0.1
Stream Node=westbrchristine ,westbrchristine , 0 , 0 ,Upstream end
Stream Node=westbrchristine ,westbrchristine , 0 , 1 ,Downstream end

Chan Stop Cuts=-1
Use User Specified Reach Order=0
User Specified Reach Order=westbrchristine ,westbrchristine