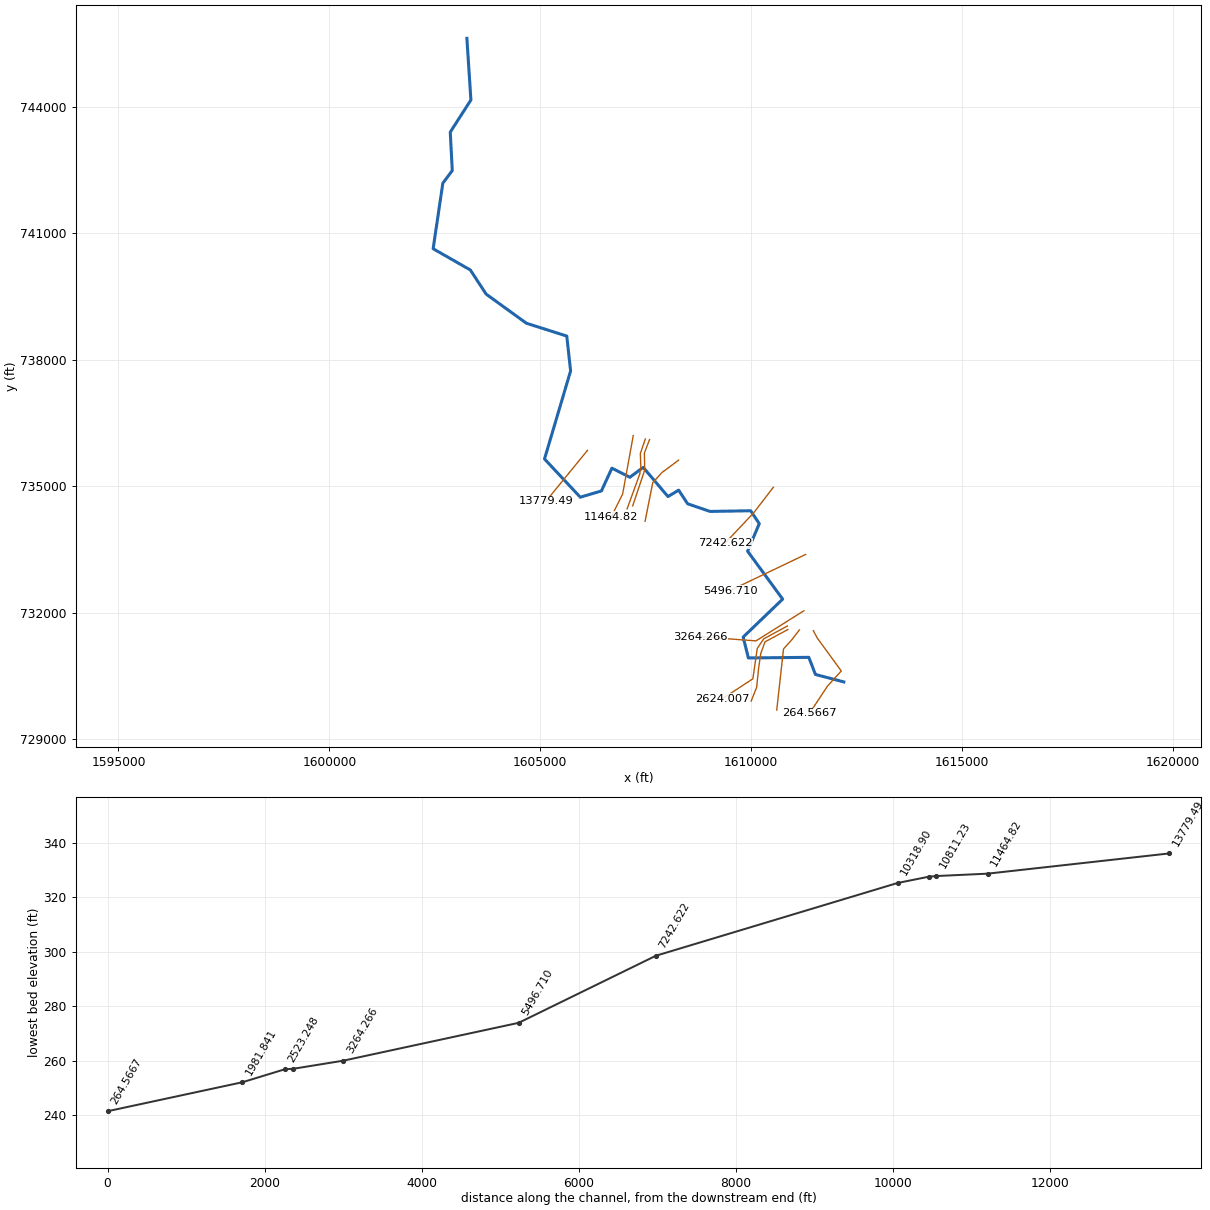
--- WestBrLittleNECreek.prj (project) ---

Proj Title=West Branch Little Northeast Creek
Current Plan=p02
Default Exp/Contr=0.3,0.1
English Units
Geom File=g01
Flow File=f01
Plan File=p02
Y Axis Title=Elevation
X Axis Title(PF)=Main Channel Distance
X Axis Title(XS)=Station
BEGIN DESCRIPTION:
Westbranch Little NE Ck, Cecil Co., MD. Geo-referenced HEC-RAS model. Vertical datum NAVD88 Created by Pat Wheeler, Seattle District, for MDE Map Modernization
END DESCRIPTION:
DSS File=dss
DSS Export Rating Curves= 0
DSS Export Rating Curve Sorted= 0
DSS Export Volume Flow Curves= 0
DXF Filename=Westbranch.
DXF OffsetX= 0
DXF OffsetY= 0
DXF ScaleX= 1
DXF ScaleY= 10

--- WestBrLittleNECreek.p02 (plan) ---

Plan Title=West Br Little NE Creek Freq Profiles
Program Version=4.00
Short Identifier=West Br Litt
Geom File=g01
Flow File=f01
Subcritical Flow
K Sum by GR= 0
Std Step Tol= 0.01
Critical Tol= 0.01
Num of Std Step Trials= 20
Max Error Tol= 0.3
Flow Tol Ratio= 0.001
Split Flow NTrial= 30
Split Flow Tol= 0.02
Split Flow Ratio= 0.02
Log Output Level= 0
Friction Slope Method= 1
Unsteady Friction Slope Method= 2
Unsteady Bridges Friction Slope Method= 1
Parabolic Critical Depth
Global Vel Dist= 0 , 0 , 0
Global Log Level= 0
CheckData=True
Encroach Param=-1 ,0,0, 0
Computation Interval=1HOUR
Output Interval=1HOUR
Run HTab= 0
Run UNet= 0
Run PostProcess= 0
Run WQNet= 0
UNET Theta= 1
UNET Theta Warmup= 1
UNET ZTol= 0.02
UNET ZSATol= 0.05
UNET MxIter= 20
UNET MaxInSteps= 0
UNET DtIC= 0
UNET DtMin= 0
UNET MaxCRTS= 20
UNET WFStab= 2
UNET SFStab= 1
UNET WFX= 1
UNET SFX= 1
UNET DSS MLevel= 4
UNET DZMax Abort= 100
UNET Convert EG Bridges= 0
UNET Use Existing IB Tables=-1
UNET Froude Reduction=False
UNET Froude Limit= 1
UNET Froude Power= 10
UNET Time Slicing=0,0, 5
Instantaneous Interval=1HOUR
DSS File=dss
Write IC File= 0
Echo Input=False
Echo Output=False
Write Detailed= 0
Detailed Automatic Start=False, 10
WQ ULTIMATE=-1
WQ Max Comp Step=1HOUR
WQ Output Interval=15MIN
WQ Output Selected Increments= 0
WQ Output face flow=0
WQ Output face velocity=0
WQ Output face area=0
WQ Output face dispersion=0
WQ Output cell volume=0
WQ Output cell surface area=0
WQ Output cell continuity=0
WQ Output face conc=0
WQ Output face dconc_dx=0
WQ Output face courant=0
WQ Output face peclet=0
WQ Output face adv mass=0
WQ Output face disp mass=0
WQ Output cell mass=0
WQ Output cell source sink temp=0
WQ Output cell source sink nsm=0
WQ Output MaxMinRange=-1
WQ Daily Max Min Mean=-1
WQ Daily Range=0
WQ Daily Time=0
WQ Create Restart=0
WQ Fixed Restart=0
WQ System Summary=False
Sorting and Armoring Iterations= 10
XS Update Threshold= 0.02
Hydraulics Update Threshold= 0.02
Energy Slope Method= 1
Volume Change Method= 0
XS Weighting Method= 0
Number of US Weighted Cross Sections= 1
Number of DS Weighted Cross Sections= 1
Upstream XS Weight=0.25
Main XS Weight=0.5
Downstream XS Weight=0.25
Number of DS XS's Weighted with US Boundary= 1
Upstream Boundary Weight= 1
Weight of XSs Associated with US Boundary= 0
Number of US XS's Weighted with DS Boundary= 1
Downstream Boundary Weight= 0.5
Weight of XSs Associated with DS Boundary= 0.5
Sediment Output Level= 4
Mass or Volume Output= 0
Output Increment Type= 1
Profile and TS Output Increment= 10
XS Output Flag= 0
XS Output Increment= 10
Disregard all LS=0
Disregard all Conn=0
Disregard all Breaches=0
Disregard all Pumps=0

--- WestBrLittleNECreek.f01 (steady flow) ---

Flow Title=West Br Little NE Creek Frequency Flows
Program Version=4.00
Number of Profiles= 2
Profile Names=100-YR,100-ULT
River Rch & RM=Little NE Creek,Westbranch      ,13779.49
    2830    2840
River Rch & RM=Little NE Creek,Westbranch      ,10318.90
    3120    3130
River Rch & RM=Little NE Creek,Westbranch      ,7242.622
    3310    3350
River Rch & RM=Little NE Creek,Westbranch      ,3264.266
    3580    3690
River Rch & RM=Little NE Creek,Westbranch      ,264.5667
    3760    3860
Boundary for River Rch & Prof#=Little NE Creek,Westbranch      , 1
Up Type= 0
Dn Type= 3
Dn Slope=0.006
Boundary for River Rch & Prof#=Little NE Creek,Westbranch      , 2
Up Type= 0
Dn Type= 3
Dn Slope=0.006
DSS Import GetInterval= 0
DSS Import GetPeak= 0
DSS Import FillOption= 0

--- WestBrLittleNECreek.g01 (geometry) ---

Geom Title=West Br Little NE Creek Geometry
Program Version=4.00

River Reach=Little NE Creek ,Westbranch
Reach XY= 30
1603261.00175026745616.7822184561603356.50194529744155.629233927
1602867.06344558743394.0151783081602914.81354311742481.988315403
1602690.38808469742181.1627009211602461.18761659740628.807030112
1603343.60941897740124.5660001641603717.49268267739552.519831717
1604673.44963528738861.575920388 1605629.4065879738557.885300085
1605720.13177323737731.8086127491605101.29050918735644.174348578
 1605949.3322414734738.3549983651606450.70826547 734886.38030073
1606699.00877266735425.9564028681607126.37214561735211.080963954
1607441.52278931735445.0564418881608028.84898898734752.680027634
 1608281.9245059734905.4803397361608493.93493897734582.212179437
1609023.96102154734400.761808813 1609988.0354908734416.519341007
1610193.36091018734110.9187167881609916.41034448 733457.69738254
1610747.26204154732321.2450612341609811.36012991731421.633223712
 1609935.0328825730926.942213252 1611367.5358085730941.267242506
1611524.63362941730535.3914134651612197.91000462730358.716052592

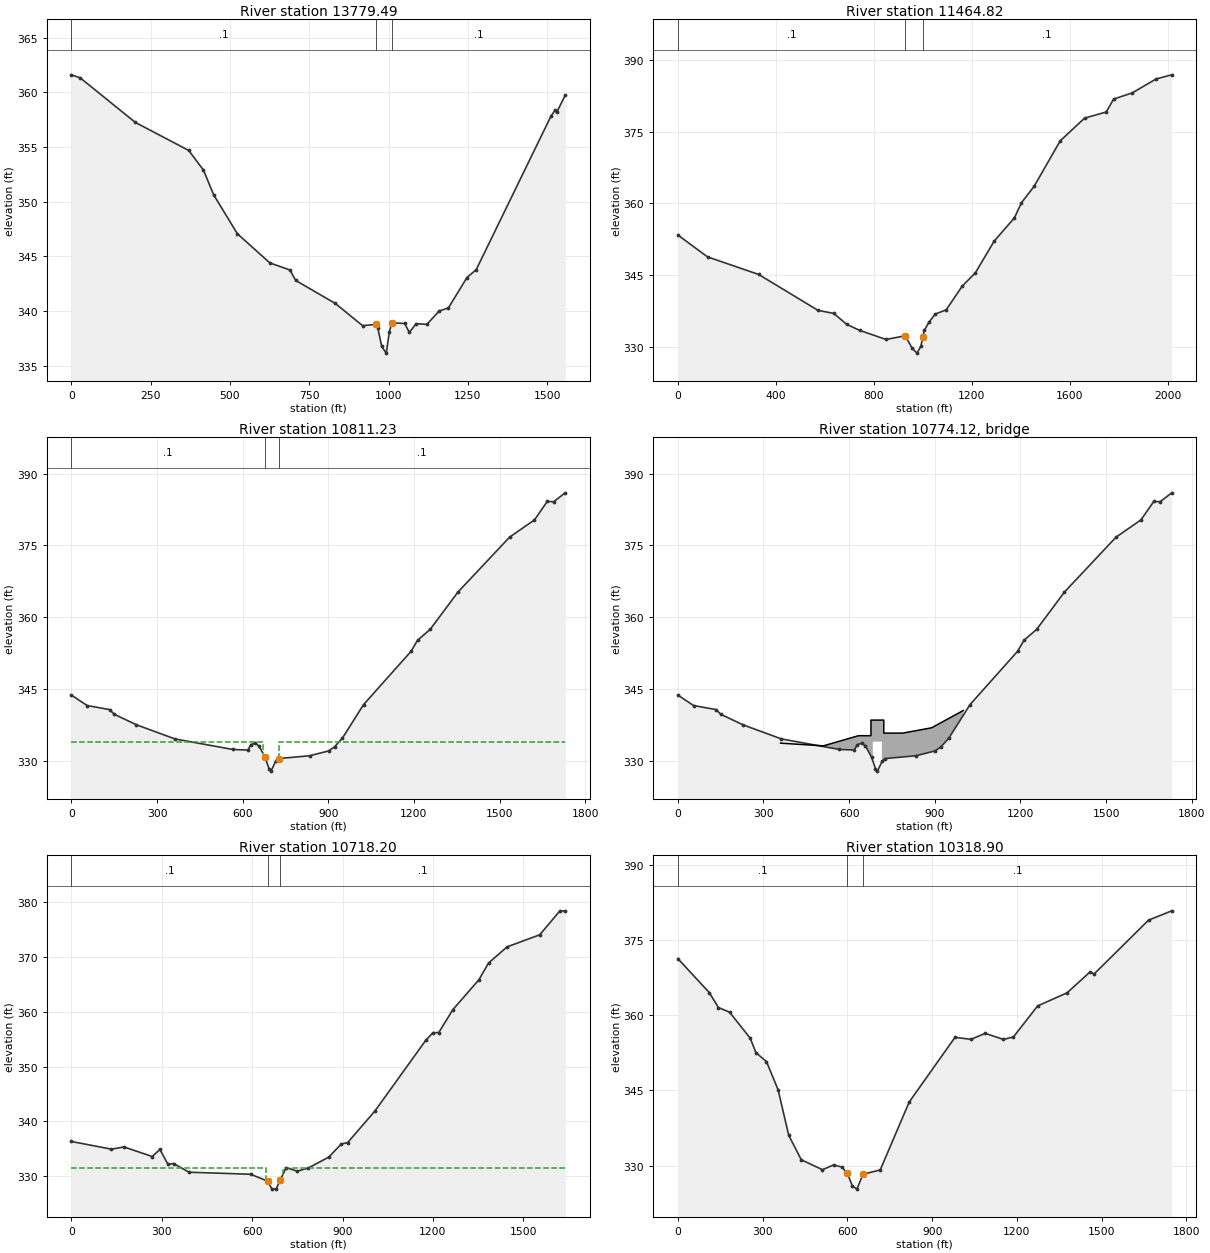
Type RM Length L Ch R = 1 ,13779.49,2193.39,2314.67,2114.7
XS GIS Cut Line= 2
1606119.53257479735847.3454711441605134.55901268734641.255395085
#Sta/Elev= 30
       0  361.59   27.63  361.32  201.75  357.24  370.13  354.68  416.54  352.88
  448.63  350.63  523.34  347.07  625.98   344.4  688.84  343.76  707.32   342.8
  832.19   340.7  918.14  338.67  958.91  338.78  966.01  338.48  978.46  336.77
  992.76  336.16 1002.71  338.12 1010.27  338.93 1050.76  338.87 1065.61  338.05
 1086.91  338.85 1120.94  338.79 1159.21     340 1188.91   340.3  1247.3  343.07
 1276.46  343.79 1511.68  357.79 1525.07  358.37 1530.05  358.16 1557.19  359.73
#Mann= 3 , 0 , 0
       0      .1       0  958.91    .045       0 1010.27      .1       0
Bank Sta=958.91,1010.27
XS Rating Curve= 0 ,0
Exp/Cntr=0.3,0.1

Type RM Length L Ch R = 1 ,11464.82,429.18,653.59,507.55
XS GIS Cut Line= 3
1607205.01364324736199.1217433361606953.74487741734812.118155867
1606682.37461026734269.377621636
#Sta/Elev= 30
       0  353.39  121.33  348.82  330.21  345.15  572.05  337.66  636.46  337.02
  689.47  334.73  741.87  333.48  850.24  331.57  928.49  332.35  956.95  329.71
  976.48  328.72  992.52  330.19  999.63  332.05 1006.75  333.52 1025.41  335.19
 1050.84  336.88 1095.41  337.76 1161.66  342.75 1214.92  345.51  1291.3   352.1
 1374.05  356.97 1402.87  360.14 1454.52  363.56 1561.21  373.07 1660.68  377.81
 1749.04  379.09 1779.17  381.79 1854.55  383.06 1952.52  385.99 2016.38  386.85
#Mann= 3 , 0 , 0
       0      .1       0  928.49    .045       0  999.63      .1       0
Bank Sta=928.49,999.63
XS Rating Curve= 0 ,0
Exp/Cntr=0.5,0.3

Type RM Length L Ch R = 1 ,10811.23,91.25,93.03,97.84
XS GIS Cut Line= 5
1607491.24507195736119.1747984441607373.76207604735775.117453247
1607384.95093277735442.2489647721607355.77490276735274.452685028
1607060.47408685734463.223998711
#Sta/Elev= 30
       0  343.72   55.36  341.54  133.86  340.69  150.78   339.7  227.98  337.52
  363.16  334.56  566.29  332.36  618.38  332.24  628.41  333.35  644.63  333.68
  657.35  333.07  678.51  330.76  692.37  328.38  699.41  327.84  715.74  329.92
  726.66  330.47   834.4  331.05  901.44  332.06  922.22  332.93  949.76  334.76
 1023.67  341.74  1190.4  352.89 1212.75  355.18 1256.86  357.44 1354.28  365.24
 1534.95   376.7 1622.42  380.32 1667.16  384.16  1689.5  384.11 1730.24  385.97
#Mann= 3 , 0 , 0
       0      .1       0  678.51     .04       0  726.66      .1       0
#XS Ineff= 2 , 0
             673  333.98  725.66          334.01
Permanent Ineff=
       F       F
Bank Sta=678.51,726.66
XS Rating Curve= 0 ,0
Exp/Cntr=0.5,0.3

Type RM Length L Ch R = 3 ,10774.12,,,
BEGIN DESCRIPTION:
Wheatley Rd.
END DESCRIPTION:
Bridge Culvert--1,0,-1,-1, 0
Deck Dist Width WeirC Skew NumUp NumDn MinLoCord MaxHiCord MaxSubmerge Is_Ogee
25,30,2.6,0, 12, 13, , , 0.98, 0, 0,0,,
     360     510     633   676.5   676.5     683     715   721.5   721.5     788
     889    1000
  333.68  333.12  335.24  335.24   338.5   338.5   338.5   338.5  335.78  335.78
  336.89   340.5
                                             334     334
                
     200     343     553     643   652.5   652.5     659     691   697.5   697.5
     831     932    1036
  333.68  333.68  333.12  335.24  335.24   338.5   338.5   338.5   338.5  335.78
  335.78  336.89  340.87
                                                     334     334
                        
BR Coef=-1 , 0 , 0 ,, 0 ,,,0.8,0,,0,
WSPro=,,,, 1 ,,,, 0 ,,,, 0 ,,,,-1 ,-1 ,-1 , 0 , 0 , 0 , 0 , 0
BC Design=,, 0 ,, 0 ,,,,,,
BC Use User HTab Curves=0
BC User HTab FreeFlow(D)= 0

Type RM Length L Ch R = 1 ,10718.20,415.58,399.3,382.91
XS GIS Cut Line= 4
1607591.94478273736102.3915133331607468.86735846735786.306309998
1607477.25900102735380.7102526281607191.94315374 734533.15435344
#Sta/Elev= 30
       0  336.32  132.95  334.91  174.82  335.32  268.17  333.57  293.77  334.86
  320.92  332.12   339.2  332.29  390.59   330.7  595.06  330.33  651.25  329.08
  664.97  327.68  679.08  327.61  693.08  329.24  712.99  331.55  749.33  330.89
  786.26  331.47  854.59  333.47  895.42  335.84  917.01  336.12 1007.84  341.91
 1176.63  354.84 1199.87  356.18 1219.29  356.22 1266.35  360.42 1352.53  365.87
 1384.52  368.93 1445.85  371.87  1554.4  374.08 1620.87  378.42 1639.18  378.46
#Mann= 3 , 0 , 0
       0      .1       0  651.25     .04       0  693.08      .1       0
#XS Ineff= 2 , 0
           644.9  331.45  701.89          331.43
Permanent Ineff=
       F       F
Bank Sta=651.25,693.08
XS Rating Curve= 0 ,0
Exp/Cntr=0.5,0.3

Type RM Length L Ch R = 1 ,10318.90,2858.19,3076.28,2950.41
XS GIS Cut Line= 4
1608280.44396105735616.1782065781607888.46468635735324.706438184
1607667.34817241735083.4884229751607486.43466099734168.870115295
#Sta/Elev= 30
       0  371.27  111.23   364.5  143.59  361.51  183.12  360.59  256.31  355.39
  276.32  352.52   313.8  350.72  354.75  345.13  392.47  336.03  436.86  331.15
   511.9  329.16  551.15  330.12   580.6  329.69  600.42  328.42  617.62  325.94
  633.45  325.29  655.61  328.26  716.32  329.12  818.96  342.67  980.83  355.56
 1037.91  355.17 1087.86  356.36 1152.57  355.15 1187.76  355.65 1273.39  361.83
 1377.44  364.44 1458.91  368.61 1473.18   368.2 1665.85  378.94 1748.04   380.8
#Mann= 3 , 0 , 0
       0      .1       0  600.42    .045       0  655.61      .1       0
Bank Sta=600.42,655.61
XS Rating Curve= 0 ,0
Exp/Cntr=0.3,0.1

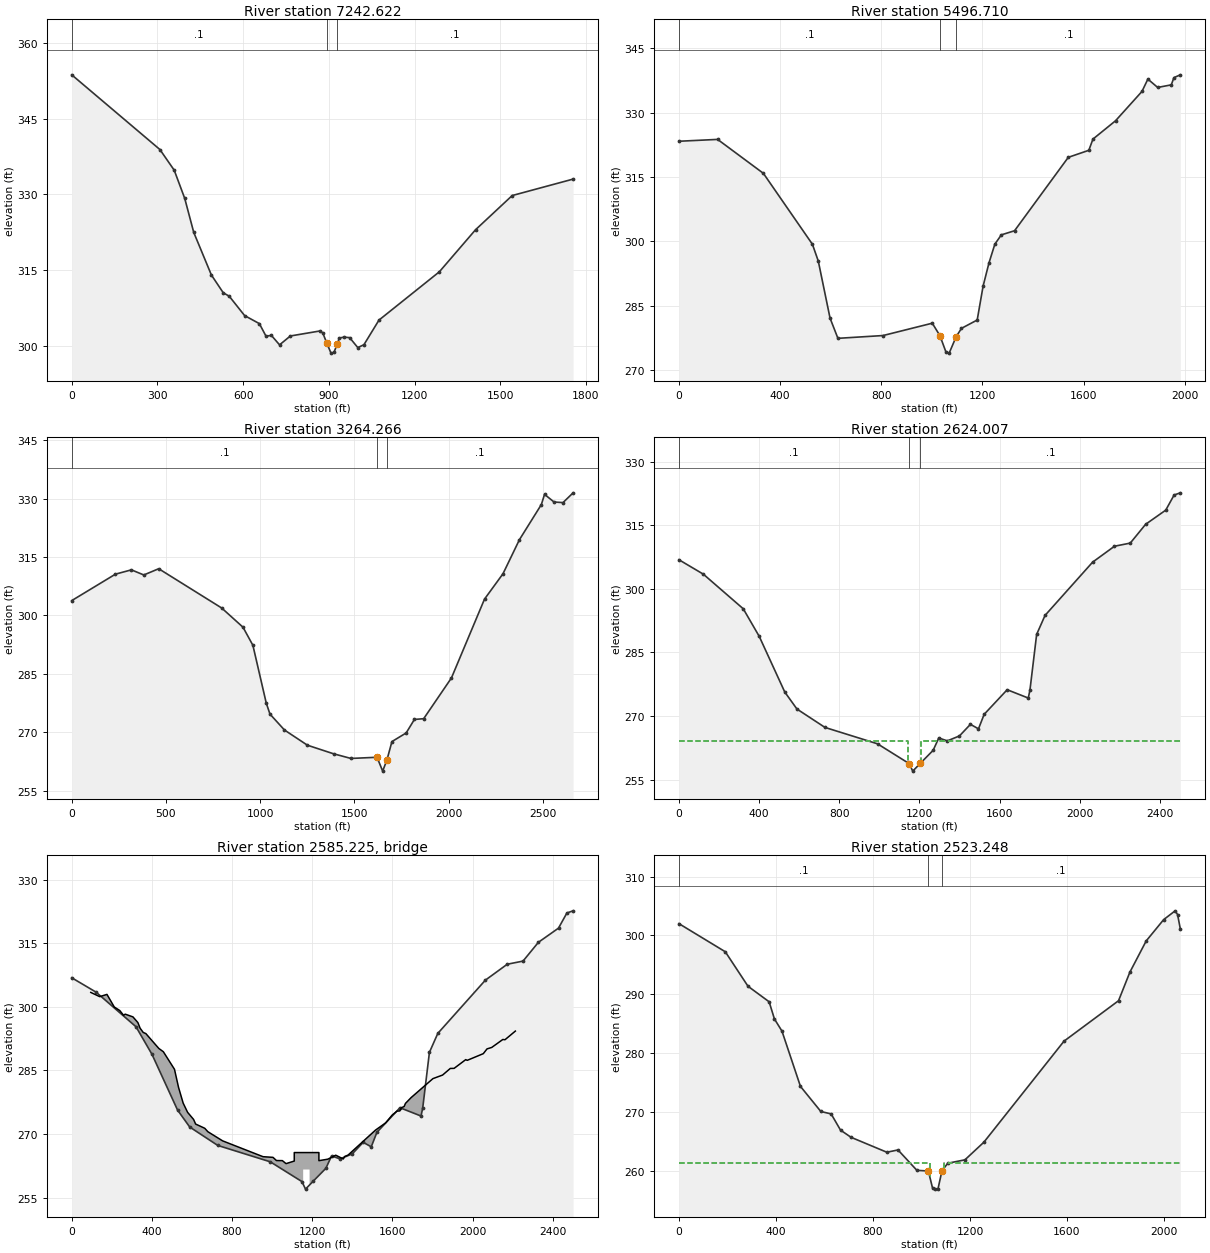
Type RM Length L Ch R = 1 ,7242.622,1756.11,1745.91,1718.54
XS GIS Cut Line= 3
1610526.78672771734972.9301660061610065.37556893734373.590338424
 1609381.0011555733646.231082335
#Sta/Elev= 30
       0  353.72  308.65  338.91  358.77  334.81  395.55  329.22  427.11  322.48
  488.94  314.03  530.31  310.52  551.51  309.82  605.19  305.99  656.79   304.4
  680.06  301.91   698.8  302.07  727.47  300.19  765.36  301.95  868.56  302.94
   878.7  302.57  892.09  300.65  907.54  298.55  917.95   298.7  929.85  300.41
  936.37  301.54  953.02  301.72  972.83  301.62 1001.36  299.65 1022.88  300.22
 1075.53   305.1 1287.02  314.68 1413.56  323.01 1541.89  329.79 1755.09  333.05
#Mann= 3 , 0 , 0
       0      .1       0  892.09    .045       0  929.85      .1       0
Bank Sta=892.09,929.85
XS Rating Curve= 0 ,0
Exp/Cntr=0.3,0.1

Type RM Length L Ch R = 1 ,5496.710,2204.49,2232.44,2118.9
XS GIS Cut Line= 2
1611290.64377593733379.8861905491609501.61016305732525.572386652
#Sta/Elev= 30
       0  323.32  152.83  323.75  333.72  315.84  527.65   299.3  550.92  295.37
  597.41  282.07  628.49  277.36   806.9  278.01 1001.67  280.89 1031.86  277.98
 1055.13  274.26 1068.39  273.91 1096.17  277.75 1117.12  279.69 1179.25  281.63
 1202.52  289.52 1225.79  294.94 1249.06  299.32 1274.67  301.49 1326.96  302.45
 1539.47  319.57  1620.7  321.21 1636.92  323.82 1726.18  328.09 1830.85  334.94
 1854.12  337.81 1892.91  335.87 1946.68  336.47 1957.18  338.16 1982.55  338.81
#Mann= 3 , 0 , 0
       0      .1       0 1031.86    .045       0 1096.17      .1       0
Bank Sta=1031.86,1096.17
XS Rating Curve= 0 ,0
Exp/Cntr=0.3,0.1

Type RM Length L Ch R = 1 ,3264.266,577.93,640.26,675.07
XS GIS Cut Line= 3
1611250.44077337732045.1465063541610114.70595175731331.543211371
1608798.05761871731430.040567562
#Sta/Elev= 30
       0  303.81  232.23  310.61  316.65  311.71  382.58   310.4  461.73     312
  795.93  301.91  909.08  296.97  961.52  292.33 1032.52  277.47 1052.21  274.65
 1128.98  270.57 1250.93  266.66 1389.47  264.46 1481.91  263.26 1620.55  263.56
 1650.38     260 1673.61  262.97 1699.52  267.59 1775.14  269.81 1818.85  273.28
 1867.99  273.47  2015.4  283.94 2190.89  304.19 2289.16  310.72 2376.28  319.46
 2492.73  328.49 2509.58  331.11 2559.89  329.14 2607.54  328.99  2661.2   331.5
#Mann= 3 , 0 , 0
       0      .1       0 1620.55    .045       0 1673.61      .1       0
Bank Sta=1620.55,1673.61
XS Rating Curve= 0 ,0
Exp/Cntr=0.5,0.3

Type RM Length L Ch R = 1 ,2624.007,99.77,100.76,99.32
XS GIS Cut Line= 5
1610858.46149866731683.3194835481610298.69856367731379.373795211
1610144.85820365731150.6296999451610041.54697181730432.757790461
1609318.54104692729959.449788049
#Sta/Elev= 30
       0  306.84  121.71  303.44  320.85  295.28   400.5  288.78  527.95  275.66
  588.75  271.65   728.7  267.31  990.78  263.45 1148.94  258.78 1166.62  257.01
 1204.73  258.86 1268.38  261.92 1296.67  264.83  1339.1  264.14 1399.75  265.31
 1454.46  268.04 1494.69  266.98 1522.98   270.4 1637.89   276.2 1743.13  274.24
 1751.49  276.11 1784.96  289.25 1826.79  293.72  2064.3  306.28 2173.38  310.03
 2252.18  310.77 2328.79   315.2 2429.18  318.54 2471.02  322.11 2502.04  322.62
#Mann= 3 , 0 , 0
       0      .1       0 1148.94     .04       0 1204.73      .1       0
#XS Ineff= 2 , 0
         1145.27  264.14 1208.02          264.08
Permanent Ineff=
       F       F
Bank Sta=1148.94,1204.73
XS Rating Curve= 0 ,0
Exp/Cntr=0.5,0.3

Type RM Length L Ch R = 3 ,2585.225,,,
BEGIN DESCRIPTION:
Dr. Miller Rd.
END DESCRIPTION:
Bridge Culvert--1,0,-1,-1, 0
Deck Dist Width WeirC Skew NumUp NumDn MinLoCord MaxHiCord MaxSubmerge Is_Ogee
25,22,2.6,0, 60, 10, , , 0.98, 0, 0,0,,
      95  139.64  175.69  212.28  239.76  258.73  266.67  305.33  330.18  341.19
   356.7  369.88  434.71  457.21  512.79  532.94  556.07  578.18  608.06  618.33
  663.63  679.51  752.91   954.6 1004.27 1021.55 1051.17 1069.37  1110.5  1110.5
    1155    1187  1233.5  1233.5 1277.79 1317.46 1355.22 1362.27 1378.89 1515.69
 1566.94  1599.4 1623.43 1637.55 1644.61 1658.74 1665.38 1693.64 1802.43 1850.57
 1889.08 1908.15 1966.27 1973.54 2053.91 2072.42 2095.89 2151.26 2162.06 2213.85
  303.38  302.39  302.92  299.95  299.11  297.99  298.26  297.62  296.27  294.95
  293.95  293.68  290.17   289.4  285.26  281.01  277.29  275.12  273.44  272.35
  271.36  270.54  268.39  264.66   264.5  263.75  263.73  263.02  263.63  265.63
  265.63  265.63  265.63  263.72  264.07  265.01  264.12  264.71  265.03  270.92
  272.64  274.49   275.4  275.45  276.19  276.49  277.22  278.59  283.06   283.9
  285.46  285.48  287.54  287.37  288.95  290.07  290.41  292.29  292.23  294.27
                                                                                
                                                                                
                                                                                
  261.63  261.63
                                                                                
                                                                                
   903.5     990   998.5   998.5    1045    1077  1123.5  1123.5    1164    1241
  263.63  263.63  263.63  265.63  265.63  265.63  265.63  263.72  263.72  264.42
                                  261.63  261.63
BR Coef=-1 , 0 , 0 ,, 0 ,,,0.8,0,,0,
WSPro=,,,, 1 ,,,, 0 ,,,, 0 ,,,,-1 ,-1 ,-1 , 0 , 0 , 0 , 0 , 0
BC Design=,, 0 ,, 0 ,,,,,,
BC Use User HTab Curves=0
BC User HTab FreeFlow(D)= 0

Type RM Length L Ch R = 1 ,2523.248,540.05,541.41,538.55
XS GIS Cut Line= 6
1610868.90426733731599.2570404111610328.51324098731308.563936591
1610227.88870502 731032.778171421610175.71301974 730667.54837431
1610132.05809334730235.1278254241610000.55179052729903.547268108
#Sta/Elev= 30
       0  301.99  191.09  297.21  284.67  291.35  371.77  288.71  393.65  285.79
  424.66  283.73  500.97  274.33  584.88  270.07  627.52  269.65  666.17   266.9
  709.49  265.68   857.2  263.14  903.22  263.53  981.21  260.06 1028.35  259.95
 1045.48  257.07 1055.54  256.87 1068.12  256.92 1084.55  259.99 1108.49  261.27
  1179.2  261.85 1257.41  264.85 1587.75  282.02 1812.54  288.89 1859.42  293.75
 1926.56  299.05 1998.55  302.67 2045.98  304.17 2055.97  303.54 2067.45  301.09
#Mann= 3 , 0 , 0
       0      .1       0 1028.35     .04       0 1084.55      .1       0
#XS Ineff= 2 , 0
         1034.96  261.29  1092.1          261.31
Permanent Ineff=
       F       F
Bank Sta=1028.35,1084.55
XS Rating Curve= 0 ,0
Exp/Cntr=0.5,0.3

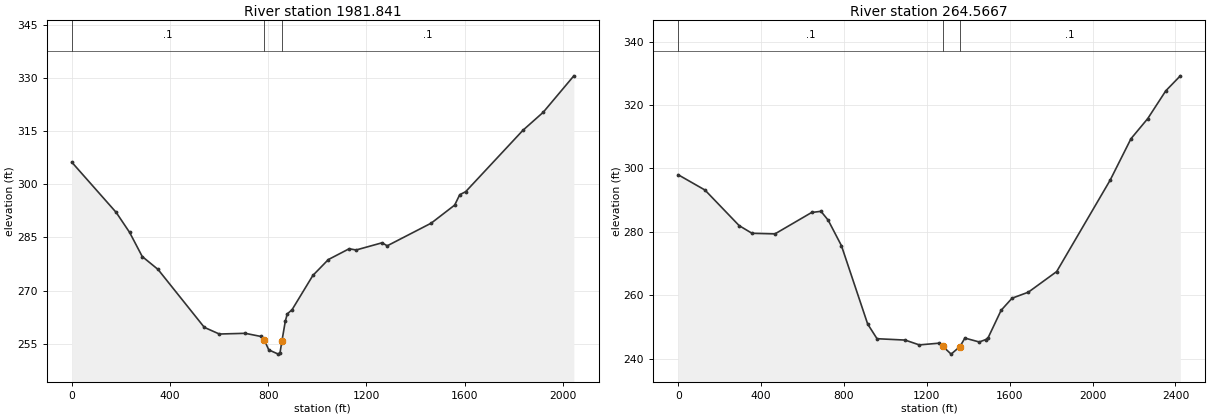
Type RM Length L Ch R = 1 ,1981.841,1650.86,1717.28,1631.62
XS GIS Cut Line= 4
 1611144.6900325731591.8033710871610973.25563794731368.193291232
1610768.00474295731140.5789493171610607.19273283729693.270858034
#Sta/Elev= 30
       0  306.23  180.95  292.05  235.61  286.41  287.04  279.61   351.2  275.98
  539.73  259.64  600.85  257.76  706.18  257.96  770.45  257.07  784.53  255.99
   802.2  253.29  840.88  252.09  847.92  252.45  855.92  255.84  869.62   261.4
  877.55  263.43  897.22  264.64  981.74  274.28 1044.76  278.76 1129.65  281.81
 1157.82  281.46 1263.46  283.49 1284.59  282.64 1463.88  289.04 1559.27  294.13
 1579.74  297.05 1603.89   297.9 1837.11  315.22 1919.71   320.3 2044.47  330.58
#Mann= 3 , 0 , 0
       0      .1       0  784.53    .045       0  855.92      .1       0
Bank Sta=784.53,855.92
XS Rating Curve= 0 ,0
Exp/Cntr=0.3,0.1

Type RM Length L Ch R = 1 ,264.5667,225.07,264.57,217.1
XS GIS Cut Line= 5
1611475.48911768731573.1691977681611564.34133829731404.018338695
1612136.91697924730617.939916372  1611815.292959730266.163644165
1611383.11068173729612.864852965
#Sta/Elev= 30
       0  297.98  129.05  293.17  294.22  281.94  356.09  279.53  466.85  279.34
  643.93  286.09  688.99  286.46  723.69  283.67  787.71  275.64  914.49  250.91
  959.59  246.29 1095.31  245.86 1163.57  244.34 1260.37  244.89 1276.82  243.91
 1317.28  241.43 1359.81  243.82 1383.67  246.49 1453.18  245.26  1484.3  246.02
 1496.14  246.64 1558.44  255.24  1611.3  259.06 1690.17  260.97 1826.72  267.46
 2084.64  296.26 2185.37  309.35  2266.2  315.69 2353.22  324.44 2423.53  329.18
#Mann= 3 , 0 , 0
       0      .1       0 1276.82    .045       0 1359.81      .1       0
Bank Sta=1276.82,1359.81
XS Rating Curve= 0 ,0
Exp/Cntr=0.3,0.1

Chan Stop Cuts=-1
Use User Specified Reach Order=0